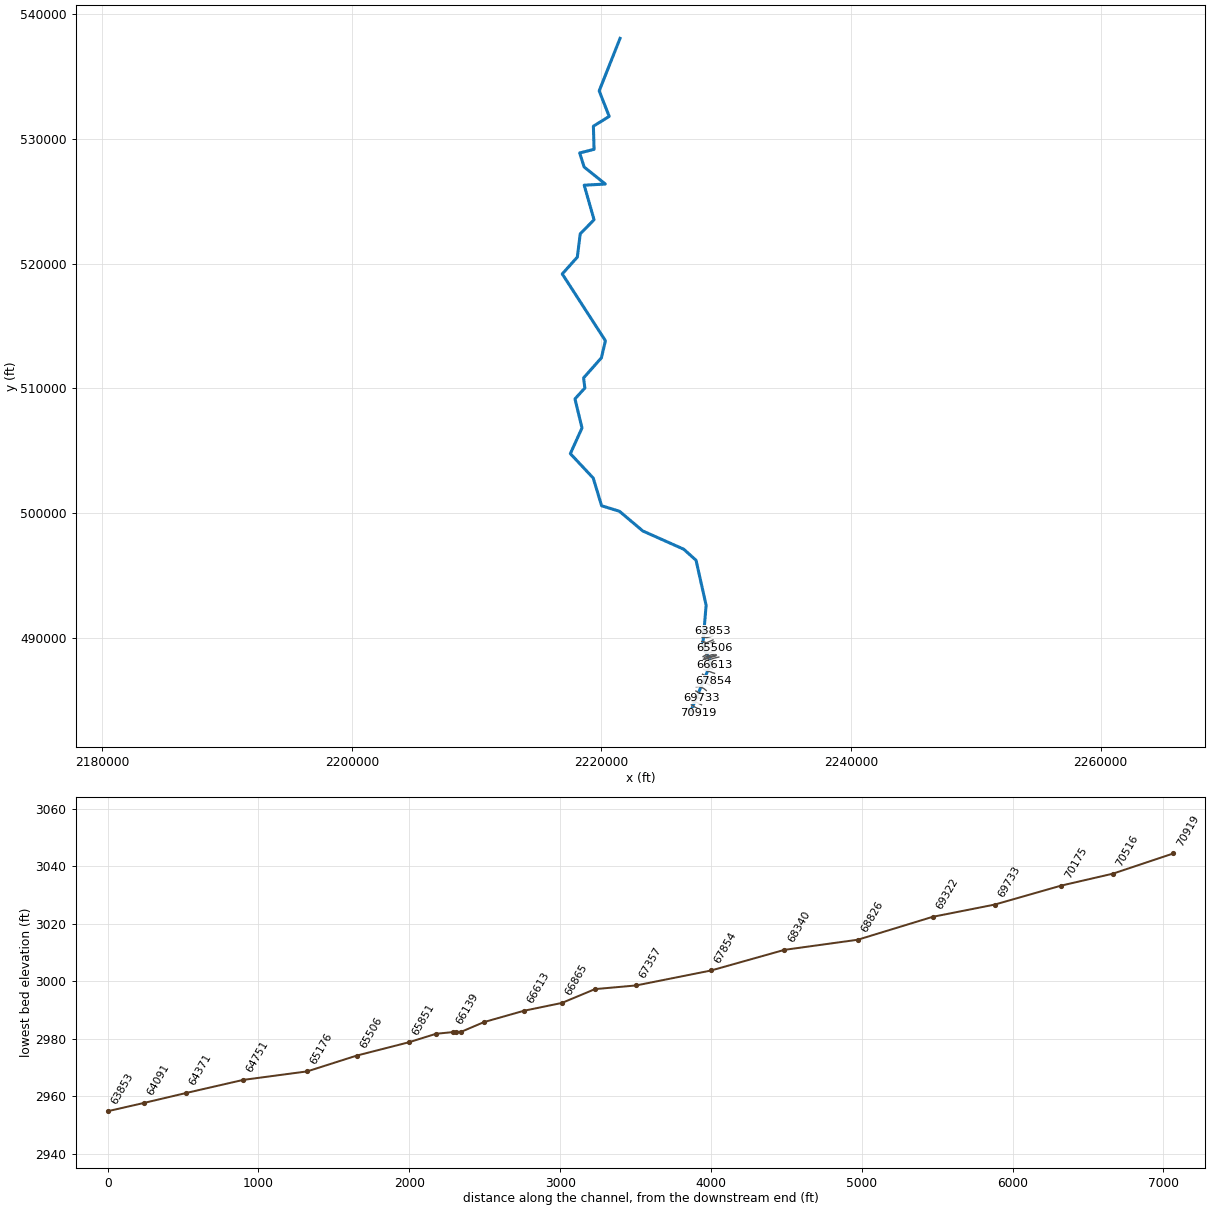
--- OLDFLDFK1.prj (project) ---

Proj Title=OLDFLDFK1
Current Plan=p01
Default Exp/Contr=0,0
English Units
Geom File=g01
Flow File=f01
Plan File=p01
Background Map Layer=Inundation Boundary (01pct Value_0)
BEGIN DESCRIPTION:
----------MODEL BY WOOD PLC 2021----------
Stream Name: Old Field Fork Lower Reach / Elk Run
Flood Zone: Alternating Enhanced Approximate / Detailed
Pocahontas County, WV
HEC-RAS Version: model run in RAS 6.1.0
Vertical Datum: NAVD88
Projection: NAD 1983 StatePlane West Virginia S FIPS 4702 (US Feet)
Terrain: 1-meter LIDAR (FEMA Region III 3DEP collected 2016-2018)
Land Use: 2019 NLCD
Hydrologic Method:
WV SIR2010-5033 regression equations weighted with gage 03193830
Model Notes:
Approximate Zone A: 70919-59122, Detailed Zone AE: 58823-26761, Approximate Zone A: 26497-9
END DESCRIPTION:
DSS File=dss
DSS Export Rating Curves= 0
DSS Export Rating Curve Sorted= 0
DSS Export Volume Flow Curves= 0
DXF OffsetX= 0
DXF OffsetY= 0
DXF ScaleX= 0
DXF ScaleY= 0

--- OLDFLDFK1.p01 (plan) ---

Plan Title=Floodplain
Program Version=6.10
Short Identifier=Floodplain
Geom File=g01
Flow File=f01
Subcritical Flow
K Sum by GR= 0
Std Step Tol= 0.01
Critical Tol= 0.01
Num of Std Step Trials= 20
Max Error Tol= 0.3
Flow Tol Ratio= 0.001
Split Flow NTrial= 30
Split Flow Tol= 0.02
Split Flow Ratio= 0.02
Log Output Level= 0
Friction Slope Method= 1
Unsteady Friction Slope Method= 2
Unsteady Bridges Friction Slope Method= 1
Parabolic Critical Depth
Global Vel Dist= 0 , 0 , 0
Global Log Level= 0
CheckData=True
Encroach Param=-1 ,0,0, 2
Encroach River=OLDFLDFK1
Encroach Reach=Main
Encroach Node=58823
       1  189.96     255
Encroach Node=58415
       1   185.4   402.8
Encroach Node=58094
       1  239.93     445
Encroach Node=57749
       1  225.39  467.12
Encroach Node=57251
       1     138  264.56
Encroach Node=57120
       1   108.5  207.43
Encroach Node=56839
       1     202  344.31
Encroach Node=56473
       1     180     357
Encroach Node=56203
       1  188.46   347.7
Encroach Node=55855
       1     158     216
Encroach Node=55565
       1  203.96   291.7
Encroach Node=55238
       1   167.4  284.15
Encroach Node=54925
       1  222.26   309.3
Encroach Node=54704
       1     210     340
Encroach Node=54479
       1     200     425
Encroach Node=54077
       1     294     500
Encroach Node=53770
       1    70.2  244.13
Encroach Node=53297
       1  132.66     325
Encroach Node=52906
       1     210  404.43
Encroach Node=52540
       1   259.5     510
Encroach Node=52121
       1  520.92  747.88
Encroach Node=51762
       1  414.05  668.04
Encroach Node=51367
       1  683.37     921
Encroach Node=50992
       1     630     712
Encroach Node=50916
       1 1011.95 1055.26
Encroach Node=50867
       1   995.3    1040
Encroach Node=50736
       1  876.66   943.2
Encroach Node=50350
       1  721.77     876
Encroach Node=50054
       1  570.35     768
Encroach Node=49735
       1  667.55     831
Encroach Node=49492
       1   594.5     717
Encroach Node=49237
       1     500     615
Encroach Node=49015
       1     465     615
Encroach Node=48783
       1  475.81     660
Encroach Node=48638
       1     305     570
Encroach Node=48482
       1     135     450
Encroach Node=48402
       1     202     540
Encroach Node=48371
       1      92     420
Encroach Node=48234
       1   128.4     370
Encroach Node=47918
       1     155  349.61
Encroach Node=47729
       1   142.8  331.38
Encroach Node=47338
       1  204.08     382
Encroach Node=46999
       1     200  382.18
Encroach Node=46620
       1     320  594.13
Encroach Node=46255
       1     300  598.34
Encroach Node=46053
       1     360   628.1
Encroach Node=45872
       1     375   599.7
Encroach Node=45670
       1     370   599.7
Encroach Node=45455
       1     370   542.7
Encroach Node=45151
       1  382.96     575
Encroach Node=44976
       1     325     510
Encroach Node=44841
       1  273.17     485
Encroach Node=44463
       1     390     525
Encroach Node=44171
       1     380     555
Encroach Node=44051
       1  398.51     550
Encroach Node=43800
       1  305.43  481.75
Encroach Node=43488
       1   240.9  391.91
Encroach Node=43196
       1   154.9  259.97
Encroach Node=42834
       1   300.5     425
Encroach Node=42483
       1   264.7     375
Encroach Node=42315
       1   149.1     330
Encroach Node=42125
       1   174.7     330
Encroach Node=41747
       1     195     271
Encroach Node=41401
       1   121.8     230
Encroach Node=41136
       1   187.4     285
Encroach Node=40825
       1     510   563.9
Encroach Node=40595
       1   679.8   730.6
Encroach Node=40405
       1  919.44   979.4
Encroach Node=40312
       1  926.28  977.07
Encroach Node=40262
       1  961.91  1012.7
Encroach Node=40080
       1     630   675.6
Encroach Node=39834
       1   690.6  736.58
Encroach Node=39614
       1     506   558.8
Encroach Node=39341
       1     415   491.2
Encroach Node=39078
       1  456.71  560.34
Encroach Node=38874
       1   428.5  490.53
Encroach Node=38560
       1     455     530
Encroach Node=38307
       1   240.1  369.76
Encroach Node=37902
       1     338   406.2
Encroach Node=37619
       1   374.4  423.69
Encroach Node=37312
       1   485.1  548.67
Encroach Node=37054
       1  529.93     622
Encroach Node=36623
       1     375  443.53
Encroach Node=36277
       1     208   267.8
Encroach Node=35938
       1     370   455.8
Encroach Node=35618
       1   361.9   433.4
Encroach Node=35335
       1     342  403.59
Encroach Node=35122
       1   206.7  275.92
Encroach Node=34812
       1   299.3     365
Encroach Node=34527
       1   332.3   378.9
Encroach Node=34325
       1   395.4  438.75
Encroach Node=34069
       1   380.4   442.3
Encroach Node=33837
       1   416.3   469.8
Encroach Node=33582
       1   271.2   341.2
Encroach Node=33370
       1   148.6     220
Encroach Node=33165
       1     173     250
Encroach Node=33011
       1   353.1  402.33
Encroach Node=32758
       1   362.2   417.4
Encroach Node=32538
       1  441.33   503.4
Encroach Node=32343
       1   397.1   469.5
Encroach Node=32138
       1   357.9  423.32
Encroach Node=31864
       1  373.09   507.8
Encroach Node=31644
       1  411.64  532.05
Encroach Node=31570
       1   421.1     589
Encroach Node=31530
       1  431.75   602.5
Encroach Node=31415
       1     405     505
Encroach Node=31276
       1     388   475.6
Encroach Node=30967
       1   223.1   299.7
Encroach Node=30805
       1   114.6   210.8
Encroach Node=30675
       1     180  268.53
Encroach Node=30548
       1  141.34   199.5
Encroach Node=30303
       1     255   329.1
Encroach Node=29955
       1   441.3  499.74
Encroach Node=29736
       1     485     570
Encroach Node=29324
       1     515     615
Encroach Node=29105
       1     470   543.5
Encroach Node=28840
       1     350     460
Encroach Node=28753
       1     370     580
Encroach Node=28704
       1     388     630
Encroach Node=28564
       1     332     695
Encroach Node=28359
       1  290.03     700
Encroach Node=28150
       1  217.37     660
Encroach Node=27845
       1   110.9     390
Encroach Node=27804
       1     103     420
Encroach Node=27636
       1  125.16     400
Encroach Node=27491
       1   149.3     370
Encroach Node=27468
       1     160     400
Encroach Node=27343
       1     201     318
Encroach Node=27092
       1     330  517.69
Encroach Node=26860
       1     405   620.8
Encroach Node=26825
       1     333     504
Encroach Node=26761
       1     380   477.9
Computation Interval=0.1SEC
Output Interval=1SEC
Instantaneous Interval=Max Profile
Mapping Interval=1HOUR
Computation Time Step Use Courant=        0
Computation Time Step Use Time Series=    0
Computation Time Step Count To Double=0
Computation Time Step Max Doubling=0
Computation Time Step Max Halving=0
Computation Time Step Residence Courant=0
Run HTab= 0
Run UNet= 0
Run Sediment= 0
Run PostProcess= 0
Run WQNet= 0
Run RASMapper=-1
UNET Theta= 0
UNET Theta Warmup= 0
UNET ZTol= 0
UNET ZSATol= 0
UNET MxIter= 0
UNET Max Iter WO Improvement= 0
UNET MaxInSteps= 0
UNET DtIC= 0
UNET DtMin= 0
UNET MaxCRTS= 0
UNET WFStab= 0
UNET SFStab= 0
UNET WFX= 1
UNET SFX= 1
UNET Gravity=32.174
UNET 1D Methodology=Finite Difference
UNET DSS MLevel= 1
UNET Pardiso=0
UNET DZMax Abort= 0
UNET Use Existing IB Tables= 0
UNET Froude Reduction=False
UNET Froude Limit= 0
UNET Froude Power= 0
UNET D1 Cores= 0
UNET WindReference=Eulerian
UNET WindDragFormulation=Hsu (1988)
UNET D2 Coriolis=0
UNET D2 Cores= 0
UNET D2 Theta= 1
UNET D2 Theta Warmup= 1
UNET D2 Z Tol= 0.01
UNET D2 Volume Tol= 0.01
UNET D2 Max Iterations= 20
UNET D2 Equation= 0
UNET D2 RampUpFraction=0.1
UNET D2 TimeSlices= 1
UNET D2 Turbulence Formulation=Non-Conservative (original)
UNET D2 Eddy Viscosity=0.3
UNET D2 Transverse Eddy Viscosity=0.1
UNET D2 Smagorinsky Mixing=0
UNET D2 BCVolumeCheck=0
UNET D2 Cores=0
UNET D2 SolverType=PARDISO (Direct)
UNET D2 Minimum Iterations= 2147483647
UNET D2 Maximum Iterations= 2147483647
UNET D2 Restart Number= 10
UNET D2 Relaxation Coeff=1.3
UNET D2 SOR Precondition Iterations= 10
UNET D2 ILUT Maximum Fill= 8
UNET D2 ILUT Tolerance=1E-08
UNET D1D2 MaxIter= 0
UNET D1D2 ZTol=0.01
UNET D1D2 QTol=0.1
UNET D1D2 MinQTol=1
DSS File=dss
Write IC File= 0
Write IC File at Fixed DateTime=0
Write IC File at Sim End=0
Echo Input=False
Echo Parameters=False
Echo Output=False
Write Detailed= 0
HDF Write Warmup=0
HDF Write Time Slices=0
HDF Flush=0
HDF Compression= 1
HDF Chunk Size= 1
HDF Spatial Parts= 1
HDF Use Max Rows=0
HDF Fixed Rows= 1
Calibration Method= 0
Calibration Iterations= 20
Calibration Max Change=0.05
Calibration Tolerance=0.2
Calibration Maximum=1.5
Calibration Minimum=0.5
Calibration Optimization Method= 1
WQ AD Non Conservative
WQ ULTIMATE=-1
WQ Max Comp Step=1HOUR
WQ Output Interval=15MIN
WQ Output Selected Increments= 0
WQ Output face flow=0
WQ Output face velocity=0
WQ Output face area=0
WQ Output face dispersion=0
WQ Output cell volume=0
WQ Output cell surface area=0
WQ Output cell continuity=0
WQ Output cumulative cell continuity=0
WQ Output face conc=0
WQ Output face dconc_dx=0
WQ Output face courant=0
WQ Output face peclet=0
WQ Output face adv mass=0
WQ Output face disp mass=0
WQ Output cell mass=0
WQ Output cell source sink temp=0
WQ Output nsm pathways=0
WQ Output nsm derived pathways=0
WQ Create Restart=0
WQ Fixed Restart=0
WQ System Summary=0
WQ Write To DSS=0
Sorting and Armoring Iterations= 10
XS Update Threshold= 0.02
Bed Roughness Predictor= 0
Hydraulics Update Threshold= 0.02
Energy Slope Method= 1
Volume Change Method= 1
Sediment Retention Method= 0
Sediment TS Multiplier= 1
Warm Up Method= 0
XS Weighting Method= 0
Number of US Weighted Cross Sections= 1
Number of DS Weighted Cross Sections= 1
Upstream XS Weight=0
Main XS Weight=1
Downstream XS Weight=0
Number of DS XS's Weighted with US Boundary= 1
Upstream Boundary Weight= 1
Weight of XSs Associated with US Boundary= 0
Number of US XS's Weighted with DS Boundary= 1
Downstream Boundary Weight= 0.5
Weight of XSs Associated with DS Boundary= 0.5
Percentile Method= 0
Sediment Output Level= 3
Mass or Volume Output= 0
Output Increment Type= 1
Profile and TS Output Increment= 1
Transport Output Increment 1
XS Output Flag= 0
XS Output Increment= 10
Read HDF5 Sediment Hotstart= 0
Sediment Hotstart Type= 0
Write Gradation File= 0
Read Gradation Hotstart= 0
Write HDF5 File= 1
Write Binary Output= 1
Write DSS Sediment File= 0
DSS Sediment Output Type= 1
SV Curve= 0
Specific Gage Flag= 0
Subcell Erosion Methods= 0
Subcell Deposition Methods= 0
Advection Scheme= 1
Matrix Solver= 0
Implicit Weighting Factor= 1
Maximum Outer Loop Convergence Iterations= 5
Convergence Maximum Absolute= 0.001
Convergence RMSE= 0.0001
Grain Fractions Max Abs Error= 0.001
Max Subgrid Regions= 1
Max Subgrid Length Scale= 3.402823E+38
Initial Layer Thickness= 3.402823E+38
Min Layer Thickness= 3.402823E+38
Max Layer Thickness= 3.402823E+38
Number of Layers= 5

--- OLDFLDFK1.f01 (steady flow) ---

Flow Title=Flow
Program Version=6.10
Number of Profiles= 7
Profile Names=01pct,FW,10pct,04pct,02pct,0_2pct,01plus
River Rch & RM=OLDFLDFK1,Main            ,70919
    2030    2030    1100    1430    1720    2860    2930
River Rch & RM=OLDFLDFK1,Main            ,67084
    2300    2300    1250    1640    1960    3220    3340
River Rch & RM=OLDFLDFK1,Main            ,60618
    2700    2700    1480    1930    2300    3740    3930
River Rch & RM=OLDFLDFK1,Main            ,56473
    3000    3000    1660    2160    2560    4140    4380
River Rch & RM=OLDFLDFK1,Main            ,50736
    3650    3650    2050    2640    3120    4980    5350
River Rch & RM=OLDFLDFK1,Main            ,40080
    4060    4060    2290    2950    3480    5510    5960
River Rch & RM=OLDFLDFK1,Main            ,31276
    4640    4640    2640    3380    3990    6270    6830
River Rch & RM=OLDFLDFK1,Main            ,26761
    7490    7490    4370    5540    6480    9970   11100
River Rch & RM=OLDFLDFK1,Main            ,22089
    8340    8340    4890    6180    7220   11100   12300
River Rch & RM=OLDFLDFK1,Main            ,434
   10600   10600    6240    7860    9160   14000   15600
Boundary for River Rch & Prof#=OLDFLDFK1,Main            , 1
Up Type= 0
Dn Type= 1
Dn Known WS=2493.5
Boundary for River Rch & Prof#=OLDFLDFK1,Main            , 2
Up Type= 0
Dn Type= 1
Dn Known WS=2493.5
Boundary for River Rch & Prof#=OLDFLDFK1,Main            , 3
Up Type= 0
Dn Type= 1
Dn Known WS=2490.6
Boundary for River Rch & Prof#=OLDFLDFK1,Main            , 4
Up Type= 0
Dn Type= 1
Dn Known WS=2491.7
Boundary for River Rch & Prof#=OLDFLDFK1,Main            , 5
Up Type= 0
Dn Type= 1
Dn Known WS=2492.6
Boundary for River Rch & Prof#=OLDFLDFK1,Main            , 6
Up Type= 0
Dn Type= 1
Dn Known WS=2495.3
Boundary for River Rch & Prof#=OLDFLDFK1,Main            , 7
Up Type= 0
Dn Type= 1
Dn Known WS=2496.2
DSS Import GetInterval= 0
DSS Import GetPeak= 0
DSS Import FillOption= 0

--- OLDFLDFK1.g01 (geometry) ---

Geom Title=Geometry
Program Version=6.10

River Reach=OLDFLDFK1       ,Main
Reach XY= 30
2227174.17646784484159.3480163962228783.82187057488011.546020657
2228116.77596055489379.402536899  2228387.883358492611.504668489
 2227581.3590524496218.8334118282226593.27638292497105.564249903
2223317.36659615498566.2378377322221445.64921099500145.909875244
2220013.12123615500590.6767022462219342.91982067502809.771673501
2217509.63477328 504767.395710992218443.82975534506828.655696064
2217878.42832708509155.9555034042218671.33848667510029.225082308
2218570.98829362510839.1968875832220000.07434621 512453.68676883
2220318.26629515 513823.462572562216861.82438913519174.160860658
2218068.46961369 520524.718198912218300.70077649522387.907385901
2219409.24678774523521.8116141412218619.82743482526288.071829662
2220309.77517039 526383.646113562218615.55152473527746.811038151
2218257.00860667528874.129649654 2219409.5131914529164.716338813
2219355.36205301531020.2483889012220622.77651292531805.801935896
2219819.79517922533852.0229090752221492.74885434 538064.29105933

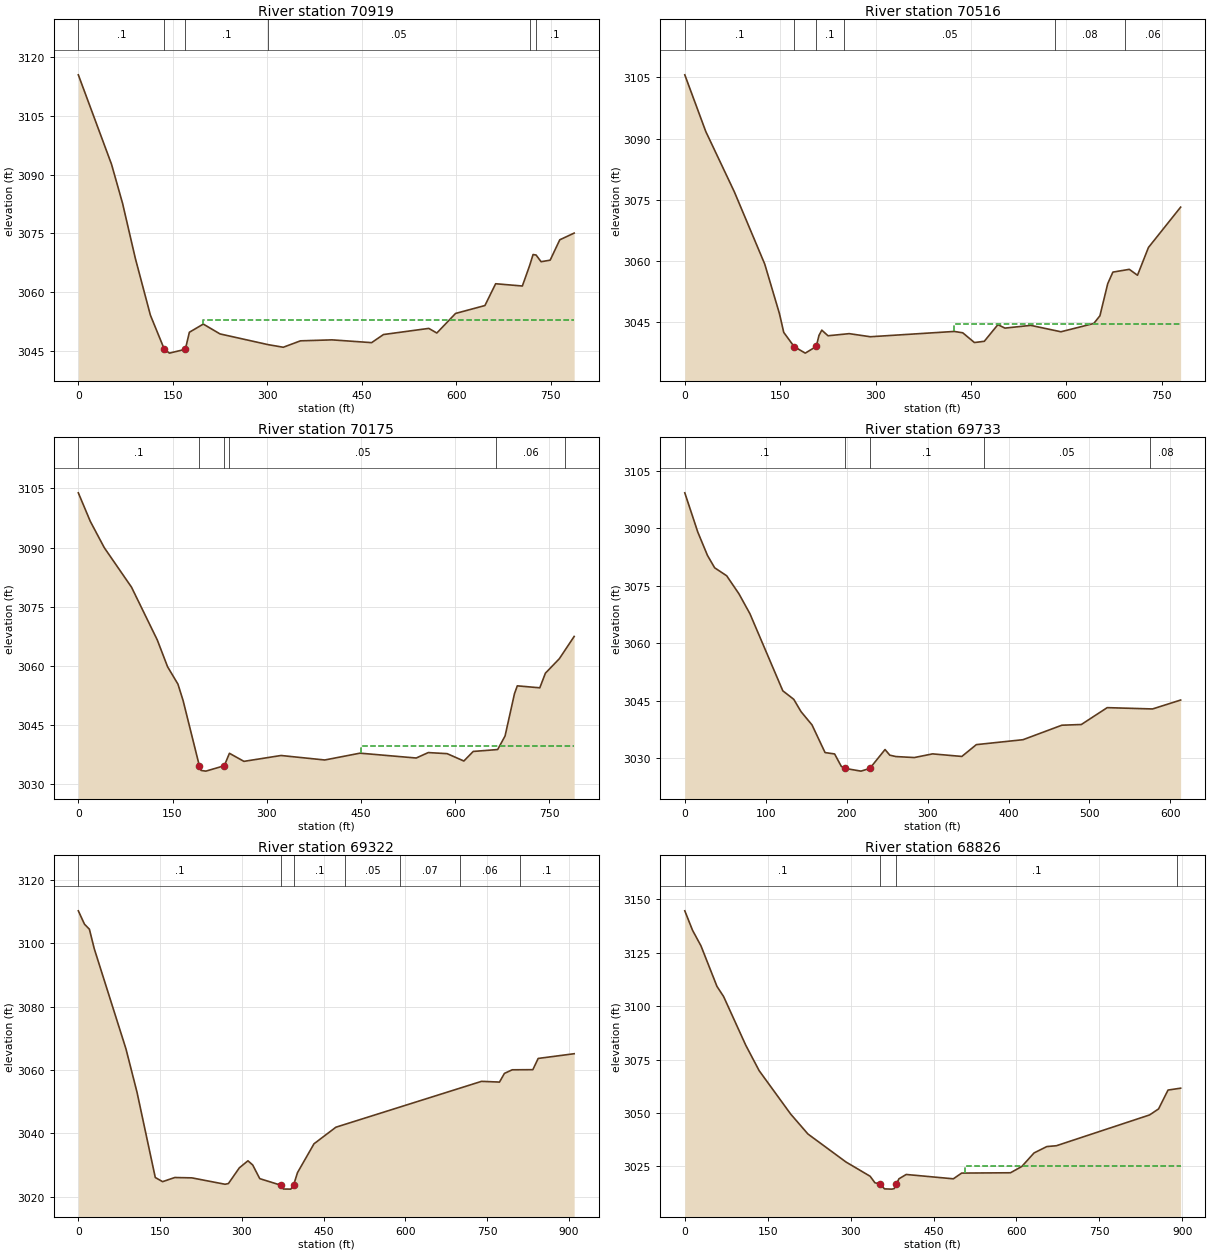
Type RM Length L Ch R = 1 ,70919   ,402.9,402.9,402.9
XS GIS Cut Line= 3
2227040.43780694484237.5778232742227353.76756795484091.597457204
2227769.69004165483944.473057034
#Sta/Elev= 30
       0 3115.53    52.7 3092.66    70.3 3082.63    90.4 3068.67   114.4  3054.1
   136.5 3045.39   144.6 3044.42  169.81  3045.4   176.2 3049.75   198.3 3051.84
   224.8 3049.33   301.1 3046.59   325.2 3045.92   352.5 3047.56   402.7 3047.81
   465.4  3047.1   484.2 3049.17   556.1 3050.74   568.9 3049.56   598.6 3054.56
   645.2 3056.58   662.2 3062.15   704.6 3061.57   716.2 3066.82   721.6 3069.61
   726.4 3069.49   734.3 3067.78   748.7 3068.17     764 3073.38   786.8 3075.09
#Mann= 6 ,-1,0
       0      .1       0   136.5    .045       0  169.81      .1       0
   301.1     .05       0   716.2     .06       0   726.4      .1       0
#XS Ineff= 2 , 0
                          197.73         3052.79
Permanent Ineff=
       F       F
Bank Sta=136.5,169.81
XS Rating Curve= 0 ,0
Exp/Cntr=0.3,0.1

Type RM Length L Ch R = 1 ,70516   ,330.1,341.1,353.1
XS GIS Cut Line= 3
2227202.56784559484633.1684248242227549.57443102484410.762659641
2227891.22184139484275.443489258
#Sta/Elev= 30
       0 3105.64      33 3091.73    77.9 3076.93   125.7  3059.2   148.8 3047.05
   155.6 3042.43  171.92 3038.95   189.4 3037.35   206.7 3038.98     211  3041.7
   215.4 3042.99   225.2 3041.61   258.5 3042.13   291.7 3041.37   423.6 3042.67
     437 3042.34   455.4 3039.95   470.9 3040.25   492.3 3044.34   503.4 3043.49
     544 3044.16   591.4 3042.59     643 3044.62   652.7 3046.51     665  3054.4
   673.1 3057.23   698.9 3057.91   711.8 3056.46     729 3063.27   779.6 3073.17
#Mann= 6 ,-1,0
       0      .1       0  171.92    .045       0   206.7      .1       0
     250     .05       0  582.16     .08       0  692.16     .06       0
#XS Ineff= 2 , 0
                          422.77          3044.4
Permanent Ineff=
       F       F
Bank Sta=171.92,206.7
XS Rating Curve= 0 ,0
Exp/Cntr(USF)=0,0
Exp/Cntr=0.3,0.1

Type RM Length L Ch R = 1 ,70175   ,449.2,442,431.8
XS GIS Cut Line= 3
2227277.59629649484890.4088279262227682.21401387484797.963058061
2228017.16245541484630.488837291
#Sta/Elev= 30
       0  3103.9    19.1 3096.64    41.4 3089.95    84.7 3079.93   125.7 3066.54
   142.1 3059.73   158.6 3055.32   166.8 3051.16  192.78 3034.53   195.5 3033.39
   203.1 3033.22   232.4 3034.59   240.6 3037.75   263.7  3035.7   322.7 3037.19
   392.4 3036.05   448.5 3037.78     538 3036.55   557.2 3037.93   587.2 3037.66
   613.9 3035.79   628.8 3038.22   667.7  3038.7   679.5 3042.15   694.5  3052.9
     699 3054.88   734.8 3054.38   743.7 3058.09   765.9 3061.77   789.5 3067.42
#Mann= 6 ,-1,0
       0      .1       0  192.78    .045       0   232.4      .1       0
     240     .05       0  665.04     .06       0  775.04      .1       0
#XS Ineff= 2 , 0
                          450.22         3039.56
Permanent Ineff=
       F       F
Bank Sta=192.78,232.4
XS Rating Curve= 0 ,0
Exp/Cntr(USF)=0,0
Exp/Cntr=0.3,0.1

Type RM Length L Ch R = 1 ,69733   ,409.5,411.1,412.8
XS GIS Cut Line= 3
2227476.83971532 485339.613532232227809.39498888485166.076061835
2228046.89289745485167.035516367
#Sta/Elev= 30
       0 3099.21    16.1 3088.95      28 3082.89    36.9 3079.65    51.7 3077.58
    66.9 3072.87    80.5 3067.66   121.1 3047.56   134.6 3045.35   143.6 3042.13
   157.2 3038.66   173.3 3031.45   185.1 3031.09   193.3 3027.88   197.8 3027.33
   217.7 3026.61   228.6 3027.32   247.4 3032.24   253.3 3030.77   260.9 3030.41
   283.5 3030.15   306.1 3031.11   342.3 3030.44   360.2 3033.52   417.9 3034.81
   465.9 3038.59   489.9 3038.77   521.9 3043.17   577.9 3042.83   612.6 3045.15
#Mann= 5 ,-1,0
       0      .1       0   197.8    .045       0   228.6      .1       0
     370     .05       0  575.11     .08       0
Bank Sta=197.8,228.6
XS Rating Curve= 0 ,0
Exp/Cntr=0.3,0.1

Type RM Length L Ch R = 1 ,69322   ,497,496.2,493.4
XS GIS Cut Line= 3
2227566.05031024485735.6467258272227842.97574315485596.498190473
2228397.19671717485367.145730158
#Sta/Elev= 30
       0  3110.3    11.3 3106.08    20.3 3104.49    29.2 3098.34    87.4 3066.67
   107.7 3052.95   141.2 3026.02   154.6 3024.71     177 3026.02   208.3 3025.91
   269.2 3023.89   275.4 3024.12   295.4 3029.08   311.2  3031.3   319.9 3029.99
   332.9 3025.66   371.6 3023.59   376.2 3022.39   389.9 3022.35  395.07  3023.7
   402.1 3027.56   432.4 3036.68   472.6 3041.92   739.8 3056.41   772.7 3056.18
   781.8 3058.93   796.1 3060.06   833.9  3060.1   843.7 3063.65   909.7 3065.14
#Mann= 7 ,-1,0
       0      .1       0   371.6    .045       0  395.07      .1       0
  489.92     .05       0  589.92     .07       0  699.92     .06       0
  809.92      .1       0
Bank Sta=371.6,395.07
XS Rating Curve= 0 ,0
Exp/Cntr=0.3,0.1

Type RM Length L Ch R = 1 ,68826   ,487.2,485.4,482.3
XS GIS Cut Line= 4
2227594.24485425486079.3175570062227825.47468719486099.985444085
2228200.94775499485937.8869390432228399.75826118485776.682017321
#Sta/Elev= 30
       0 3144.69      14 3135.59    29.3 3128.27    58.2 3109.32    70.2 3104.57
   110.3 3081.77   134.5 3069.87   191.5 3049.56   222.8  3040.2   291.7 3027.08
   335.3 3020.42     344 3017.37   352.7 3016.84   361.4 3014.51   374.5 3014.39
   378.9 3014.63   382.4 3016.74   387.6 3019.25   400.6 3021.25   485.9 3019.22
   500.9  3021.9   589.3 3022.05   609.8    3025   631.9 3031.33   654.9 3034.31
   672.4 3034.71     841 3049.13   857.2 3051.95   874.3 3060.77   897.1 3061.65
#Mann= 4 ,-1,0
       0      .1       0   352.7    .045       0   382.4      .1       0
  891.12     .06       0
#XS Ineff= 2 , 0
                           507.6         3025.42
Permanent Ineff=
       F       F
Bank Sta=352.7,382.4
XS Rating Curve= 0 ,0
Exp/Cntr=0.3,0.1

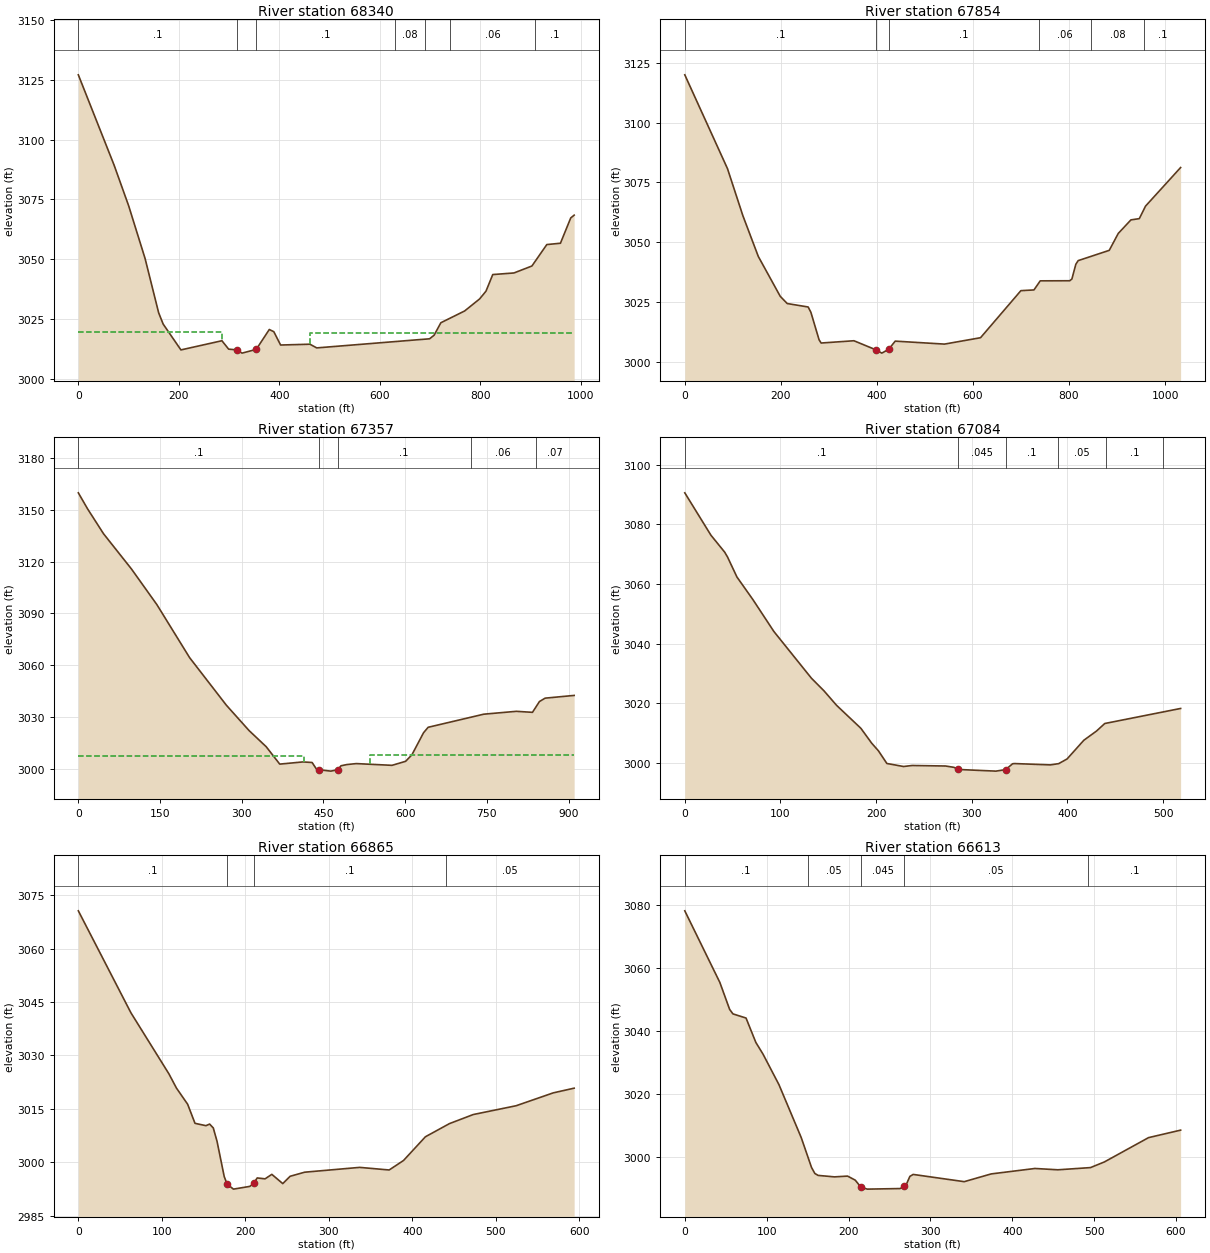
Type RM Length L Ch R = 1 ,68340   ,492,486.4,475.7
XS GIS Cut Line= 3
2227837.79377921486645.6240750392228487.10123838486313.360006845
2228716.52650071486196.299614723
#Sta/Elev= 30
       0    3127    71.2 3089.32   100.2 3072.34     133 3050.26   159.9  3027.7
   168.9 3022.99   204.2 3012.22   285.8 3016.05   299.2 3012.54  315.06 3012.24
   325.9 3010.88   354.1 3012.44   380.1 3020.74   389.1 3019.82   402.6 3014.26
     461  3014.6   474.5 3013.06   699.1 3016.86   708.1 3018.34   721.6 3023.56
     769 3028.48   798.7 3033.49   811.4 3036.73   824.9 3043.66   867.1 3044.33
   902.8 3047.23   932.5 3056.18   959.6 3056.73   980.1 3067.29   986.9 3068.45
#Mann= 7 ,-1,0
       0      .1       0  315.06    .045       0   354.1      .1       0
     630     .08       0     690      .1       0  739.38     .06       0
  909.38      .1       0
#XS Ineff= 2 , 0
          285.84 3019.62  461.63          3019.1
Permanent Ineff=
       F       F
Bank Sta=315.06,354.1
XS Rating Curve= 0 ,0
Exp/Cntr=0.3,0.1

Type RM Length L Ch R = 1 ,67854   ,486.7,497.1,506.2
XS GIS Cut Line= 4
 2228098.6115974487085.8584776372228311.77020231486966.716226147
 2228665.7404072486668.9842781112228962.49243433486534.861269842
#Sta/Elev= 30
       0 3119.94    88.9 3080.75   120.9 3061.13     153  3044.1   198.8 3027.41
   213.3 3024.41   256.9 3022.97   262.6 3020.73   279.6 3009.27   283.9 3007.92
   352.2 3008.87   398.9    3005   410.2  3003.7   424.4 3005.26   438.1 3008.71
   540.8 3007.47   615.8 3010.14   699.8 3029.79     727 3030.09   740.1 3033.89
   801.6 3033.93     806 3034.66   814.2 3040.81   819.1 3042.34   883.8 3046.63
   902.5 3053.68   928.9 3059.35   946.4 3059.88   959.3 3065.09  1032.4 3081.22
#Mann= 6 ,-1,0
       0      .1       0   398.9    .045       0   424.4      .1       0
  736.73     .06       0  846.73     .08       0  956.73      .1       0
Bank Sta=398.9,424.4
XS Rating Curve= 0 ,0
Exp/Cntr=0.3,0.1

Type RM Length L Ch R = 1 ,67357   ,273.1,273.1,267.9
XS GIS Cut Line= 2
     2228204.671      487463.514     2229060.047      487152.752
#Sta/Elev= 30
       0 3159.94      17 3150.63    46.3 3136.19    97.4 3115.81   144.2 3095.08
   204.3 3064.31   271.8 3036.71   313.6 3021.97   344.8 3012.67   369.7 3002.57
   412.3 3003.84   429.1  3003.5   437.8 2999.35   442.1  2999.3   463.4  2998.5
   476.1 2999.32   482.2 3001.61   493.1 3002.32   510.2 3002.87   575.8 3001.86
   600.8  3004.2   612.3 3007.97   633.6 3020.74   642.1 3023.93   744.2 3031.53
   803.8 3033.19   833.6 3032.61   846.4 3038.87   856.8 3040.83   910.1 3042.42
#Mann= 5 ,-1,0
       0      .1       0   442.1    .045       0   476.1      .1       0
     720     .06       0     840     .07       0
#XS Ineff= 2 , 0
          414.72 3007.54  534.85         3007.61
Permanent Ineff=
       F       F
Bank Sta=442.1,476.1
XS Rating Curve= 0 ,0
Exp/Cntr=0.3,0.1

Type RM Length L Ch R = 1 ,67084   ,226.5,218.7,226.6
XS GIS Cut Line= 2
2228435.28490426487691.4392655052228908.55002471487479.816650672
#Sta/Elev= 30
       0 3090.62    27.3 3076.41    41.7 3070.71    44.7 3069.07    54.5 3062.38
    71.1 3054.84    93.2 3044.06   132.4  3028.4   145.6 3024.14   158.7  3019.3
   184.1 3011.59   195.4  3006.6   202.5 3004.02   211.3 2999.78   228.8 2998.77
   237.6 2999.11   272.6 2998.94   281.4 2998.49   285.8 2997.78   325.2 2997.22
   335.4 2997.72   342.7 2999.68   344.5 2999.76   382.2 2999.31   390.9 2999.73
   399.7 3001.31   417.2 3007.58   430.4 3010.66   439.1  3013.2   518.4 3018.25
#Mann= 6 ,-1,0
       0      .1       0   285.8    .045       0   335.4      .1       0
     390     .05       0     440      .1       0     500     .06       0
Bank Sta=285.8,335.4
XS Rating Curve= 0 ,0
Exp/Cntr(USF)=0,0
Exp/Cntr=0.3,0.1

Type RM Length L Ch R = 1 ,66865   ,237.3,252.4,273.1
XS GIS Cut Line= 3
2228524.59696565487860.8364036972228927.08289492487681.272901435
2229046.41469289487585.572942531
#Sta/Elev= 30
       0 3070.62      63 3041.96   108.5  3024.8   117.5 3020.81   130.9 3016.27
   139.7 3010.91   152.8 3010.25   157.2  3010.7   161.6 3009.61   166.1 3005.84
   174.7 2995.94   178.1 2993.85   185.7 2992.42   205.4 2993.19   209.8 2994.04
   214.2 2995.56   223.6 2995.31   231.7 2996.57   244.8 2993.97   253.6 2996.03
   271.1 2997.18   336.8 2998.53   372.2  2997.8   389.4 3000.47   415.6 3007.13
   444.4 3010.83   472.9 3013.38   524.2 3015.85   568.7 3019.47   593.7 3020.79
#Mann= 4 ,-1,0
       0      .1       0   178.1    .045       0   209.8      .1       0
     440     .05       0
Bank Sta=178.1,209.8
XS Rating Curve= 0 ,0
Exp/Cntr=0.3,0.1

Type RM Length L Ch R = 1 ,66613   ,254.7,264.7,280
XS GIS Cut Line= 4
2228549.43286014488009.5144684052228846.98708221488018.492397519
2228953.43967028487953.0817711162229071.43531006487813.282589196
#Sta/Elev= 30
       0  3078.1    42.8 3055.36    54.8 3046.77    58.8 3045.36    74.8 3044.04
    86.8 3036.28    95.6 3032.55     115 3022.88   142.2 3006.07   154.8 2996.57
   158.8 2994.68   162.8 2994.05   182.8 2993.58   198.8 2993.83   208.2 2992.54
   214.8  2990.4   222.8 2989.69   262.9 2989.87  268.13 2990.55   270.9 2991.37
   274.9 2993.73   278.9 2994.36   341.3 2992.06   374.2 2994.52   427.7 2996.25
   455.7 2995.83   495.5 2996.53   512.5 2998.33   566.4 3006.05   605.6 3008.43
#Mann= 5 ,-1,0
       0      .1       0     150     .05       0   214.8    .045       0
  268.13     .05       0  492.63      .1       0
Bank Sta=214.8,268.13
XS Rating Curve= 0 ,0
Exp/Cntr(USF)=0,0
Exp/Cntr=0.3,0.1

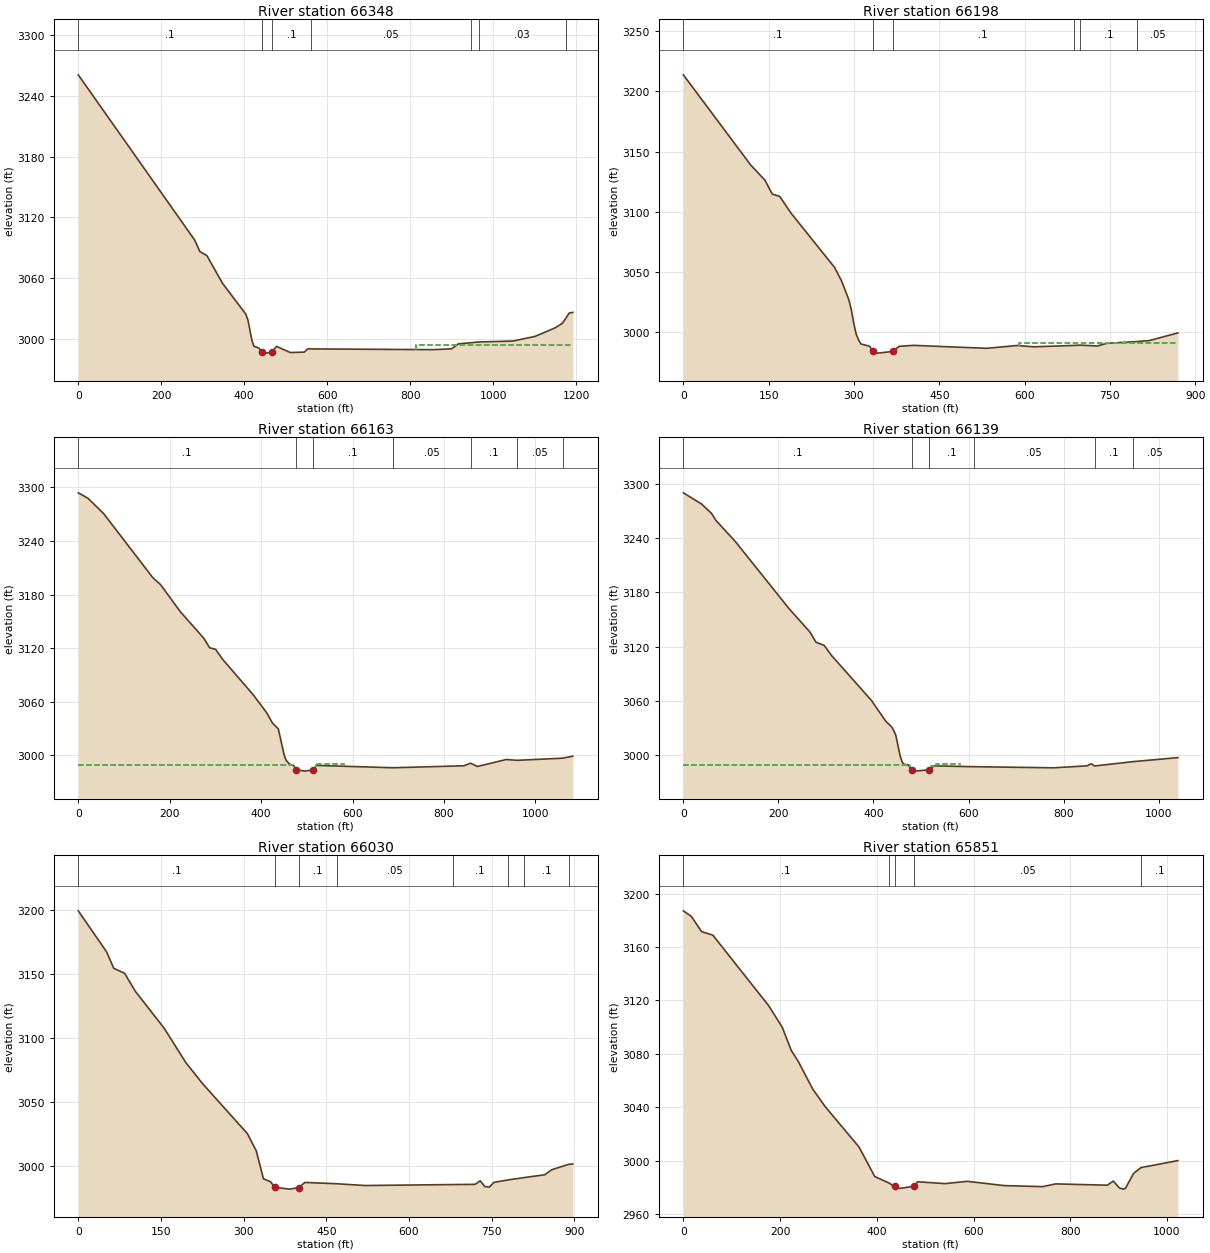
Type RM Length L Ch R = 1 ,66348   ,149.3,149.8,150.8
XS GIS Cut Line= 3
     2228260.511       488127.632229056.30520941488378.882274222
2229404.87725341488459.707146464
#Sta/Elev= 30
       0 3260.87   280.7 3097.48   293.3 3086.09   310.1 3082.16   347.8 3054.75
   403.7 3024.46     409 3018.64   418.6 2998.35   423.3 2992.62   435.9 2990.63
  442.03 2986.99   452.7 2985.75  467.46 2986.99   477.8 2992.44   511.1 2986.35
   544.9 2986.74   553.3 2990.01   561.7 2989.92   854.9 2989.18   900.1 2990.02
   916.3 2994.88   946.3 2996.02   964.9 2996.76  1047.9  2997.7  1101.3  3002.3
  1150.6 3010.91    1167  3015.2  1175.2 3020.14  1183.4 3025.35  1192.3 3026.05
#Mann= 7 ,-1,0
       0      .1       0  442.03    .045       0  467.46      .1       0
   561.7     .05       0   946.3     .06       0   964.9     .03       0
  1175.2      .1       0
#XS Ineff= 2 , 0
                           814.9            2994
Permanent Ineff=
       F       F
Bank Sta=442.03,467.46
XS Rating Curve= 0 ,0
Exp/Cntr=0.3,0.1

Type RM Length L Ch R = 1 ,66198   ,36.1,35.3,34.3
BEGIN DESCRIPTION:
xs 4
END DESCRIPTION:
XS GIS Cut Line= 3
2228323.86359274488299.345872736 2228698.7934556488423.699168896
2229156.93717829488548.052465055
#Sta/Elev= 30
       0 3213.79   118.3 3138.88   143.6 3126.13   156.3 3114.65   169.4 3112.71
     190 3098.41   265.8 3053.73   278.5 3042.15   291.1 3026.68   295.3 3018.57
   299.5 3007.59   303.8  2998.4     308  2993.5   312.2 2990.02   327.7 2988.12
   333.3 2983.81   341.7  2982.4     3682983.786   379.6 2988.06   404.7 2988.86
   533.2 2986.41   587.1 2988.74   616.1 2987.65   686.6 2988.78   697.3 2989.06
     728 2988.34   744.6 2990.54   797.7 2992.03   819.2 2992.82   869.7  2999.2
#Mann= 6 ,-1,0
       0      .1       0   333.3    .045       0     368      .1       0
   686.6     .05       0   697.3      .1       0   797.7     .05       0
#XS Ineff= 2 , 0
                           590.6         2991.23
Permanent Ineff=
       F       F
Bank Sta=333.3,368
XS Rating Curve= 0 ,0
Exp/Cntr(USF)=0,0
Exp/Cntr=0.5,0.3

Type RM Length L Ch R = 1 ,66163   ,22.7,23.4,24.2
BEGIN DESCRIPTION:
xs 3
END DESCRIPTION:
XS GIS Cut Line= 4
2228184.30393787 488268.500871632228592.05600662488427.088157658
2228803.16559852488490.389646317 2229207.0725087488618.669094183
#Sta/Elev= 30
       0 3294.03    21.3 3287.92    55.7 3270.63     163 3199.05   180.1 3191.18
     223 3161.03   274.5 3131.23   287.4 3120.44   300.3 3118.79   315.6 3107.62
   381.8 3068.38   411.9 3047.84   424.8 3036.17   437.6 3029.54   450.2  3000.7
   454.3 2994.71   461.8 2990.25     471 2988.76   476.52983.821   496.1 2982.33
   512.8 2983.86   521.1 2988.72   688.3 2986.11   843.6 2988.32   858.1 2991.19
     873 2987.55     936 2995.33   960.3 2994.43  1059.1 2996.82  1081.7 2999.04
#Mann= 7 ,-1,0
       0      .1       0   476.5    .045       0   512.8      .1       0
   688.3     .05       0   858.1      .1       0   960.3     .05       0
  1059.1     .03       0
#XS Ineff= 3 ,-1
       0     470 2989.74     519  522.99 2988.99  522.99   581.4 2990.85
Permanent Ineff=
       F       F       F
Bank Sta=476.5,512.8
XS Rating Curve= 0 ,0
Exp/Cntr(USF)=0,0
Exp/Cntr=0.5,0.3

Type RM Length L Ch R = 1 ,66139   ,110.6,109.9,109.3
BEGIN DESCRIPTION:
xs 2
END DESCRIPTION:
XS GIS Cut Line= 4
2228177.15906894488282.3219599752228607.72657441488455.444423183
2228722.64407154488492.7552988752229158.50880011488625.759102248
#Sta/Elev= 30
       0 3289.88    38.3 3277.55    59.3 3267.13    69.1 3259.05   109.1 3236.21
   222.8 3161.59   265.9 3136.35   279.2 3124.75   296.4 3121.18     312 3109.96
   395.6  3060.5   425.8 3037.52   438.7 3030.92     443 3026.84   447.3 3021.38
   455.9 2999.65   460.2 2992.48   464.5 2989.73     473 2989.26   480.7 2983.69
   485.6 2982.26  517.27  2983.7   527.6 2988.05   610.6 2987.15   778.9 2985.93
   849.2  2988.1   858.3 2990.41   865.2 2987.95   945.3 2992.71  1040.6 2997.19
#Mann= 6 ,-1,0
       0      .1       0   480.7    .045       0  517.27      .1       0
   610.6     .05       0   865.2      .1       0   945.3     .05       0
#XS Ineff= 3 ,-1
       0  476.01  2989.5  521.15  532.33  2988.3  532.33  582.88 2989.62
Permanent Ineff=
       F       F       F
Bank Sta=480.7,517.27
XS Rating Curve= 0 ,0
Exp/Cntr(USF)=0,0
Exp/Cntr=0.5,0.3

Type RM Length L Ch R = 1 ,66030   ,169.8,179,187.3
BEGIN DESCRIPTION:
xs 1
END DESCRIPTION:
XS GIS Cut Line= 3
2228252.80456636488432.114053598 2228499.6411843488537.767605974
2229100.83794694488721.960082241
#Sta/Elev= 30
       0 3199.41    51.5 3167.26    64.3 3154.48      84 3150.57   103.9 3136.24
     156 3107.47   195.3 3080.59   225.8 3064.09   306.7 3025.19   322.9 3011.69
     336 2989.76   348.6 2987.51   356.9 2983.07   383.7 2981.68   399.8 2982.89
   411.3 2986.93   469.2 2985.88   520.1 2984.51     679 2985.25     720 2985.42
   729.2 2988.22   737.6 2983.72   745.6 2983.21   754.3 2986.97   779.4 2988.85
   808.7 2990.69   846.4 2992.92   858.9 2996.85   889.7 3001.06   897.3  3001.4
#Mann= 8 ,-1,0
       0      .1       0   356.9    .045       0   399.8      .1       0
   469.2     .05       0     679      .1       0   779.4     .05       0
   808.7      .1       0   889.7     .05       0
Bank Sta=356.9,399.8
XS Rating Curve= 0 ,0
Exp/Cntr(USF)=0,0
Exp/Cntr=0.3,0.1

Type RM Length L Ch R = 1 ,65851   ,344.8,344.9,343.7
XS GIS Cut Line= 3
     2228140.901       488497.762228651.91398156488804.945819884
2229059.98486483488928.588826236
#Sta/Elev= 30
       0 3187.05    16.5 3182.93    37.7 3171.47      61 3168.84   176.9 3115.83
   204.5 3099.92   223.2 3082.53   238.1 3074.03   267.2 3053.83   293.2 3040.51
   363.2 3010.28   395.9 2988.12   424.6 2983.42  436.63 2980.82   447.2  2979.3
   476.5 2980.78   484.5 2984.24   541.2 2982.86   587.2 2984.59   663.4 2981.38
   742.8  2980.6   769.8 2982.65   876.5 2981.69   889.1 2984.76   901.6 2979.63
     910 2978.74   914.2  2979.4   930.9 2990.48   946.3 2994.87  1022.6 3000.11
#Mann= 5 ,-1,0
       0      .1       0   424.6     .05       0  436.63    .045       0
   476.5     .05       0   946.3      .1       0
Bank Sta=436.63,476.5
XS Rating Curve= 0 ,0
Exp/Cntr=0.3,0.1

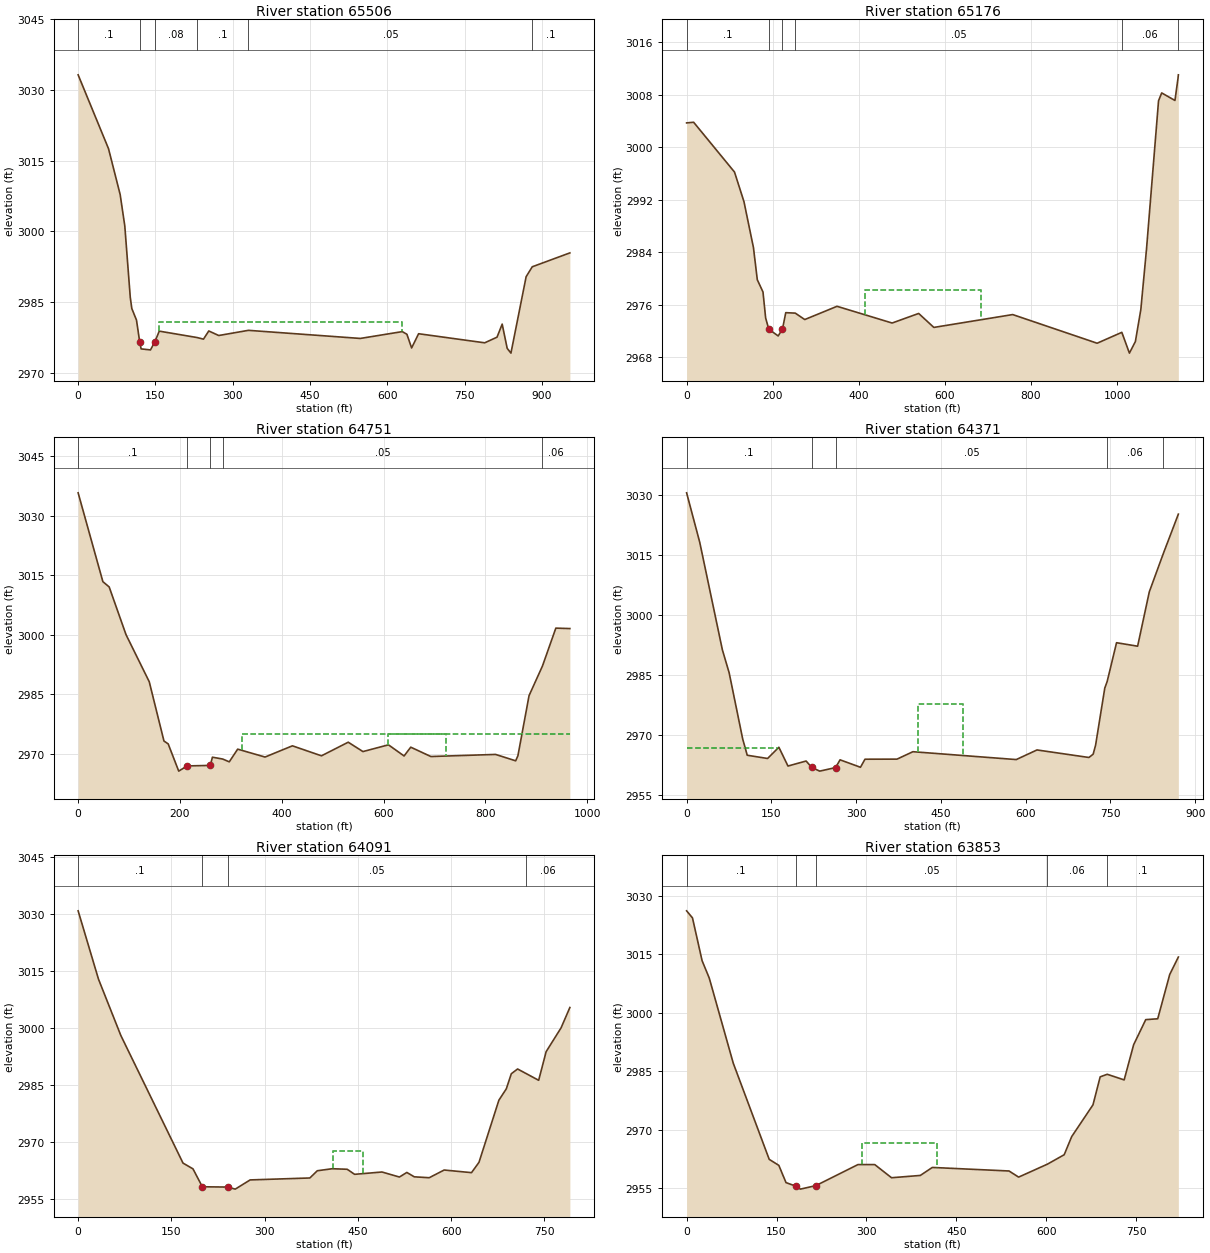
Type RM Length L Ch R = 1 ,65506   ,331,329.5,327.8
XS GIS Cut Line= 3
2228200.07108004488936.4410633132228802.15747086489255.077692225
 2229060.1944955 489165.15569879
#Sta/Elev= 30
       0 3033.23      59 3017.54    81.6  3007.8    90.6 3001.13   101.2 2985.99
   104.2 2983.59   113.3 2981.13  119.67 2976.39   122.3 2975.02   140.4  2974.8
   148.6 2976.45   157.5 2978.79   230.9 2977.43   243.3 2977.09   253.6 2978.83
   272.9 2977.86   330.5 2978.96   547.7 2977.24   629.2 2978.69   638.2 2978.12
   647.3 2975.22   660.9 2978.24   789.2 2976.31   813.1 2977.51   823.1 2980.28
   832.8 2975.14   840.1 2974.12   869.6 2990.36   881.5 2992.46   954.5 2995.41
#Mann= 6 ,-1,0
       0      .1       0  119.67    .045       0   148.6     .08       0
   230.9      .1       0   330.5     .05       0   881.5      .1       0
#XS Ineff= 1 ,-1
   157.4  628.722980.683
Permanent Ineff=
       F
Bank Sta=119.67,148.6
XS Rating Curve= 0 ,0
Exp/Cntr(USF)=0,0
Exp/Cntr=0.3,0.1

Type RM Length L Ch R = 1 ,65176   ,443.4,425.1,401.7
XS GIS Cut Line= 2
2227975.26609645 489202.29739173 2229011.3238469489683.184574013
#Sta/Elev= 30
       0 3003.72    16.3 3003.82   111.3 2996.22   133.3 2991.69   155.3 2984.69
   164.2  2979.8   177.4 2977.94   183.6 2973.96  190.95 2972.25   212.7 2971.23
   222.7 2972.28   230.3 2974.78   252.4 2974.71   274.4 2973.73   349.4 2975.75
   477.3  2973.2     539 2974.66   574.3 2972.53   757.4 2974.49   953.5 2970.12
  1010.9 2971.78  1028.5 2968.61  1042.4 2970.38    1055 2975.24  1068.2 2984.46
  1096.2  3007.1  1103.5 3008.29  1134.3 3007.14  1141.4 3010.53  1142.2 3011.05
#Mann= 6 ,-1,0
       0      .1       0  190.95    .045       0   222.7      .1       0
   252.4     .05       0  1010.9     .06       0  1141.4      .1       0
#XS Ineff= 1 ,-1
   415.4   684.22978.171
Permanent Ineff=
       F
Bank Sta=190.95,222.7
XS Rating Curve= 0 ,0
Exp/Cntr(USF)=0,0
Exp/Cntr=0.3,0.1

Type RM Length L Ch R = 1 ,64751   ,373,379.7,387.1
XS GIS Cut Line= 3
2228033.16804092489717.7849932262228440.10415773489610.113180217
2228937.29458839489833.373851309
#Sta/Elev= 30
       0  3035.8    48.6 3013.41      61 3012.07    94.1 3000.04   139.7 2988.18
   168.6 2973.23   176.9 2972.51   197.6 2965.64   214.1 2966.95   259.6 2967.08
   263.8 2969.15   283.9 2968.69   296.9 2967.98   313.4 2971.18   367.2 2969.19
   420.9 2972.02     478  2969.5   530.6 2972.93   559.5 2970.57   609.6 2972.27
   640.3 2969.46   653.4 2971.68   692.9 2969.32     820 2969.85   859.5 2968.24
   863.9  2969.5   885.8 2984.67   912.1 2992.13   938.4 3001.69     966 3001.58
#Mann= 5 ,-1,0
       0      .1       0   214.1    .045       0   259.6      .1       0
   283.9     .05       0   912.1     .06       0
#XS Ineff= 2 ,-1
   321.7     293    2975   609.6   723.6    2975
Permanent Ineff=
       F       F
Bank Sta=214.1,259.6
XS Rating Curve= 0 ,0
Exp/Cntr(USF)=0,0
Exp/Cntr=0.3,0.1

Type RM Length L Ch R = 1 ,64371   ,278,280.4,283.4
XS GIS Cut Line= 4
2228068.83804059490038.7913415472228229.20812941490039.369431597
2228449.75031314490024.054002172 2228921.7644374490151.085691068
#Sta/Elev= 30
       0 3030.44    23.3 3018.08    63.3 2991.31    75.3 2985.58    99.3 2969.06
   107.3 2965.03   143.3 2964.22   163.3 2967.02   179.4 2962.34   211.5 2963.59
  221.422961.994   235.5 2961.07   263.6 2961.95   271.6 2963.89   307.7 2962.03
   315.7 2964.04   372.3 2964.06   400.5 2965.91   583.4 2963.95   620.1 2966.35
     712 2964.47   719.5 2965.29   723.8 2967.52   740.1 2981.79   744.3 2983.41
   760.9 2993.08   798.2 2992.21   818.9 3005.77   843.8 3015.35   870.3 3025.13
#Mann= 5 ,-1,0
       0      .1       0  221.42    .045       0   263.6     .05       0
   744.3     .06       0   843.8      .1       0
#XS Ineff= 2 ,-1
       0   159.3 2966.82   410.3  490.03 2977.76
Permanent Ineff=
       F       F
Bank Sta=221.42,263.6
XS Rating Curve= 0 ,0
Exp/Cntr=0.3,0.1

Type RM Length L Ch R = 1 ,64091   ,238,238,237.9
XS GIS Cut Line= 2
2228071.43899771490312.6166926522228862.35180062490315.466828879
#Sta/Elev= 30
       0 3030.73    32.7  3012.8    68.7 2997.97   168.7 2964.44   184.7 2962.93
  199.78 2958.22   240.4 2958.14   252.7  2957.6   276.7 2960.02   372.7 2960.53
   384.7 2962.43   408.7 2962.96   432.7 2962.82   444.7 2961.49   488.7  2962.1
   516.7 2960.78   528.7 2961.98   540.7 2960.83   564.7  2960.6   588.7 2962.62
   632.7 2961.93   644.7 2964.64   676.7 2980.96   688.7 2983.97   696.7 2987.92
   706.8 2989.17   740.7  2986.2   752.7 2993.72   776.7 2999.97   790.9 3005.33
#Mann= 4 ,-1,0
       0      .1       0  199.78    .045       0   240.4     .05       0
     720     .06       0
#XS Ineff= 1 ,-1
  410.63  458.47 2967.56
Permanent Ineff=
       F
Bank Sta=199.78,240.4
XS Rating Curve= 0 ,0
Exp/Cntr(USF)=0,0
Exp/Cntr=0.3,0.1

Type RM Length L Ch R = 1 ,63853   ,222.4,217.1,219.9
XS GIS Cut Line= 2
2228094.37632694490550.7395050362228914.58890798      490553.247
#Sta/Elev= 30
       0 3026.11     9.8  3024.3    25.8 3013.34    37.8 3008.86    77.8 2987.05
   137.8 2962.38   153.8 2960.85   165.8 2956.42   181.8 2955.53   189.8 2954.75
   215.6 2955.65   285.8 2961.04   313.8 2961.04   341.8 2957.67   389.8 2958.26
   409.8 2960.31   537.8  2959.4   553.8 2957.83   601.8 2961.15   629.8 2963.57
   642.3 2968.22   677.8 2976.36   689.8 2983.54   701.5  2984.2   729.8 2982.76
   745.6 2991.77   765.8 2998.21   785.8 2998.43   805.8 3009.79   820.2 3014.26
#Mann= 5 ,-1,0
       0      .1       0   181.8    .045       0   215.6     .05       0
   601.8     .06       0   701.5      .1       0
#XS Ineff= 1 ,-1
  292.36  416.94 2966.59
Permanent Ineff=
       F
Bank Sta=181.8,215.6
XS Rating Curve= 0 ,0
Exp/Cntr=0.3,0.1