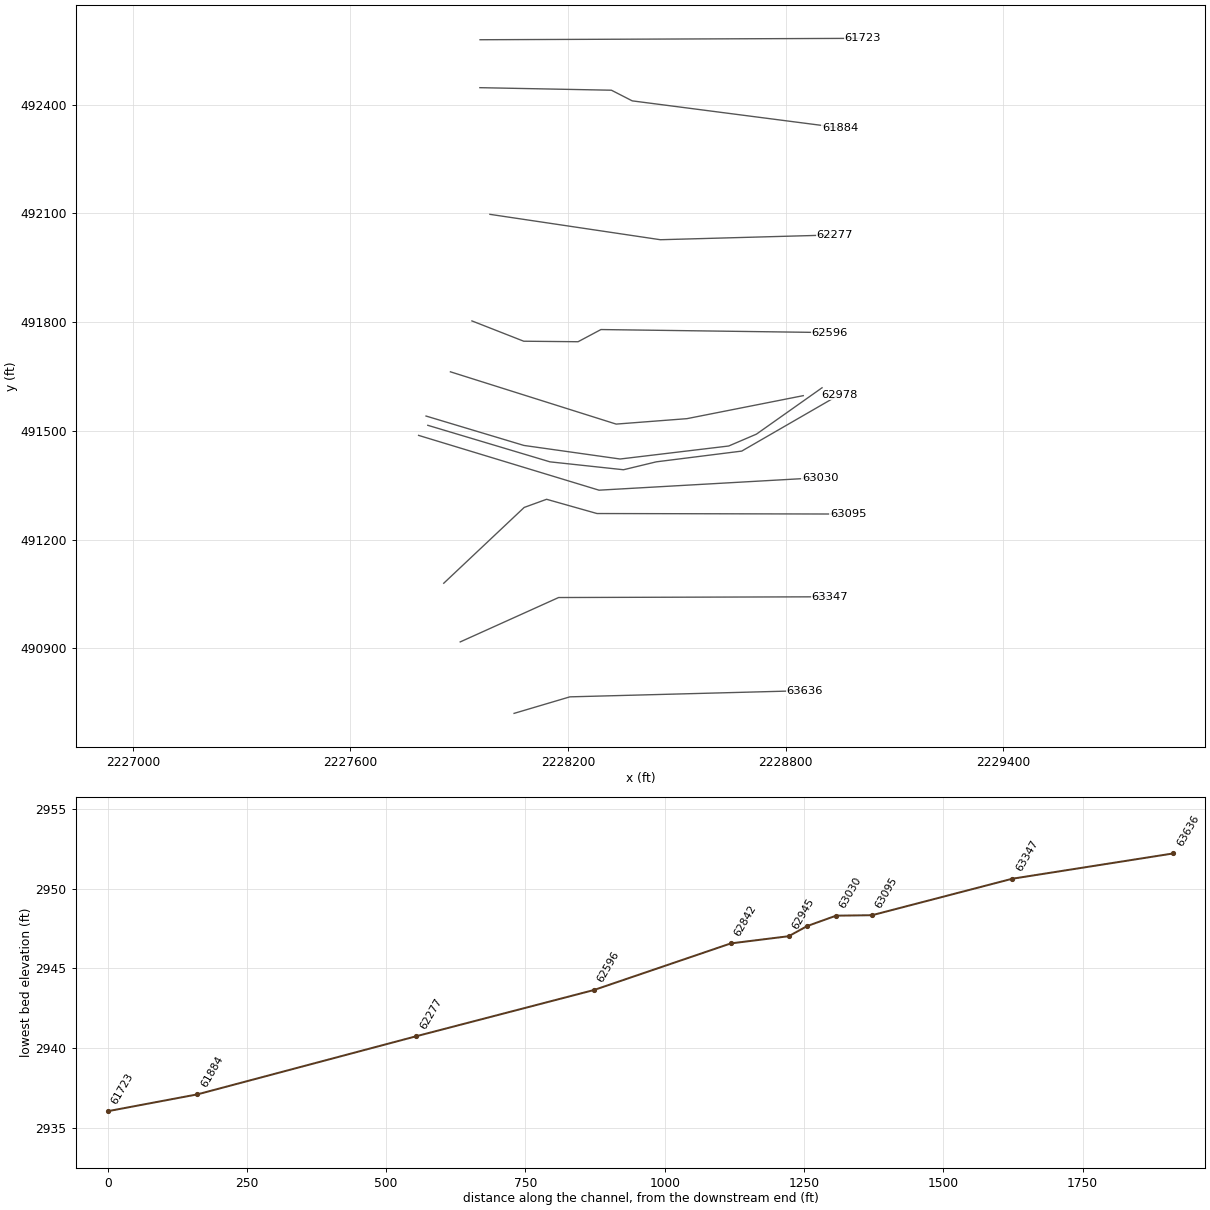
HEC-RAS study OLDFLDFK1.prj: OLDFLDFK1

--- OLDFLDFK1.g01 (geometry) --- (continued)

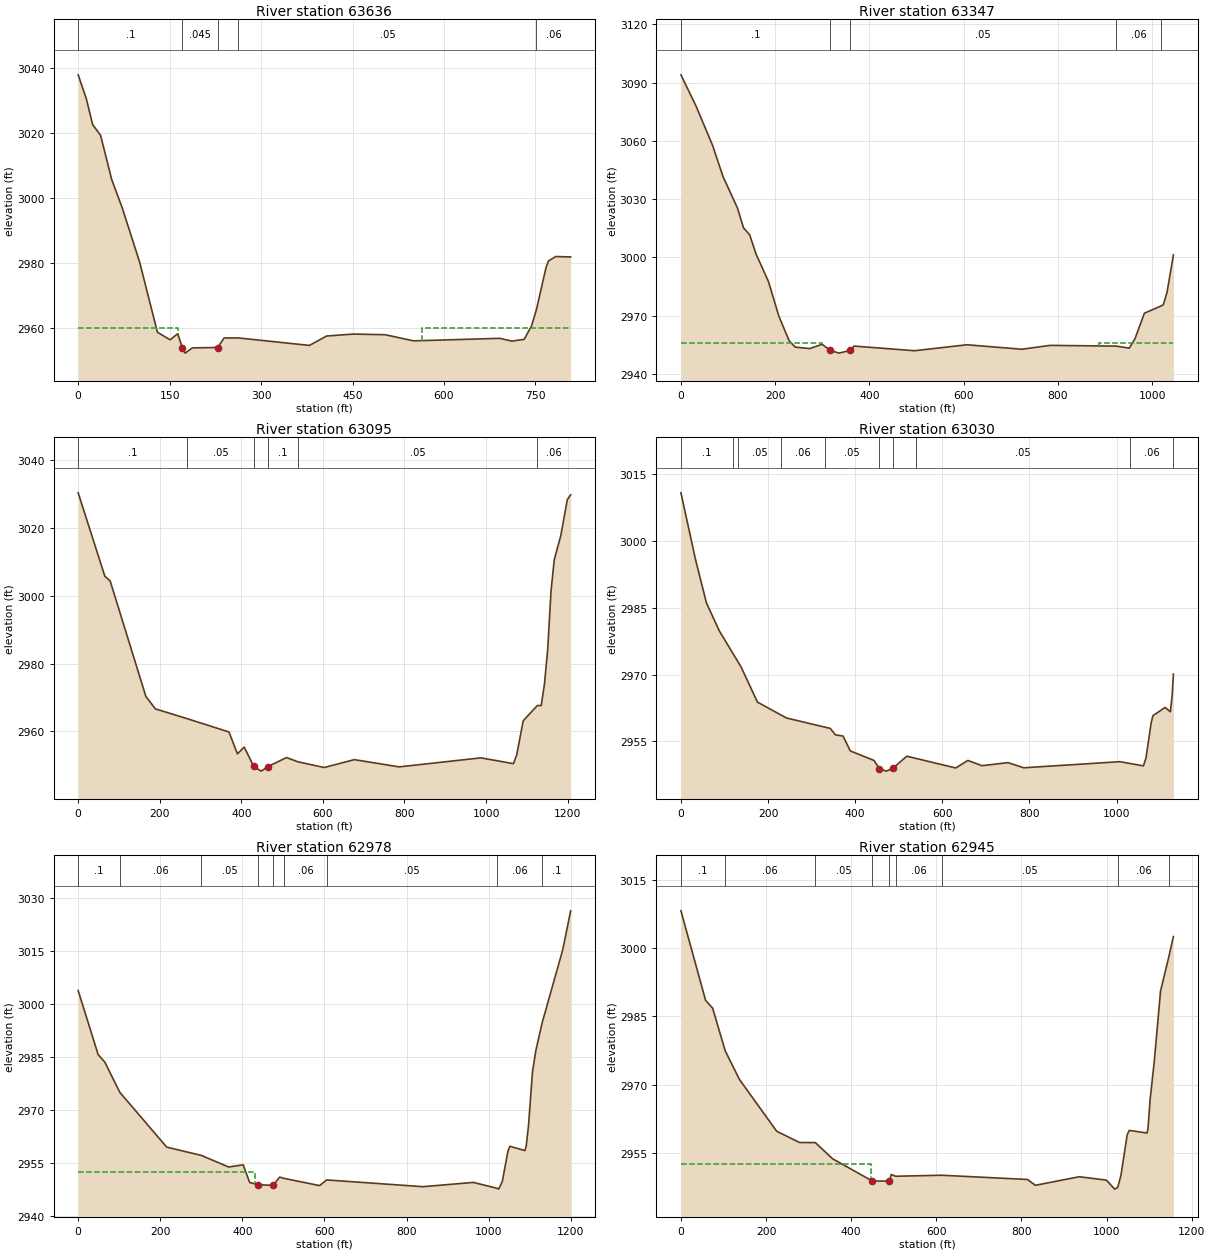
Type RM Length L Ch R = 1 ,63636   ,284.6,289.2,285.3
XS GIS Cut Line= 3
2228051.48804412490720.1861730712228205.39540037490765.788352698
2228852.37632383490782.889170058
#Sta/Elev= 30
       0 3037.77    13.2 3030.53    23.9 3022.43    36.8 3019.17      55 3005.59
    72.2  2996.9   100.8 2980.22     130 2958.64   150.9 2956.31   163.3 2958.21
  170.95 2953.83   175.3 2952.22   187.3 2953.83   228.9 2953.95   239.3 2956.88
   262.6 2956.89   379.4 2954.59   407.4 2957.48   451.4 2958.08   503.4 2957.88
   550.3 2955.99   691.5 2956.77   711.5 2955.92   731.5 2956.46   743.5 2960.56
   751.5 2965.52   767.5 2978.65   771.5 2980.59   783.5 2981.92   807.7 2981.78
#Mann= 5 ,-1,0
       0      .1       0  170.95    .045       0   228.9      .1       0
   262.6     .05       0   751.5     .06       0
#XS Ineff= 2 , 0
           163.3    2960   563.5            2960
Permanent Ineff=
       F       F
Bank Sta=170.95,228.9
XS Rating Curve= 0 ,0
Exp/Cntr(USF)=0,0
Exp/Cntr=0.3,0.1

Type RM Length L Ch R = 1 ,63347   ,260.6,251.7,242.7
XS GIS Cut Line= 3
2227902.95314863490917.4044903972228174.24012487491039.902763903
 2228921.7270101491041.950472194
#Sta/Elev= 30
       0 3093.99    32.1 3077.87    67.2  3057.6    89.1 3041.71   119.8 3025.46
     133 3015.08   145.9 3011.58   159.3 3001.72   185.7 2987.54   207.6 2969.84
   229.6 2956.99   242.7 2953.72   273.5 2952.97   299.6 2955.18   316.8 2952.07
   335.6 2950.63   358.5    2952   367.6 2954.27   495.6 2951.86   607.2 2954.94
   723.5 2952.63   783.5 2954.62   923.2 2954.25   951.6 2953.22   963.6 2958.03
   983.6  2971.2  1018.9 2974.91  1023.6  2975.5  1031.6 2981.87  1045.2 3001.22
#Mann= 5 ,-1,0
       0      .1       0   316.8    .045       0   358.5     .05       0
   923.2     .06       0  1018.9      .1       0
#XS Ineff= 2 , 0
           299.6    2956  886.44            2956
Permanent Ineff=
       F       F
Bank Sta=316.8,358.5
XS Rating Curve= 0 ,0
Exp/Cntr=0.3,0.1

Type RM Length L Ch R = 1 ,63095   ,65.6,64.7,64
XS GIS Cut Line= 5
2227857.50994835491079.3481382752228079.36405292 491288.56498372
2228141.14620862491311.0312221572228280.15605895491271.715304892
 2228972.3970308 491270.31116499
#Sta/Elev= 30
       0 3030.21    65.4 3005.69    78.5 3004.28   165.9 2970.35   189.2 2966.66
   267.6 2963.76   369.7 2959.86   390.5 2953.41   407.1 2955.42   430.4 2949.77
   448.7 2948.34   465.1 2949.68     511 2952.33   539.2 2951.07   603.2  2949.4
     677 2951.72   787.2 2949.59   987.2 2952.24  1067.2 2950.54  1075.2 2953.11
  1091.2 2963.17  1125.9 2967.65  1135.2  2967.6  1143.2 2973.93  1151.2 2984.21
  1159.2 3001.09  1167.2 3010.53  1183.2 3017.59  1199.2 3028.18  1207.4 3029.64
#Mann= 6 ,-1,0
       0      .1       0   267.6     .05       0   430.4    .045       0
   465.1      .1       0   539.2     .05       0  1125.9     .06       0
Bank Sta=430.4,465.1
XS Rating Curve= 0 ,0
Exp/Cntr(USF)=0,0
Exp/Cntr=0.3,0.1

Type RM Length L Ch R = 1 ,63030   ,47.1,51.7,57.3
BEGIN DESCRIPTION:
xs 4
END DESCRIPTION:
XS GIS Cut Line= 3
2227788.17160151491487.3880515282228285.67713056 491336.17407402
2228895.15026128491370.803229175
#Sta/Elev= 30
       0 3010.79    33.4 2995.84    58.5 2986.08    88.3 2979.76     138 2971.71
   175.6 2963.81   242.2 2960.24   342.8  2957.9   354.5 2956.45   372.1 2956.19
   388.8 2952.84   443.2 2950.71   455.7 2948.84   471.2 2948.31   485.9 2948.91
   518.4 2951.66   630.7 2949.02   658.7 2950.71   690.8 2949.53   750.8 2950.22
   786.9 2949.06  1007.3 2950.43  1061.6 2949.49  1067.4 2951.25  1079.4 2959.17
  1083.4 2960.76  1111.4 2962.61  1123.4 2961.64  1127.5 2965.23  1130.4  2970.1
#Mann= 10 ,-1,0
       0      .1       0     120     .06       0     130     .05       0
     230     .06       0     330     .05       0   455.7    .045       0
   485.9      .1       0  539.98     .05       0 1029.98     .06       0
 1129.98      .1       0
Bank Sta=455.7,485.9
XS Rating Curve= 0 ,0
Exp/Cntr(USF)=0,0
Exp/Cntr=0.5,0.3

Type RM Length L Ch R = 1 ,62978   ,34.2,33.4,32
BEGIN DESCRIPTION:
xs 3
END DESCRIPTION:
XS GIS Cut Line= 6
2227813.48822276491515.2214247192228150.37254586491414.399826133
2228353.19275397491392.557649874 2228443.6817699491414.399826133
 2228679.2652424491444.0427796262228948.91622409491599.818658839
#Sta/Elev= 30
       0 3003.83    48.7 2985.69    64.9 2983.59   101.4 2975.05   215.7 2959.54
     3002957.196   366.5 2953.92     402 2954.53   417.9 2949.53   438.3 2948.91
   474.7 2948.71   490.9 2951.06   502.2 2950.68   588.2 2948.66   605.4 2950.26
     840 2948.35   962.7 2949.56    10212947.882  1024.2 2947.66  1033.2  2949.8
    1047  2958.4  1051.6 2959.77  1088.4 2958.57  1091.6 2959.88  1097.3 2965.94
  1106.8 2980.89  1115.1 2986.93  1130.22994.646  1180.5 3015.36  1199.7 3026.36
#Mann= 9 ,-1,0
       0      .1       0   101.4     .06       0     300     .05       0
   438.3    .045       0   474.7     .05       0   502.2     .06       0
   605.4     .05       0    1021     .06       0  1130.2      .1       0
#XS Ineff= 2 , 0
             430 2952.64     490         2949.57
Permanent Ineff=
       F       F
Bank Sta=438.3,474.7
XS Rating Curve= 0 ,0
Exp/Cntr=0.5,0.3

Type RM Length L Ch R = 1 ,62945   ,109.2,103.7,99.5
BEGIN DESCRIPTION:
xs 2
END DESCRIPTION:
XS GIS Cut Line= 6
2227808.69850296491540.7724173412228078.60539529491459.644334096
2228343.83182129491422.2006033682228643.38166711491458.084178649
2228719.82928402491490.8474430372228900.80731587491618.780189692
#Sta/Elev= 30
       0 3008.15    57.9 2988.49    74.6 2986.74   103.9 2977.42   137.3 2971.13
     225 2959.73   278.7 2957.26   315.8 2957.24     356 2953.71  449.78 2948.79
   489.9  2948.8     494 2950.24   504.4 2949.85   612.7 2950.07   814.4 2949.14
   832.6 2947.86   935.8 2949.74   999.5    2949  1019.1 2947.02  1026.2  2947.4
  1033.8 2950.08  1048.4 2958.95  1053.3 2959.92  1095.1 2959.34  1097.4 2960.46
  1102.3  2966.7  1112.1 2975.17  1126.8 2990.55  1146.4 2998.12    1157 3002.49
#Mann= 9 ,-1,0
       0      .1       0   103.9     .06       0   315.8     .05       0
  449.78    .045       0   489.9     .05       0   504.4     .06       0
   612.7     .05       0  1026.2     .06       0  1146.4      .1       0
#XS Ineff= 2 , 0
             447  2952.6     493          2949.5
Permanent Ineff=
       F       F
Bank Sta=449.78,489.9
XS Rating Curve= 0 ,0
Exp/Cntr(USF)=0,0
Exp/Cntr=0.5,0.3

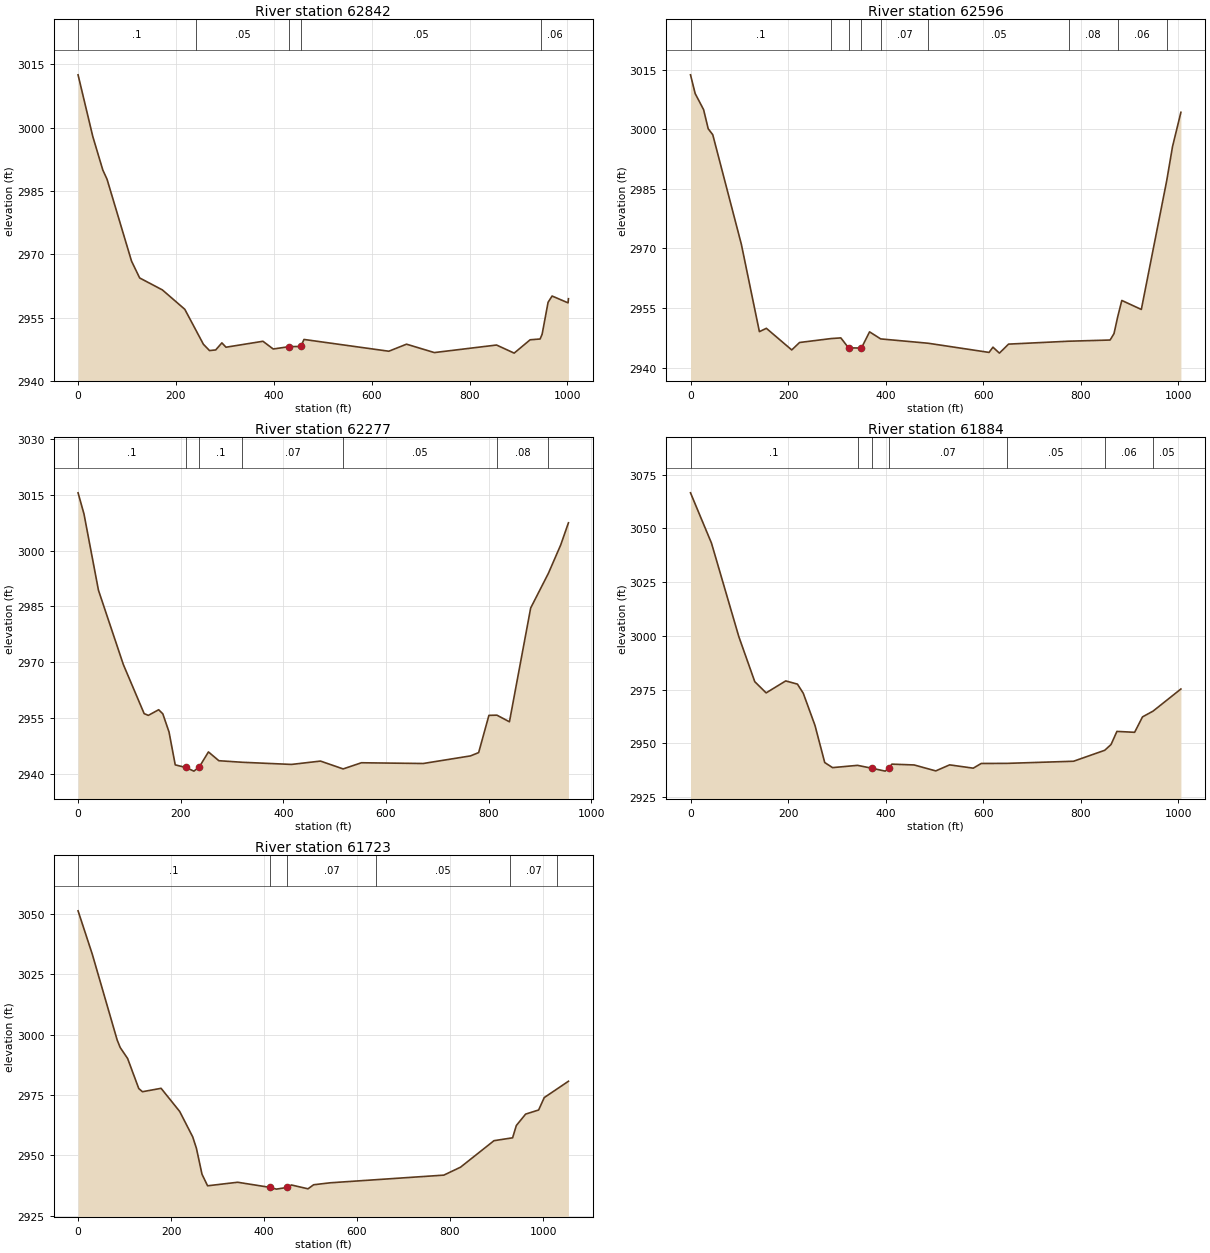
Type RM Length L Ch R = 1 ,62842   ,225.1,246,268.5
BEGIN DESCRIPTION:
xs 1
END DESCRIPTION:
XS GIS Cut Line= 4
2227875.89879457491662.842437644 2228333.0036426491518.554291167
2228528.08121664  491533.56025842228848.97805441 491597.04704285
#Sta/Elev= 30
       0 3012.51    30.2 2997.86    50.6 2989.95    59.2 2987.78   109.3 2968.36
   125.9 2964.38   172.3 2961.55   218.1 2956.96   256.2 2948.66   268.7 2947.17
   281.3 2947.33   293.9    2949   302.3 2947.97   377.8 2949.38   398.8 2947.55
  431.82 2948.11  455.19 2948.15   461.7 2949.81     635 2947.02   671.2 2948.69
   728.1  2946.7   855.2 2948.49   891.2 2946.57   923.8 2949.73   944.2 2949.92
   948.3 2951.05   960.5 2958.62   968.7  2960.1  1001.3 2958.48  1002.1 2959.46
#Mann= 5 ,-1,0
       0      .1       0     240     .05       0  431.82    .045       0
  455.19     .05       0  944.99     .06       0
Bank Sta=431.82,455.19
XS Rating Curve= 0 ,0
Exp/Cntr(USF)=0,0
Exp/Cntr=0.3,0.1

Type RM Length L Ch R = 1 ,62596   ,335.4,318.7,299.2
XS GIS Cut Line= 5
 2227935.2589646491803.3002745992228078.11893729491747.276755895
2228227.98184983491745.8761679272228291.00830837 491779.49027915
2228921.27289379491771.086751344
#Sta/Elev= 30
       0 3013.75     9.6 3009.02    26.8 3004.99    36.3 3000.16    45.6 2998.67
   104.2 2971.07   141.2 2949.05   155.5 2949.89   207.5 2944.44   223.5 2946.32
   287.5  2947.3   308.1 2947.48  323.92 2944.97   350.3 2944.92     367    2949
   389.8 2947.22   487.1 2946.13   611.9 2943.82   619.9 2945.14   633.1 2943.64
   651.9 2945.91     775 2946.64     860 2946.94     868 2948.56   875.6 2952.79
     884 2956.91     924 2954.64     976 2987.06     988 2995.71  1005.1 3004.31
#Mann= 9 ,-1,0
       0      .1       0   287.5     .05       0  323.92    .045       0
   350.3     .05       0   389.8     .07       0   487.1     .05       0
     775     .08       0   875.6     .06       0     976      .1       0
Bank Sta=323.92,350.3
XS Rating Curve= 0 ,0
Exp/Cntr(USF)=0,0
Exp/Cntr=0.3,0.1

Type RM Length L Ch R = 1 ,62277   ,398.7,392.9,382.7
XS GIS Cut Line= 3
2227984.81613043492097.4502826072228454.87710058492027.394349415
2228935.18947775 492040.64669919
#Sta/Elev= 30
       0 3015.54    11.5 3009.89    39.8 2989.34    88.3 2969.37   128.8  2956.2
   136.9 2955.72   157.1 2957.24   165.2 2956.14   177.3 2951.25   189.4 2942.42
   209.6 2941.73   225.8 2940.74  236.35 2941.88   254.1  2945.9   274.4 2943.54
     320 2943.12   415.9 2942.54   472.5 2943.44   516.6 2941.33   552.2 2942.99
   672.6 2942.79   764.7 2944.83   780.7 2945.72   800.7 2955.73   816.3 2955.78
   840.7    2954   882.1 2984.59   916.7 2993.93   940.7 3001.56   955.7 3007.49
#Mann= 7 ,-1,0
       0      .1       0   209.6    .045       0  236.35      .1       0
     320     .07       0   516.6     .05       0   816.3     .08       0
   916.7      .1       0
Bank Sta=209.6,236.35
XS Rating Curve= 0 ,0
Exp/Cntr=0.3,0.1

Type RM Length L Ch R = 1 ,61884   ,147.8,161.2,176.4
XS GIS Cut Line= 4
2227957.15924202492447.0308697112228319.91152563492440.027929873
 2228377.3356323492410.6155825532228950.17611105 492336.38442027
#Sta/Elev= 30
       0  3066.6      43 3043.19      99 2999.69   131.7 2978.72     155  2973.5
   195.1 2979.07   219.1 2977.59   231.1 2973.33   255.1 2958.37   275.1 2941.08
   291.1 2938.72   342.3 2939.78   371.1 2938.46   399.1 2937.09   406.7 2938.54
   412.6 2940.34   458.4 2939.96   502.6 2937.19     531    2940   579.4 2938.47
   595.8 2940.65     649  2940.7   785.1 2941.69   848.9 2946.79   861.8 2949.46
   873.9 2955.57   910.2 2955.16   926.3 2962.33     948 2965.02    1005 2975.31
#Mann= 7 ,-1,0
       0      .1       0   342.3     .07       0   371.1    .045       0
   406.7     .07       0     649     .05       0   848.9     .06       0
     948     .05       0
Bank Sta=371.1,406.7
XS Rating Curve= 0 ,0
Exp/Cntr(USF)=0,0
Exp/Cntr=0.3,0.1

Type RM Length L Ch R = 1 ,61723   ,170.1,185.2,200.3
XS GIS Cut Line= 2
2227957.58893438 492579.336622872229012.28713733492583.192923429
#Sta/Elev= 30
       0 3051.36    30.6 3033.38    84.1 2997.83    90.6 2994.73   106.6 2990.16
   130.6  2977.7   138.6  2976.4   178.6 2977.81   218.6 2968.21   246.6 2957.68
   254.6 2952.93   266.6 2942.18   278.6 2937.41   343.2 2938.88  412.87 2936.75
   426.6 2936.03   450.4 2936.76   458.8 2937.75   494.6 2936.16   506.6 2937.84
   542.7 2938.66   786.6 2941.83   822.6 2945.12   894.6 2956.11   934.6  2957.3
   942.6 2962.39   962.6 2967.12   990.6 2968.83  1002.6 2973.96  1054.7 2980.73
#Mann= 6 ,-1,0
       0      .1       0  412.87    .045       0   450.4     .07       0
     640     .05       0     930     .07       0    1030     .05       0
Bank Sta=412.87,450.4
XS Rating Curve= 0 ,0
Exp/Cntr(USF)=0,0
Exp/Cntr=0.3,0.1