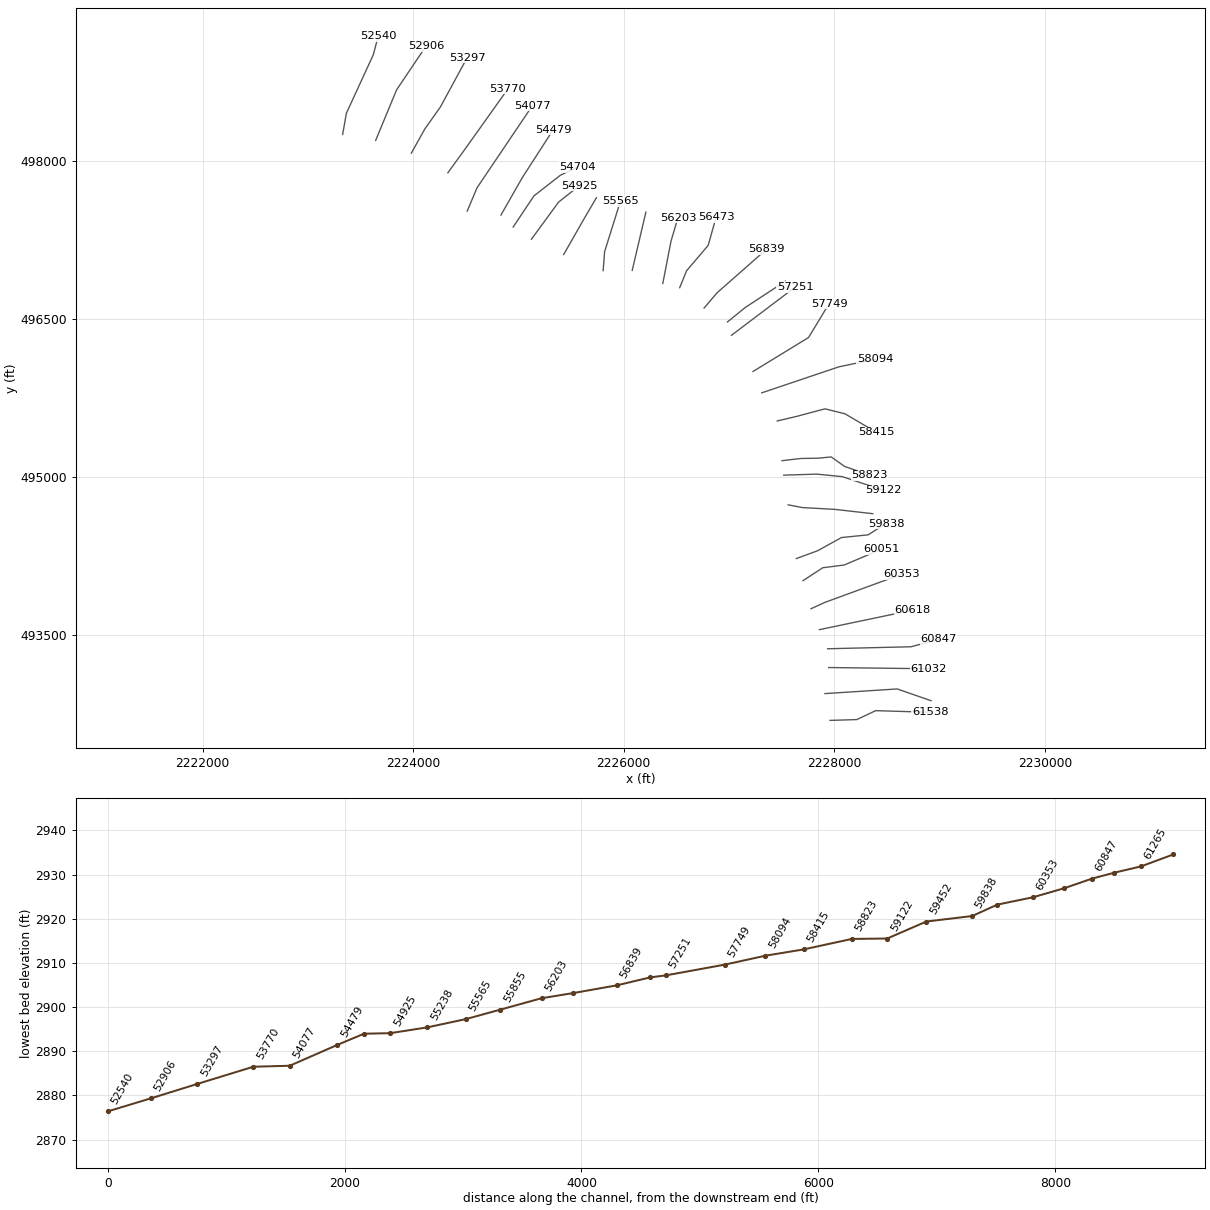
HEC-RAS study OLDFLDFK1.prj: OLDFLDFK1

--- OLDFLDFK1.g01 (geometry) --- (continued)

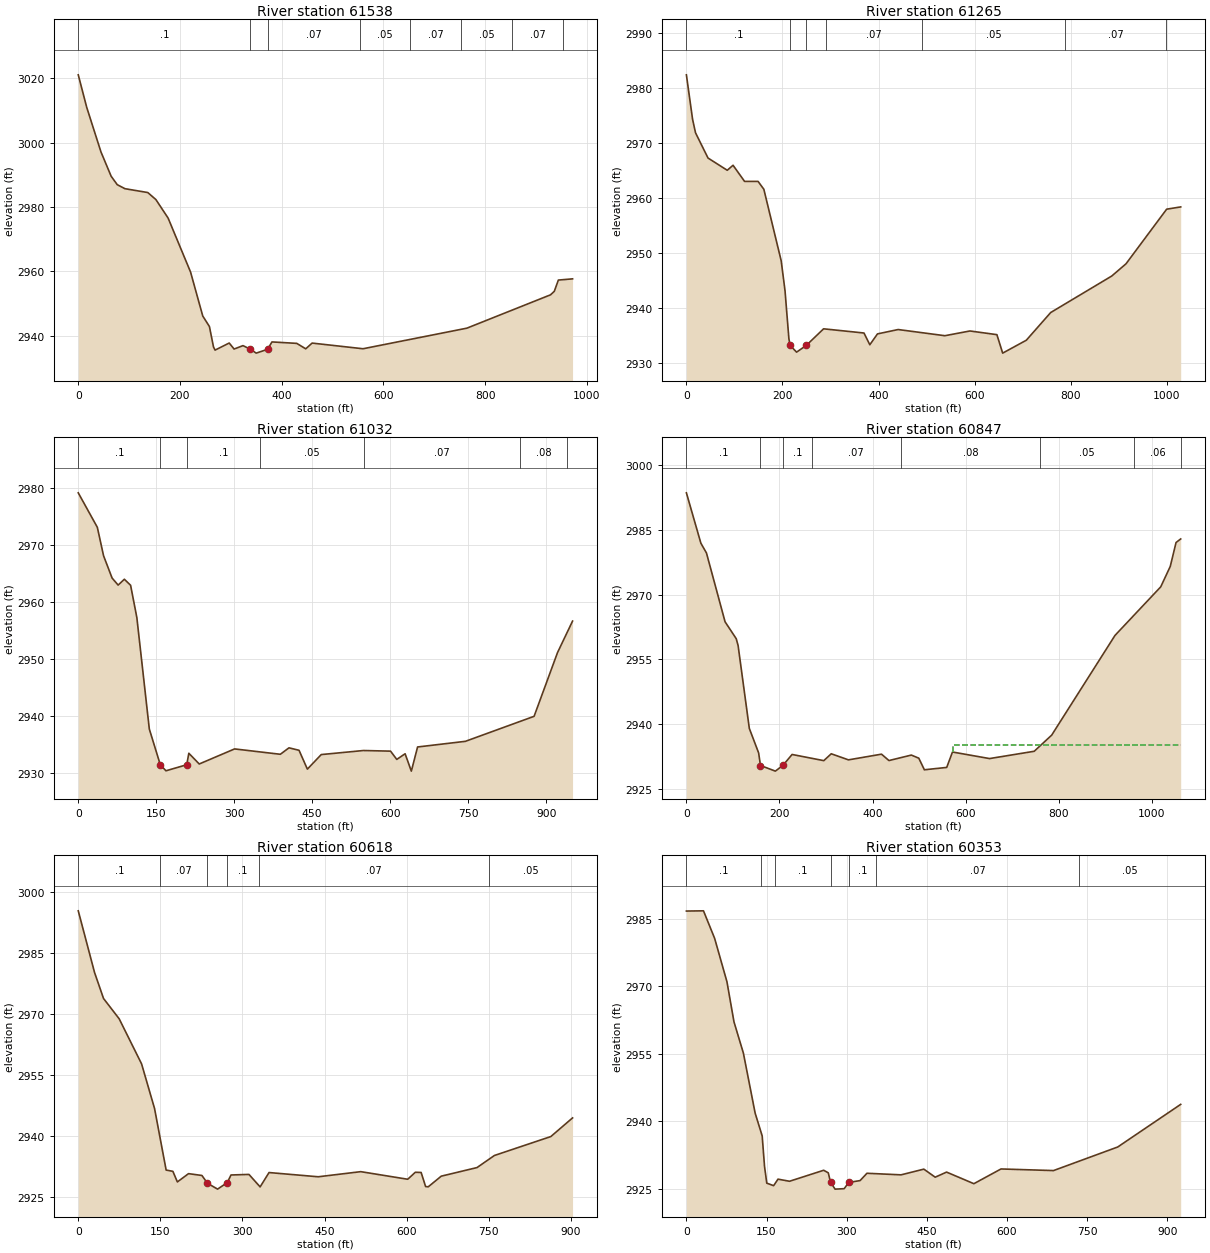
Type RM Length L Ch R = 1 ,61538   ,287.1,272.8,263.6
XS GIS Cut Line= 4
2227959.51708466492687.3130385292228214.03292157492695.025639647
2228393.35089758 492779.864251952228912.02332279492764.439049713
#Sta/Elev= 30
       0 3021.06    16.7 3010.92    44.7 2997.08    64.7 2989.54    76.7 2986.92
    91.8 2985.68   136.7 2984.48   152.7 2982.29   176.7 2976.54   220.8 2959.79
   244.8 2946.11   257.9 2942.85   265.9 2936.51     269 2935.52   296.8 2937.72
   306.4 2935.85   323.9 2936.91   338.6 2935.78   349.9 2934.58   372.2 2935.77
   380.9 2938.06   429.6 2937.61   447.3 2935.92   459.8  2937.7   559.9 2935.94
     764 2942.33   928.6  2952.7     936 2953.79     944 2957.28   971.9 2957.66
#Mann= 8 ,-1,0
       0      .1       0   338.6    .045       0   372.2     .07       0
  553.01     .05       0  653.01     .07       0  753.01     .05       0
  853.01     .07       0  953.01     .06       0
Bank Sta=338.6,372.2
XS Rating Curve= 0 ,0
Exp/Cntr(USF)=0,0
Exp/Cntr=0.3,0.1

Type RM Length L Ch R = 1 ,61265   ,234.6,232.5,228.9
XS GIS Cut Line= 3
2227911.31332767492941.8288754382228597.73482722492986.176331869
2228919.73592391492874.343615651
#Sta/Elev= 30
       0 2982.37    12.9 2974.28      19 2971.85      45 2967.27      85 2965.05
    97.1 2965.96   121.1 2963.03   149.2 2963.03   161.2  2961.6   197.3 2948.62
   205.3 2943.16   213.3 2934.49   215.9 2933.27   229.3 2932.05   249.4 2933.26
   285.5 2936.28   369.6 2935.52   381.7 2933.39   397.7 2935.36   440.7 2936.15
     538 2935.03   590.1 2935.89   646.2 2935.22   658.2 2931.87   707.4 2934.21
   758.2 2939.24   885.2 2945.86   914.9 2948.08   999.5 2957.99  1028.7  2958.4
#Mann= 7 ,-1,0
       0      .1       0   215.9    .045       0   249.4      .1       0
     290     .07       0     490     .05       0  787.85     .07       0
  997.85     .06       0
Bank Sta=215.9,249.4
XS Rating Curve= 0 ,0
Exp/Cntr(USF)=0,0
Exp/Cntr=0.3,0.1

Type RM Length L Ch R = 1 ,61032   ,183.8,184.9,186.8
XS GIS Cut Line= 2
 2227947.4854857493189.5185942352228898.24144673493178.022149725
#Sta/Elev= 30
       0 2979.15    36.7 2973.11    48.7 2968.12    65.1 2964.22    76.7 2962.99
    88.7 2964.01   100.7 2962.95   112.7 2957.31   136.7 2937.77  157.86  2931.5
   168.7 2930.46   208.7 2931.52   212.7 2933.53   232.7 2931.65   300.7 2934.29
   388.7 2933.35   405.3 2934.48   424.7 2934.05   440.7 2930.75   467.4  2933.3
   548.7 2934.01   600.7  2933.9   612.7 2932.45   628.7 2933.44   640.7  2930.4
   652.7 2934.63   744.7 2935.62   876.8    2940   921.9 2951.17   950.8 2956.68
#Mann= 7 ,-1,0
       0      .1       0  157.86    .045       0   208.7      .1       0
     350     .05       0     550     .07       0     850     .08       0
     940     .05       0
Bank Sta=157.86,208.7
XS Rating Curve= 0 ,0
Exp/Cntr(USF)=0,0
Exp/Cntr=0.3,0.1

Type RM Length L Ch R = 1 ,60847   ,223.6,229.7,236.1
XS GIS Cut Line= 3
2227937.05724165493367.8749398382228728.88321217493386.825395972
2228989.78821435493456.069514153
#Sta/Elev= 30
       0 2993.57    31.1  2981.9    43.1 2979.63    83.1 2963.68   107.1 2959.76
   111.1 2958.17   135.2 2938.97   155.2 2933.29   159.2 2930.37   191.2 2929.07
   207.5 2930.42   227.1 2932.93   295.2  2931.5   311.2 2933.09   348.2 2931.68
   419.2    2933   435.2 2931.52   483.3 2932.79   499.3 2932.07   511.3 2929.38
   559.3 2929.93   571.7  2933.5   651.3 2931.98   747.3 2933.67   784.8 2937.41
   920.9 2960.53  1019.1 2971.78  1039.6 2976.52    1052 2982.05    1062 2982.88
#Mann= 8 ,-1,0
       0      .1       0   159.2    .045       0   207.5      .1       0
     270     .07       0     460     .08       0     760     .05       0
  962.05     .06       0 1061.99      .1       0
#XS Ineff= 2 , 0
                          572.81         2935.16
Permanent Ineff=
       F       F
Bank Sta=159.2,207.5
XS Rating Curve= 0 ,0
Exp/Cntr=0.3,0.1

Type RM Length L Ch R = 1 ,60618   ,260.1,264.5,269.5
XS GIS Cut Line= 2
2227858.96286297493549.3573074192228743.03944584493734.450064041
#Sta/Elev= 30
       0 2995.44    29.8 2980.25    46.2 2973.86    74.8 2968.86   115.7 2957.77
   139.4 2946.79   160.6 2931.63   172.9 2931.32   181.1 2928.71   201.5 2930.75
     226  2930.3   236.1 2928.38   254.6 2926.94   272.4 2928.57   279.1 2930.42
   311.9 2930.56   332.3 2927.49   348.6 2931.02   438.5 2929.98   516.2 2931.24
     602 2929.37   615.9 2931.09   626.5 2931.04   634.7 2927.57   639.5 2927.51
   663.3 2930.13   728.7 2932.25   760.4 2935.22   863.5 2939.88   903.2 2944.47
#Mann= 6 ,-1,0
       0      .1       0     150     .07       0   236.1    .045       0
   272.4      .1       0     330     .07       0     750     .05       0
Bank Sta=236.1,272.4
XS Rating Curve= 0 ,0
Exp/Cntr(USF)=0,0
Exp/Cntr=0.3,0.1

Type RM Length L Ch R = 1 ,60353   ,307.8,301.9,293.9
XS GIS Cut Line= 3
2227779.11255611493748.1316390282227910.93983909493808.402374221
2228643.70032001494076.932162283
#Sta/Elev= 30
       0 2986.79      32 2986.84    52.9  2980.7    75.9 2971.06    89.1 2962.12
   106.7 2955.16   128.7 2941.81   141.9 2936.72   146.3 2929.91   150.5 2926.21
   163.3 2925.65   171.5  2927.1   193.1 2926.63     257 2929.08   265.6 2928.51
   269.8 2926.46   278.3 2924.88   295.4 2924.98   303.9 2926.37   325.2 2926.78
     338 2928.41   401.9 2928.06   444.5 2929.33   465.8 2927.54   487.1 2928.67
   538.2 2926.09     589 2929.37   687.3 2929.01   807.5 2934.26   925.4 2943.75
#Mann= 7 ,-1,0
       0      .1       0     140     .07       0  164.95      .1       0
   269.8    .045       0   303.9      .1       0  354.95     .07       0
  734.95     .05       0
Bank Sta=269.8,303.9
XS Rating Curve= 0 ,0
Exp/Cntr=0.3,0.1

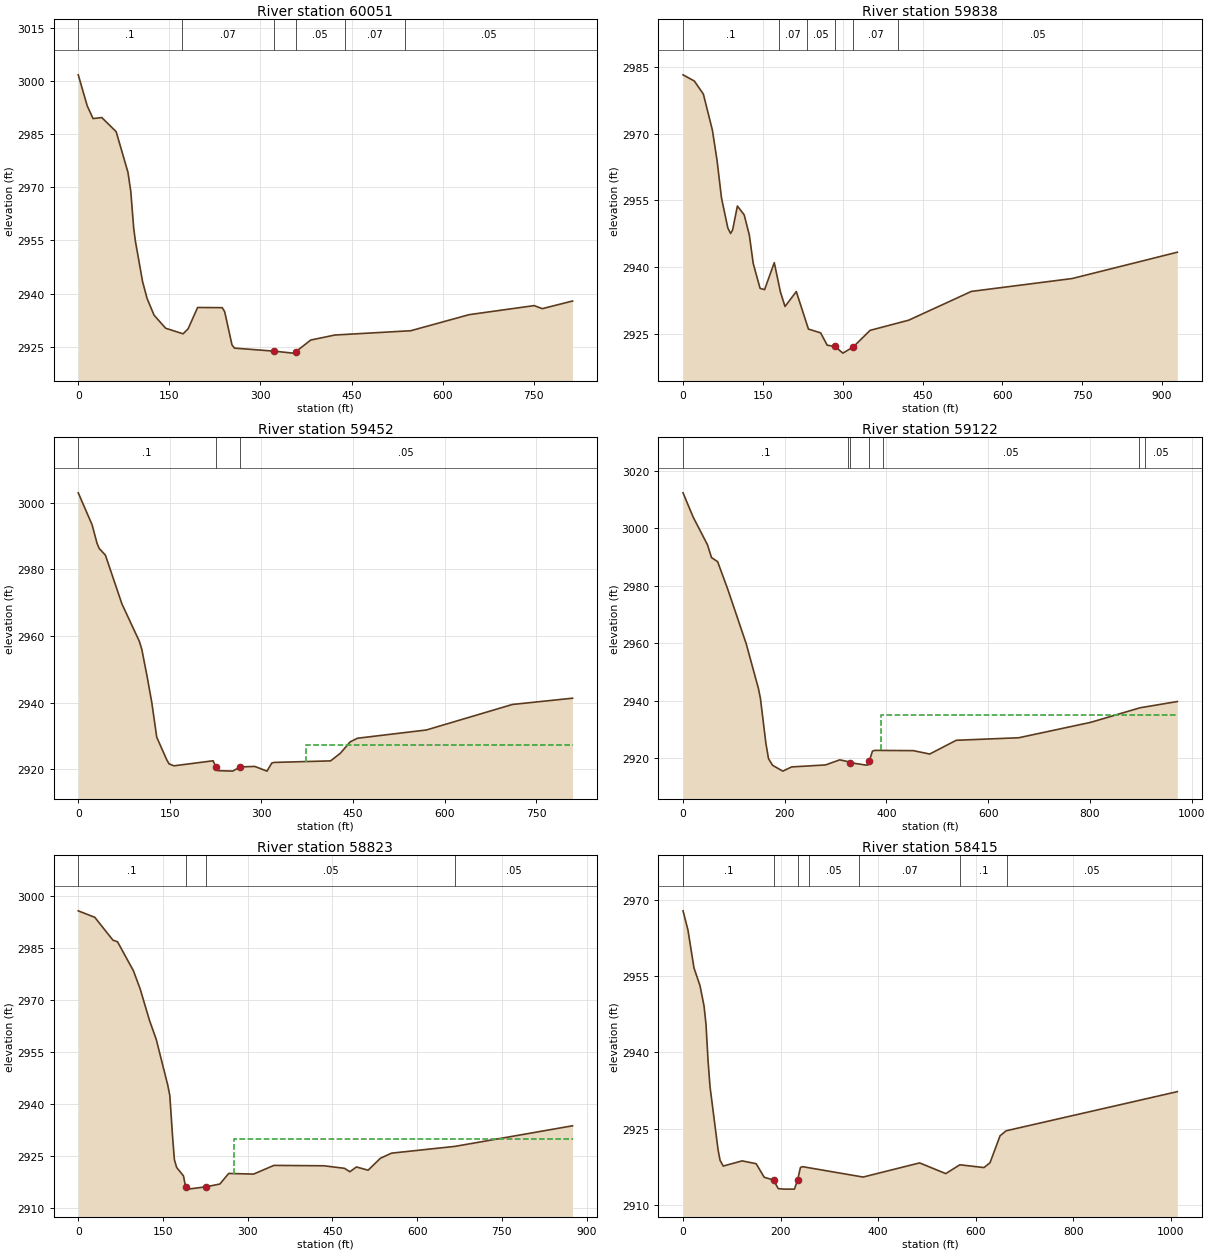
Type RM Length L Ch R = 1 ,60051   ,201.5,213.4,225.4
XS GIS Cut Line= 4
 2227703.7769571494015.1679468132227890.67120658494137.529204318
2228094.32727215494163.5100192682228448.73046637494313.870867378
#Sta/Elev= 30
       0 3001.75    14.8 2992.98    24.4  2989.4    38.7  2989.7    62.4 2985.71
    81.8 2974.26    86.5 2968.81    91.3 2958.43    94.2 2954.67   105.9 2943.39
   113.2 2938.69   124.8 2933.92   143.9 2930.23   172.6 2928.66   180.9 2930.09
   196.5 2936.09     237 2936.04     241 2934.92   253.1 2925.53   257.2 2924.62
   322.72923.764   353.2 2923.21   358.12923.608   382.7  2926.9   422.5 2928.32
   547.3 2929.53   643.6 2934.07   750.5 2936.62   763.9 2935.76   813.7 2937.92
#Mann= 6 ,-1,0
       0      .1       0     170     .07       0   322.7    .045       0
   358.1     .05       0  438.69     .07       0  538.69     .05       0
Bank Sta=322.7,358.1
XS Rating Curve= 0 ,0
Exp/Cntr(USF)=0,0
Exp/Cntr=0.3,0.1

Type RM Length L Ch R = 1 ,59838   ,403.7,386.2,365.7
XS GIS Cut Line= 5
2227640.30997725494225.1342735052227840.91044071494298.608162882
2228069.20627943494424.661079966 2228321.3121136494449.871663383
2228490.78325768494557.716936888
#Sta/Elev= 30
       0 2983.22    21.2 2981.83    38.2 2978.89    55.2 2970.76    63.8 2964.07
    72.3  2955.5    84.1  2948.8    89.3 2947.53    93.2 2948.36   102.1 2953.71
   114.9 2951.72   124.6 2947.15   131.9 2940.77   144.7  2935.2   153.2  2934.9
   171.4 2940.97     183 2934.37   191.6 2931.11   212.8 2934.47   235.6 2926.03
   258.5 2925.18   270.9  2922.4   285.2 2922.13   300.4 2920.62  319.82 2922.01
   351.4 2925.74     424 2928.03   541.7  2934.5   731.2  2937.4   928.7 2943.32
#Mann= 6 ,-1,0
       0      .1       0     180     .07       0  233.63     .05       0
   285.2    .045       0  319.82     .07       0  403.63     .05       0
Bank Sta=285.2,319.82
XS Rating Curve= 0 ,0
Exp/Cntr=0.3,0.1

Type RM Length L Ch R = 1 ,59452   ,329.4,330.4,326.4
XS GIS Cut Line= 4
2227561.94460717494735.0914211342227697.27967088494709.106194138
2228004.77923292494692.1733817782228365.99439383494651.034425685
#Sta/Elev= 30
       0 3003.04    22.6 2993.46    30.8 2987.85    34.3 2986.32    44.5 2984.29
    71.5 2969.65     100 2958.42   104.1 2955.97   112.9 2947.67   120.4 2940.01
   128.5 2929.59   144.7 2922.87   148.7 2921.56   156.7 2920.98   220.8 2922.49
  225.332920.638   228.8 2919.51   252.9 2919.39   264.9 2920.63   288.9  2920.8
     309 2919.38     317 2921.84     321    2922   413.1 2922.46   429.1 2924.74
   445.2 2928.18   457.2 2929.27     570 2931.75   710.9 2939.42   809.3  2941.3
#Mann= 3 ,-1,0
       0      .1       0  225.33    .045       0   264.9     .05       0
#XS Ineff= 2 , 0
                          372.65         2927.34
Permanent Ineff=
       F       F
Bank Sta=225.33,264.9
XS Rating Curve= 0 ,0
Exp/Cntr=0.3,0.1

Type RM Length L Ch R = 1 ,59122   ,263.3,298.2,233.5
XS GIS Cut Line= 4
2227520.17579613495017.1097902622227832.50691291495026.913906035
2228076.20921927495003.1039105862228469.77443816494872.849229599
#Sta/Elev= 30
       0 3012.26      20 3003.79      48 2994.22      56 2989.75      68 2988.35
      88 2978.71   124.1 2959.87   148.1 2944.34   152.1 2940.88     163 2925.11
   168.1 2919.84   176.1 2917.55   196.1 2915.53   213.5 2916.99   280.1 2917.68
   308.2 2919.45   324.8 2918.81   328.4 2918.48   360.4 2917.61   364.4 2917.77
  366.132918.974   372.4 2922.47     377 2922.74   452.9 2922.65     485 2921.47
   537.2 2926.25   660.1 2927.13   801.7 2932.49   898.6 2937.55   971.9 2939.72
#Mann= 7 ,-1,0
       0      .1       0   324.8    .045       0   328.4    .045       0
  366.13      .1       0  392.48     .05       0  897.35      .1       0
  907.35     .05       0
#XS Ineff= 2 , 0
                          389.86         2934.97
Permanent Ineff=
       F       F
Bank Sta=328.4,366.13
XS Rating Curve= 0 ,0
Exp/Cntr(USF)=0,0
Exp/Cntr=0.3,0.1

Type RM Length L Ch R = 1 ,58823   ,402.3,408.6,428
BEGIN DESCRIPTION:
start of detailed reach
END DESCRIPTION:
XS GIS Cut Line= 6
2227503.11756793495154.6597348332227683.80254533 495175.66048464
2227847.09979998495178.2352006392227971.01348236495190.272127607
2228097.85228399495100.3280325682228333.51396006495017.630328581
#Sta/Elev= 30
       0 2995.66    29.3 2993.79    61.5 2987.19    69.5 2986.75    97.7 2978.37
   109.8 2973.05   125.9 2964.18     138 2958.63   158.4 2945.45   162.1 2942.42
   166.9 2930.73   170.2 2923.92   174.2 2921.68   186.3 2919.25  189.96  2916.1
   194.3 2915.44   226.3 2916.11   250.7 2916.91   266.3 2919.96   310.3 2919.77
   346.3 2922.28   434.7 2922.17   471.1 2921.44   480.9 2920.46   492.4 2921.83
   513.1  2920.9   534.9 2924.34   554.5 2925.81   667.2 2927.77     875  2933.7
#Mann= 4 ,-1,0
       0      .1       0  189.96    .045       0   226.3     .05       0
   667.2     .05       0
#XS Ineff= 2 , 0
                          276.06         2929.77
Permanent Ineff=
       F       F
Bank Sta=189.96,226.3
XS Rating Curve= 0 ,0
Exp/Cntr(USF)=0,0
Exp/Cntr=0.3,0.1

Type RM Length L Ch R = 1 ,58415   ,314.8,321.1,336.1
XS GIS Cut Line= 6
2227458.33455472495531.9143599252227650.80588187495577.391029002
2227779.03591656 495612.135285932227912.06188585495647.182420024
2228102.36164888495599.6560471392228402.76403014 495422.62145211
#Sta/Elev= 30
       0 2967.93    10.1 2964.13    22.4 2956.68    34.8 2953.17      43  2949.2
    47.1 2945.51    51.2 2938.46    55.3 2933.26    71.8 2920.81    75.9 2918.74
    82.4 2917.61   121.1 2918.63   149.9 2918.07   166.3  2915.4   185.4 2914.85
   195.1 2913.16   207.5 2913.06   228.2 2913.06   234.6 2914.78   240.6 2917.33
   244.8 2917.49     369 2915.44   484.8 2918.23   538.4 2916.12   567.3 2917.86
   616.7 2917.31   629.1 2918.26   649.7 2923.58   662.1 2924.56    1013 2932.28
#Mann= 7 ,-1,0
       0      .1       0   185.4    .045       0   234.6     .08       0
  257.77     .05       0  360.62     .07       0  568.19      .1       0
  664.33     .05       0
Bank Sta=185.4,234.6
XS Rating Curve= 0 ,0
Exp/Cntr(USF)=0,0
Exp/Cntr=0.3,0.1

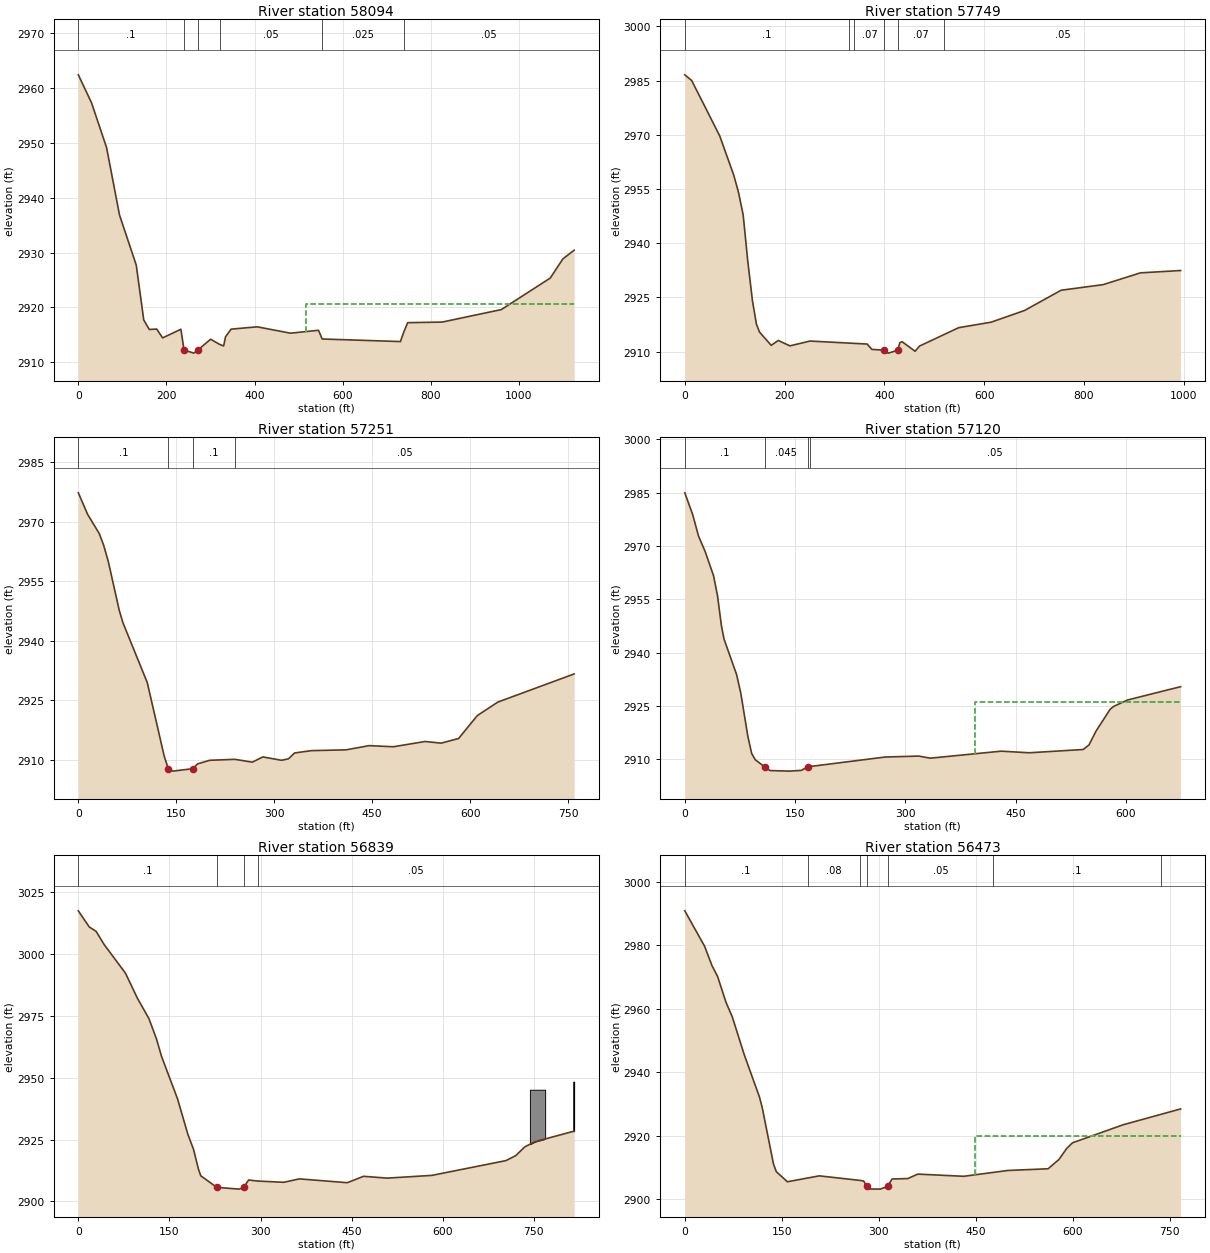
Type RM Length L Ch R = 1 ,58094   ,261.7,344.9,327.8
XS GIS Cut Line= 3
2227311.48043651 495799.311122452228044.78319741496046.502153381
2228389.38035949496118.178363094
#Sta/Elev= 30
       0 2962.44      30 2957.33    64.1 2949.17    93.5 2936.85   131.5 2927.71
   148.5  2917.7   161.1 2915.96     178 2916.03   191.4 2914.42   232.9    2916
  239.93  2912.2   262.4 2911.64   270.9 2912.18   300.4 2914.18   320.9 2913.23
     330 2912.95   334.2 2914.62   346.9 2916.02   406.1 2916.44   481.7 2915.28
   545.3 2915.81   553.7 2914.22   731.3 2913.75   739.4 2915.58   747.9  2917.2
   826.4 2917.31   960.5 2919.59  1071.5 2925.34  1100.3 2928.85  1125.8 2930.43
#Mann= 6 ,-1,0
       0      .1       0  239.93    .045       0   270.9      .1       0
   320.9     .05       0   553.7    .025       0   739.4     .05       0
#XS Ineff= 2 , 0
                          517.18         2920.55
Permanent Ineff=
       F       T
Bank Sta=239.93,270.9
XS Rating Curve= 0 ,0
Exp/Cntr(USF)=0,0
Exp/Cntr=0.3,0.1

Type RM Length L Ch R = 1 ,57749   ,417.3,497.5,457.3
XS GIS Cut Line= 3
2227228.40534642 496002.241368762227755.94726292496325.013725568
 2227950.3048111496646.050747124
#Sta/Elev= 30
       0 2986.57    13.8    2985    70.1 2969.65      98 2958.87   107.6  2954.1
     117 2947.82   126.3  2934.9   135.7 2923.99   143.6 2917.59   149.8 2915.42
   173.2 2911.77   187.3 2913.11   210.7 2911.62   250.9 2912.95   365.5 2912.12
   374.9 2910.65  399.62 2910.41   407.7 2909.61   426.7 2910.39   431.1 2912.52
   435.5 2912.77   461.6 2910.13   470.4 2911.56   548.9 2916.65     614 2918.17
   680.7 2921.39   754.2    2927   838.4 2928.55   913.2 2931.81   993.7 2932.45
#Mann= 6 ,-1,0
       0      .1       0     330     .05       0     340     .07       0
  399.62    .045       0   426.7     .07       0     520     .05       0
Bank Sta=399.62,426.7
XS Rating Curve= 0 ,0
Exp/Cntr(USF)=0,0
Exp/Cntr=0.3,0.1

Type RM Length L Ch R = 1 ,57251   ,128,130.9,131
XS GIS Cut Line= 2
2227023.63578672496345.8377485882227629.26778955496803.966255025
#Sta/Elev= 30
       0 2977.27    14.2 2971.86    32.1 2966.99    38.7 2964.12    45.8 2960.04
    62.7 2947.65    68.4 2944.53   105.6 2929.47   131.5 2910.97     138  2907.7
   144.8 2907.18  175.25  2907.8   182.7 2909.01   201.3 2909.91   239.8 2910.15
   266.5 2909.44   282.6 2910.76   311.2 2909.91   321.7 2910.27   331.2 2911.75
   356.8 2912.34     410 2912.54   445.4  2913.6   482.5 2913.32     531 2914.64
   555.9 2914.23   582.5 2915.41     611 2921.16   642.4 2924.56   759.4 2931.66
#Mann= 4 ,-1,0
       0      .1       0     138    .045       0  175.25      .1       0
     240     .05       0
Bank Sta=138,175.25
XS Rating Curve= 0 ,0
Exp/Cntr(USF)=0,0
Exp/Cntr=0.3,0.1

Type RM Length L Ch R = 1 ,57120   ,279.4,280.9,287.8
XS GIS Cut Line= 3
2226985.64570824496472.7208234822227155.87188303496611.102673723
2227536.23639514496860.412873941
#Sta/Elev= 30
       0 2984.96    10.7 2978.87    18.7 2972.78    27.7 2968.46    39.1 2961.65
    44.5 2956.03    49.7 2947.72    53.3 2943.89    70.4 2933.89    76.1  2928.7
    85.7 2916.56    90.9 2911.71    95.8 2909.94   108.5 2907.94   115.9 2906.89
   142.4 2906.73   158.5 2906.94     167 2907.94   272.3 2910.69     318 2910.96
   333.8 2910.37   430.2 2912.34   468.4 2911.89   541.8 2912.81   549.7 2914.12
   559.1 2917.96   578.4 2924.13   583.2 2924.92   601.9 2926.72   674.2 2930.47
#Mann= 4 ,-1,0
       0      .1       0   108.5    .045       0     167      .1       0
     170     .05       0
#XS Ineff= 2 , 0
                          393.98          2926.1
Permanent Ineff=
       F       F
Bank Sta=108.5,167
XS Rating Curve= 0 ,0
Exp/Cntr(USF)=0,0
Exp/Cntr=0.3,0.1

Type RM Length L Ch R = 1 ,56839   ,366.8,366.6,379.5
XS GIS Cut Line= 3
2226763.38805812496604.6989103312226887.37917857496750.444668838
2227356.49162272497163.236005316
#Sta/Elev= 30
       0  3017.5    17.9    3011    29.3 3009.19    42.6 3003.82    77.5 2992.33
    97.4 2982.08   116.2 2973.92   128.6 2965.71     137 2958.61   163.4 2941.39
   180.2 2927.18   189.7 2920.97   197.7 2913.05   201.5 2910.34   227.9 2905.66
   264.7 2904.93   272.3 2905.67   280.3 2908.62   295.9 2908.18   338.4  2907.7
   363.9 2909.07   442.8 2907.53   469.5 2910.12   508.4 2909.38   582.1 2910.49
     704 2916.47   719.9 2918.46   735.2 2922.07   751.9 2924.12   816.2 2928.39
#Mann= 4 ,-1,0
       0      .1       0   227.9    .045       0   272.3      .1       0
   295.9     .05       0
#Block Obstruct= 2 ,-1
  743.37  768.47 2945.13  814.68  816.22 2948.39
Bank Sta=227.9,272.3
XS Rating Curve= 0 ,0
Exp/Cntr=0.3,0.1

Type RM Length L Ch R = 1 ,56473   ,197,269.7,297.8
XS GIS Cut Line= 4
2226531.43953293496798.1669097452226596.93808941 496958.96077657
2226801.94813426497199.8030781342226877.32603721497466.452782916
#Sta/Elev= 30
       0  2990.8    30.5  2979.7    42.1 2973.54    50.8  2970.1    63.7 2962.02
    73.5  2957.4    91.9 2945.55   115.5 2932.19   119.9 2928.74   137.1 2911.17
   141.5  2908.7   158.7 2905.51   208.1 2907.37   271.2 2905.93   276.8 2905.72
   281.6 2904.07   286.8 2903.23   302.3 2903.19   313.7 2904.05   320.6 2906.38
   344.9 2906.51   360.4 2907.92   431.6 2907.23   499.6 2909.06     562  2909.6
   578.6 2912.49   591.1 2916.08   599.8 2917.78   678.4 2923.47     767 2928.44
#Mann= 7 ,-1,0
       0      .1       0     190     .08       0   271.2     .05       0
   281.6    .045       0   313.7     .05       0  476.83      .1       0
  736.37     .05       0
#XS Ineff= 2 , 0
                          448.88            2920
Permanent Ineff=
       F       F
Bank Sta=281.6,313.7
XS Rating Curve= 0 ,0
Exp/Cntr(USF)=0,0
Exp/Cntr=0.3,0.1

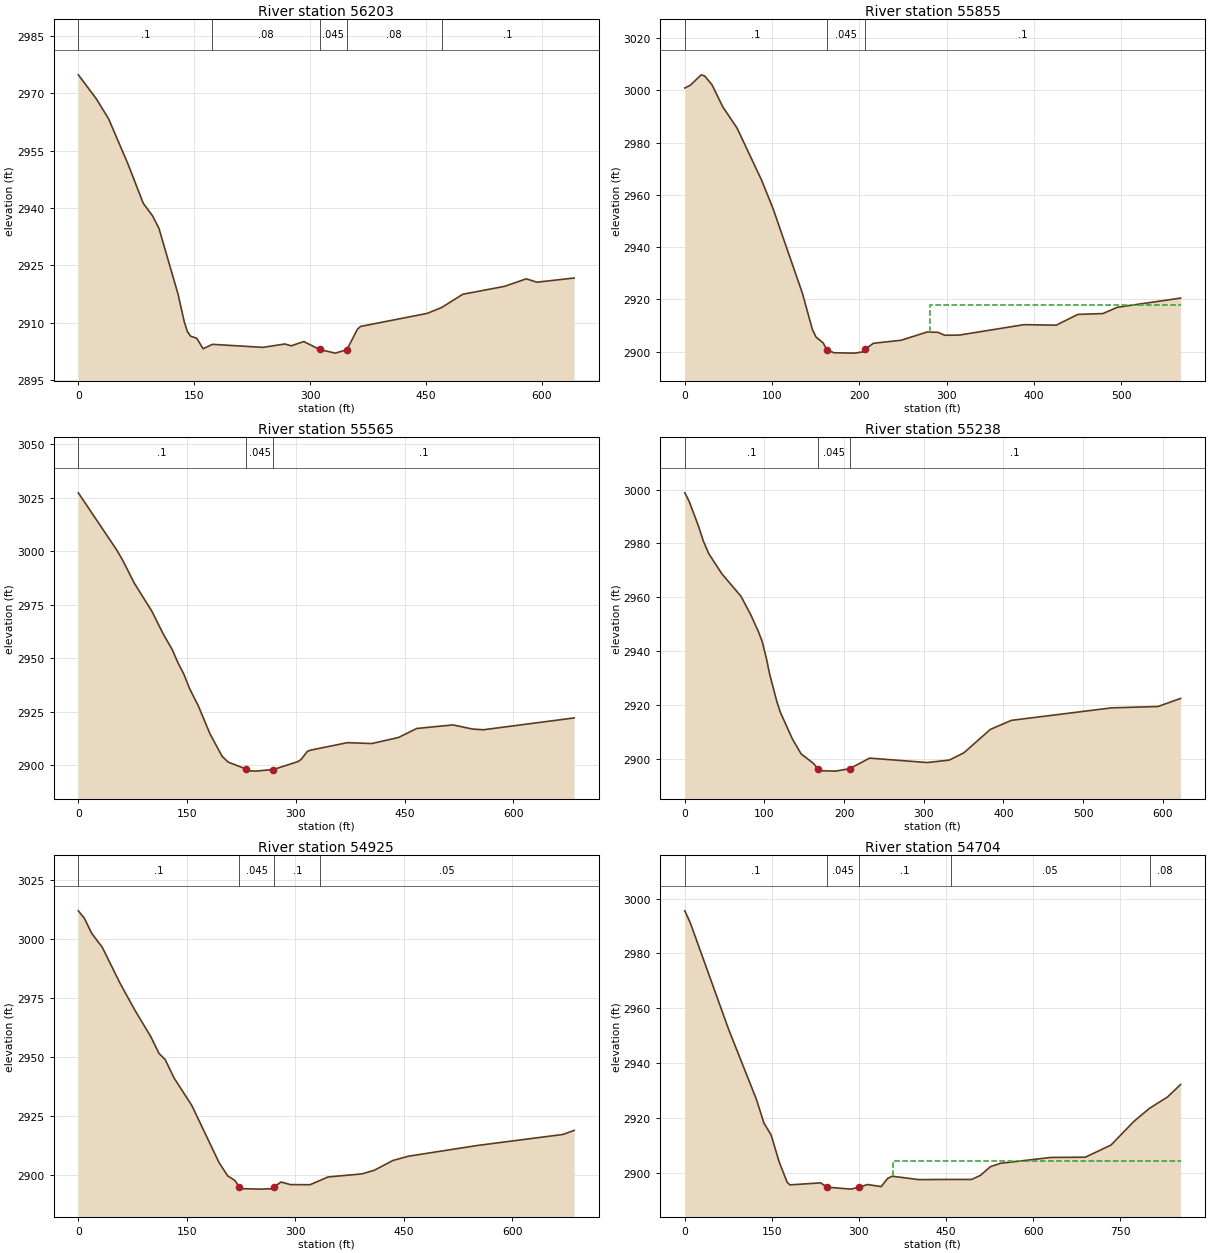
Type RM Length L Ch R = 1 ,56203   ,309.6,347.6,303.2
XS GIS Cut Line= 3
 2226371.1497321496838.6729600582226449.23981842497241.270738442
2226515.18255799497463.393650654
#Sta/Elev= 30
       0 2974.85    22.9 2968.69    39.2 2963.33    63.7 2951.79      84 2941.25
    96.3 2937.87   104.4 2934.64   128.9 2917.58     137 2910.32   141.1 2907.68
   145.2 2906.47   153.3 2905.88   161.5 2903.17   173.6 2904.31   238.9 2903.52
   267.4  2904.4   275.5 2903.92   291.8 2905.05   312.22902.968   332.6 2902.01
   347.7 2902.92   361.1 2908.21   365.2 2908.99   451.7 2912.42   470.3 2913.95
   497.6 2917.41   551.9  2919.5   579.7 2921.45   593.6 2920.58   641.8 2921.67
#Mann= 5 ,-1,0
       0      .1       0   173.6     .08       0   312.2    .045       0
   347.7     .08       0   470.3      .1       0
Bank Sta=312.2,347.7
XS Rating Curve= 0 ,0
Exp/Cntr(USF)=0,0
Exp/Cntr=0.3,0.1

Type RM Length L Ch R = 1 ,55855   ,293.9,290.6,288.5
XS GIS Cut Line= 2
2226080.61151953 496962.894070682226210.25908002497515.807138682
#Sta/Elev= 30
       0 3000.93     6.5 3002.07    18.8    3006    22.9 3005.53    31.1 3002.23
    43.4 2993.81    59.9 2985.58    88.1 2965.56     101 2954.85   134.7 2922.36
   146.1 2908.54   150.3 2905.59   158.5 2903.35   162.6 2900.74   170.8 2899.58
   194.6 2899.43   203.7  2899.9  206.19 2900.83     216  2903.2   247.8 2904.36
   277.6 2907.52   289.9  2907.4   297.7 2906.27   314.6 2906.35   388.5 2910.33
   425.5 2910.14   450.2 2914.26   478.9 2914.58   495.4 2916.98   567.9  2920.5
#Mann= 3 ,-1,0
       0      .1       0   162.6    .045       0  206.19      .1       0
#XS Ineff= 2 , 0
                          280.56         2917.99
Permanent Ineff=
       F       F
Bank Sta=162.6,206.19
XS Rating Curve= 0 ,0
Exp/Cntr(USF)=0,0
Exp/Cntr=0.3,0.1

Type RM Length L Ch R = 1 ,55565   ,332.7,326.4,305.8
XS GIS Cut Line= 3
 2225804.4028902496960.1965499552225818.23585778497140.025128511
2225968.66938023 497620.72075196
#Sta/Elev= 30
       0 3027.19    52.9 3000.55    61.2 2995.72    77.2 2985.04   101.3    2972
   117.3 2961.19   129.4  2954.1   137.4  2947.9   145.4 2942.68   153.4 2935.87
   165.5 2927.76   181.6 2914.72   198.3 2904.24   206.7  2901.5   230.7 2898.37
   236.1 2897.44   244.4 2897.29     269 2898.03   303.1 2901.76   307.3 2902.74
   315.7 2906.41   319.9 2907.05   371.2 2910.58   404.9 2910.17   441.5 2912.97
   466.9  2917.2   516.9 2918.86   543.6 2916.94   558.8  2916.6     684 2922.12
#Mann= 3 ,-1,0
       0      .1       0   230.7    .045       0     269      .1       0
Bank Sta=230.7,269
XS Rating Curve= 0 ,0
Exp/Cntr(USF)=0,0
Exp/Cntr=0.3,0.1

Type RM Length L Ch R = 1 ,55238   ,316.1,312.9,303.2
XS GIS Cut Line= 3
2225429.20631327497112.8236566082225628.58321965497462.298578513
 2225740.1308342497652.111850383
#Sta/Elev= 30
       0 2998.79     5.4 2995.67    17.1 2986.51    23.4 2980.79    30.2 2976.16
    46.4 2968.77    70.6 2960.34    83.3 2953.22    92.5 2947.13    97.1 2943.68
   102.9 2936.69   106.3 2931.72   115.5 2921.33   120.1 2917.17   135.1 2907.35
   146.1 2901.79   160.8 2898.47   167.4  2896.3   172.5 2895.54   189.2 2895.41
     2072896.314     232 2900.24   304.4  2898.6     332 2899.51   350.4 2902.22
   383.6 2910.91     410 2914.27   535.8 2918.91   594.1 2919.42   622.5 2922.42
#Mann= 3 ,-1,0
       0      .1       0   167.4    .045       0     207      .1       0
Bank Sta=167.4,207
XS Rating Curve= 0 ,0
Exp/Cntr(USF)=0,0
Exp/Cntr=0.3,0.1

Type RM Length L Ch R = 1 ,54925   ,218.9,221.7,223.9
XS GIS Cut Line= 3
2225122.96255978497258.369935106 2225381.2546491497611.635298857
2225576.20060611497765.451902581
#Sta/Elev= 30
       0    3012     8.4 3008.84    18.3 3002.56    33.2  2996.5    57.3 2981.56
    77.8 2970.14   100.2 2958.72   111.6 2951.59   120.2 2948.97   132.3 2941.25
   157.1 2929.48   194.7 2905.32   206.6 2899.72   216.6 2897.76  222.26 2895.17
   226.5 2894.29   251.2  2894.1   266.2 2894.25   271.1 2895.14   280.5 2897.12
   293.5 2896.01   320.6 2895.97   345.4 2899.25   392.2 2900.55   409.3 2902.08
   435.1 2906.22   456.6 2908.04   551.9 2912.59   670.6 2917.27   685.9 2918.98
#Mann= 4 ,-1,0
       0      .1       0  222.26    .045       0   271.1      .1       0
  334.75     .05       0
Bank Sta=222.26,271.1
XS Rating Curve= 0 ,0
Exp/Cntr=0.3,0.1

Type RM Length L Ch R = 1 ,54704   ,171.6,225,224
XS GIS Cut Line= 4
2224949.67148833497374.5127753212225146.77129469497670.162484862
2225399.57322025497867.2622912232225560.25241021497944.388302408
#Sta/Elev= 30
       0 2995.54     9.5 2991.14    75.3 2952.41   123.4 2926.71   136.4 2918.04
   148.7 2913.76   162.4 2904.01   176.3 2896.47   181.1 2895.52     234 2896.26
   245.2  2894.7   285.7 2893.97   300.2 2894.65   314.6 2895.65   338.3  2894.9
   349.3 2897.86   357.1 2898.69   402.8 2897.44   457.8 2897.51   494.1  2897.5
   509.3    2899   526.6 2902.19   543.7 2903.39     631 2905.54   689.9 2905.62
   734.2 2910.06   774.2 2918.81   800.8  2923.5   831.8 2927.64   854.1 2932.17
#Mann= 5 ,-1,0
       0      .1       0   245.2    .045       0   300.2      .1       0
   457.8     .05       0   800.8     .08       0
#XS Ineff= 2 , 0
                          358.87         2904.27
Permanent Ineff=
       F       F
Bank Sta=245.2,300.2
XS Rating Curve= 0 ,0
Exp/Cntr(USF)=0,0
Exp/Cntr=0.3,0.1

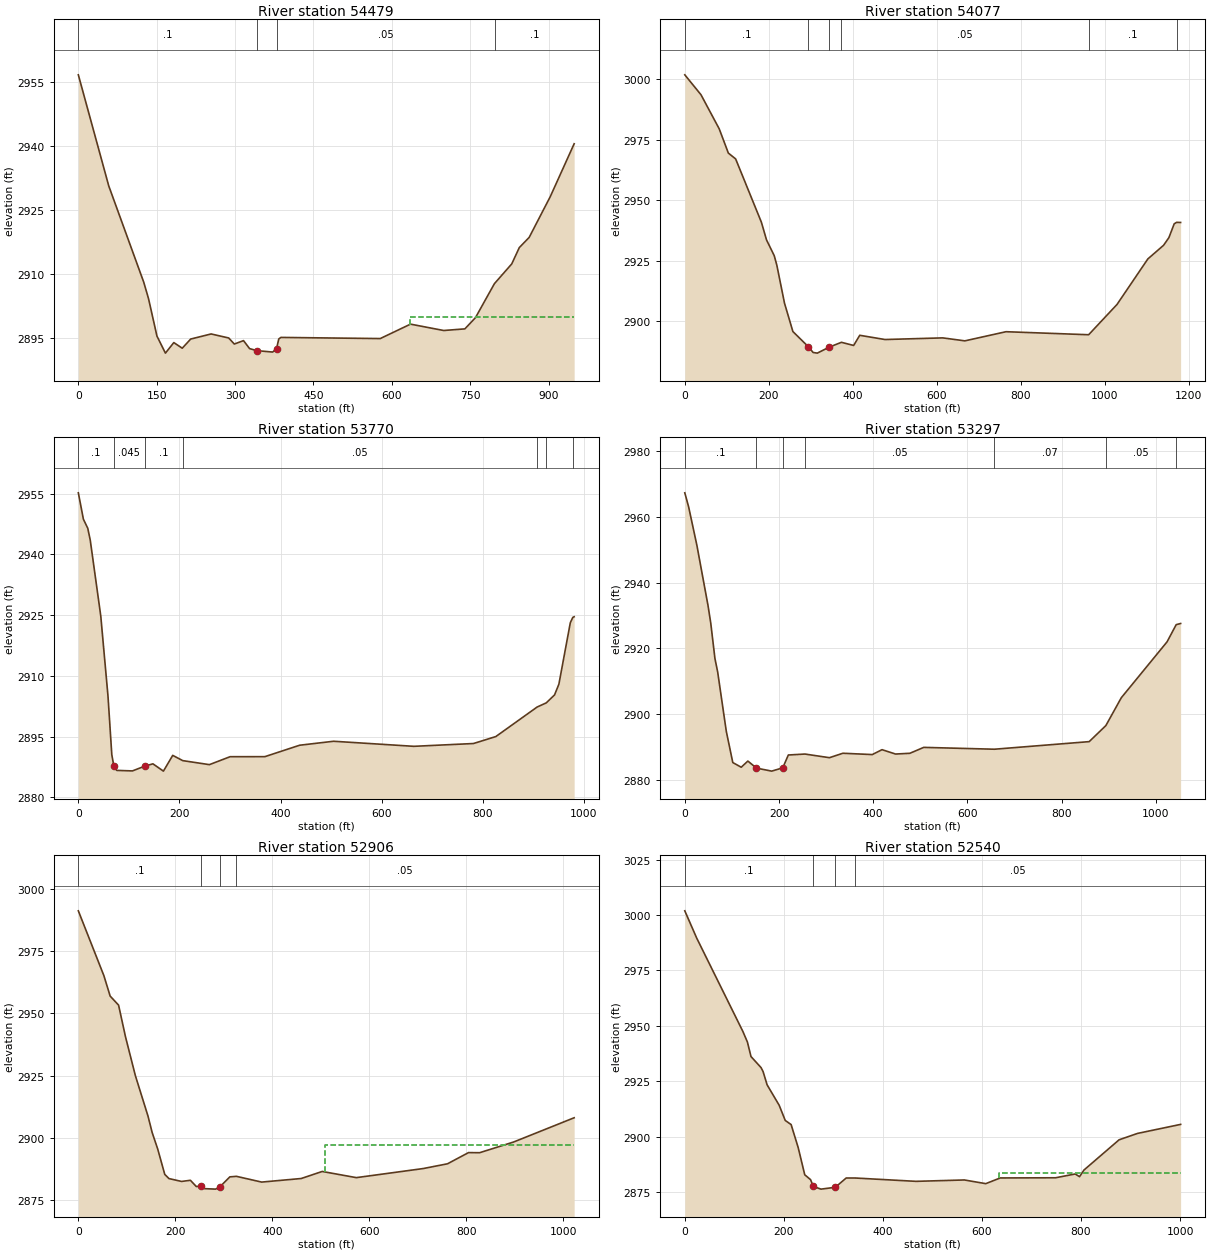
Type RM Length L Ch R = 1 ,54479   ,322.9,402,303.6
XS GIS Cut Line= 3
2224833.59943588497488.3817869992225035.92847096497843.187993831
2225329.00954323498297.535069921
#Sta/Elev= 30
       0 2956.63    58.2 2930.62   125.2 2908.06   134.4 2904.19   150.5 2895.43
   166.7 2891.44   182.8 2893.91   198.9 2892.59   215.1 2894.74   254.2 2895.93
   287.8 2894.99   298.6 2893.57   316.2 2894.37   327.8  2892.5   341.7 2892.02
     372 2891.69  379.42 2892.49   383.7 2894.76   387.7 2895.12   577.9 2894.85
   635.8 2898.23   699.4 2896.74   739.9 2897.12   760.2 2899.75   796.4  2907.7
   829.7 2912.35   844.1 2916.16     863 2918.55   903.3 2928.08   949.1 2940.48
#Mann= 4 ,-1,0
       0      .1       0   341.7    .045       0  379.42     .05       0
  798.44      .1       0
#XS Ineff= 2 , 0
                          633.95         2899.99
Permanent Ineff=
       F       F
Bank Sta=341.7,379.42
XS Rating Curve= 0 ,0
Exp/Cntr(USF)=0,0
Exp/Cntr=0.3,0.1

Type RM Length L Ch R = 1 ,54077   ,308.1,306.3,300
XS GIS Cut Line= 3
 2224512.7495423497525.6190998392224606.12207347497746.946581139
2225131.77484156498526.780128533
#Sta/Elev= 30
       0 3001.74    38.6  2993.5      82  2979.4   103.7  2969.4   121.1 2966.98
   182.4 2940.82   194.6 2933.52     213 2926.98   219.1 2923.12   237.4 2907.39
   257.4 2895.64     294  2889.4   305.6 2886.99   315.5 2886.72   344.2 2889.22
     373 2891.19   402.1 2889.89   416.6 2894.09   476.7 2892.34   614.3 2893.02
   666.9 2891.79   764.9 2895.57   961.7 2894.32  1029.2 2906.83  1102.7 2925.66
  1140.1 2931.29  1152.8 2934.46  1165.4 2940.16  1171.2 2940.77  1180.7 2940.72
#Mann= 6 ,-1,0
       0      .1       0     294    .045       0   344.2      .1       0
     373     .05       0   961.7      .1       0  1171.2    .016       0
Bank Sta=294,344.2
XS Rating Curve= 0 ,0
Exp/Cntr(USF)=0,0
Exp/Cntr=0.3,0.1

Type RM Length L Ch R = 1 ,53770   ,405.5,473.1,424.6
XS GIS Cut Line= 3
2224329.32072772 497890.044407462224484.81464986498104.332402409
2224900.14675933498687.303943456
#Sta/Elev= 30
       0 2955.17      10 2948.67    18.7 2946.41    23.6 2943.48    44.4 2924.76
    58.7 2904.95    66.2 2890.54    70.2 2887.81    75.9 2886.68     107 2886.55
  131.332887.727   147.5  2888.3   168.3  2886.5   186.7 2890.39   206.5 2889.09
   259.2  2888.1   300.2 2890.06   368.9 2890.07   437.7 2892.89   504.9 2893.87
   663.6 2892.62   781.5 2893.31   825.7 2895.03   907.3 2902.31   925.4 2903.34
   941.8  2905.3   950.4 2907.95     973 2923.11   977.9 2924.43   980.6 2924.59
#Mann= 7 ,-1,0
       0      .1       0    70.2    .045       0  131.33      .1       0
   206.5     .05       0   907.3      .1       0   925.4     .06       0
   977.9    .016       0
Bank Sta=70.2,131.33
XS Rating Curve= 0 ,0
Exp/Cntr(USF)=0,0
Exp/Cntr=0.3,0.1

Type RM Length L Ch R = 1 ,53297   ,381.4,391.3,406
XS GIS Cut Line= 4
2223982.12510124498076.2112829392224111.26321211498307.757343176
2224257.70784771 498513.963852152224512.67447346498983.820486402
#Sta/Elev= 30
       0 2967.34     8.1 2963.09    25.7 2951.34    49.3 2933.02    55.1  2927.7
      64 2916.88    69.8  2912.8    88.1 2894.73   101.9 2885.22   119.8  2883.8
   133.9 2885.67   152.2 2883.53   184.5 2882.61     208 2883.62   219.8 2887.52
   255.1 2887.81     307  2886.7   335.6 2888.05     398 2887.65   418.7 2889.14
   447.5 2887.81   477.8 2888.04   507.3 2889.84   657.4 2889.28   858.5 2891.59
   893.9 2896.48   926.7 2904.96  1023.8 2921.97  1043.2  2927.2  1052.6 2927.56
#Mann= 7 ,-1,0
       0      .1       0   152.2    .045       0     208      .1       0
   255.1     .05       0   657.4     .07       0   893.9     .05       0
  1043.2    .016       0
Bank Sta=152.2,208
XS Rating Curve= 0 ,0
Exp/Cntr(USF)=0,0
Exp/Cntr=0.3,0.1

Type RM Length L Ch R = 1 ,52906   ,355.3,366.4,345.6
XS GIS Cut Line= 3
2223643.00170563498196.5180275312223841.85061461 498677.21365098
2224121.96820813499093.931799365
#Sta/Elev= 30
       0 2991.23    52.7 2965.16    65.6 2956.96      83 2953.32    97.2 2940.63
   117.6 2924.98   143.6 2908.74   152.2 2902.12   163.7 2895.45   178.2 2885.28
   186.9 2883.59   212.8 2882.44   231.1  2882.9   243.3 2880.38   252.5 2880.63
   260.4 2879.54   283.1 2879.35   292.3 2880.34   312.4 2884.28     326 2884.49
     378 2882.18   459.6 2883.62   502.8 2886.45   573.2 2883.97   710.8 2887.61
   761.1 2889.53   804.5 2894.03   827.4 2893.99   897.2 2898.27  1022.3 2908.04
#Mann= 4 ,-1,0
       0      .1       0   252.5    .045       0   292.3      .1       0
     326     .05       0
#XS Ineff= 2 , 0
                          507.72         2897.29
Permanent Ineff=
       F       F
Bank Sta=252.5,292.3
XS Rating Curve= 0 ,0
Exp/Cntr(USF)=0,0
Exp/Cntr=0.3,0.1

Type RM Length L Ch R = 1 ,52540   ,435.4,418.8,364.7
XS GIS Cut Line= 4
2223329.41514374498253.4972237622223365.01352455 498455.22011229
 2223621.4051579499012.2479528862223667.51846652499189.420636878
#Sta/Elev= 30
       0 3001.91      24 2989.63   117.5  2947.4   126.4 2942.72   133.7 2936.17
     154 2931.19   158.1 2929.39   166.2 2923.43   190.6 2914.19   202.8 2907.36
   214.7 2905.49     229 2895.07   242.2 2882.85   253.9 2880.66   259.5 2877.59
     275 2876.38   303.9 2877.21   325.9  2881.4   343.5  2881.4   466.8 2879.89
   564.5 2880.51   607.7 2878.85   636.9 2881.42   748.6  2881.5   788.2 2883.21
     797    2882   805.9 2884.98   876.9 2898.63   914.1 2901.51  1001.1 2905.58
#Mann= 4 ,-1,0
       0      .1       0   259.5    .045       0   303.9      .1       0
   343.5     .05       0
#XS Ineff= 2 , 0
                          635.24         2883.51
Permanent Ineff=
       F       F
Bank Sta=259.5,303.9
XS Rating Curve= 0 ,0
Exp/Cntr(USF)=0,0
Exp/Cntr=0.3,0.1