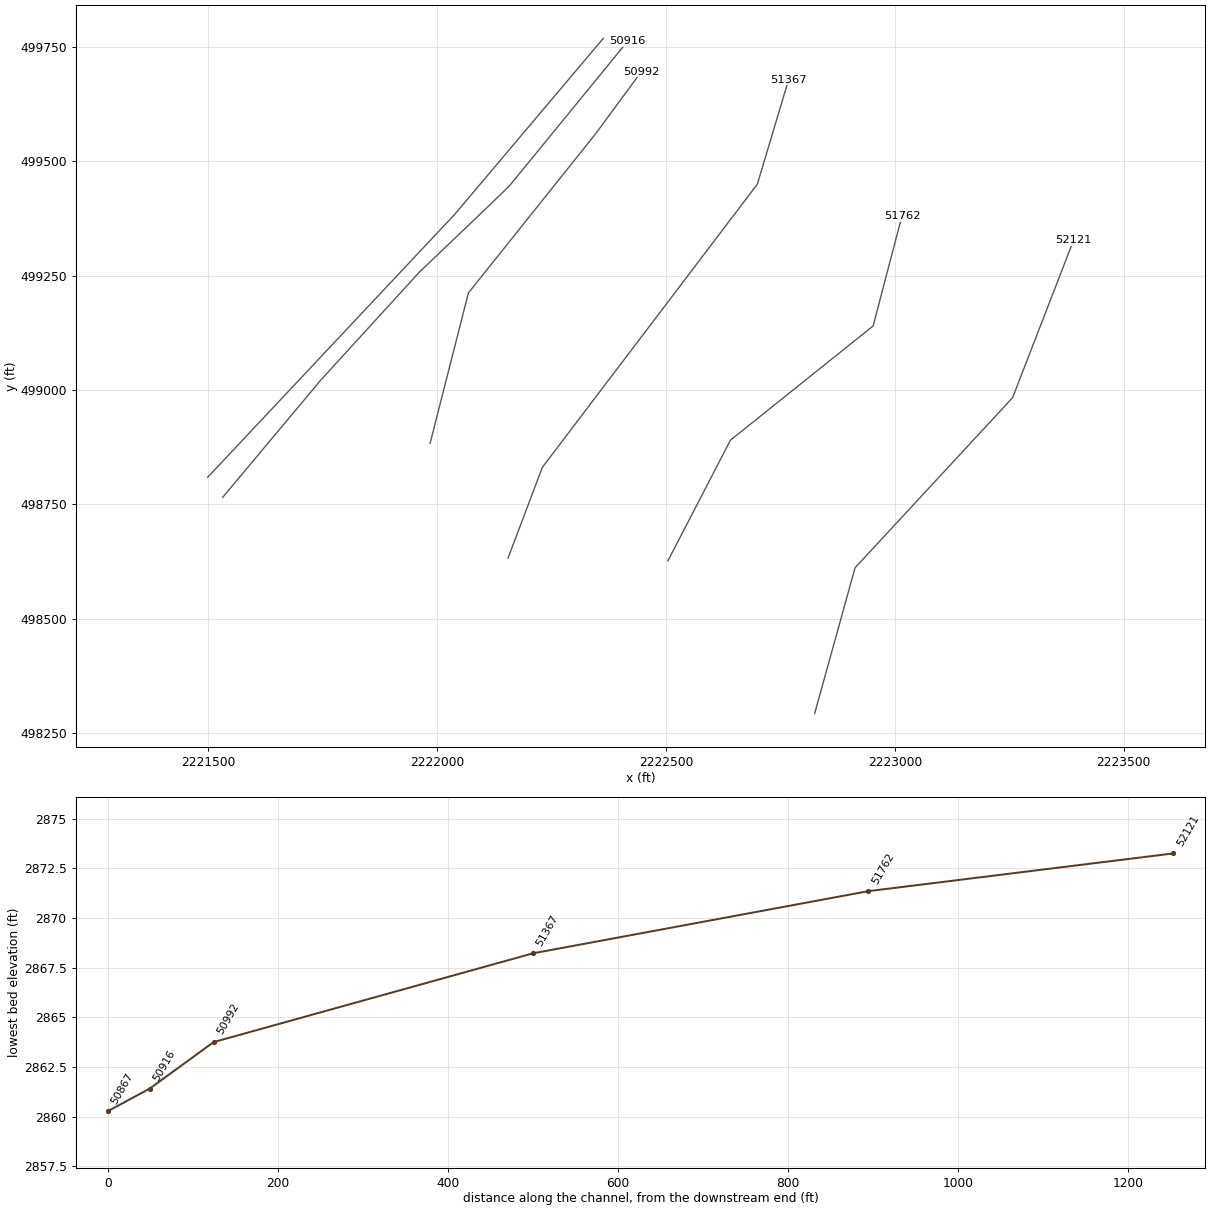
HEC-RAS study OLDFLDFK1.prj: OLDFLDFK1

--- OLDFLDFK1.g01 (geometry) --- (continued)

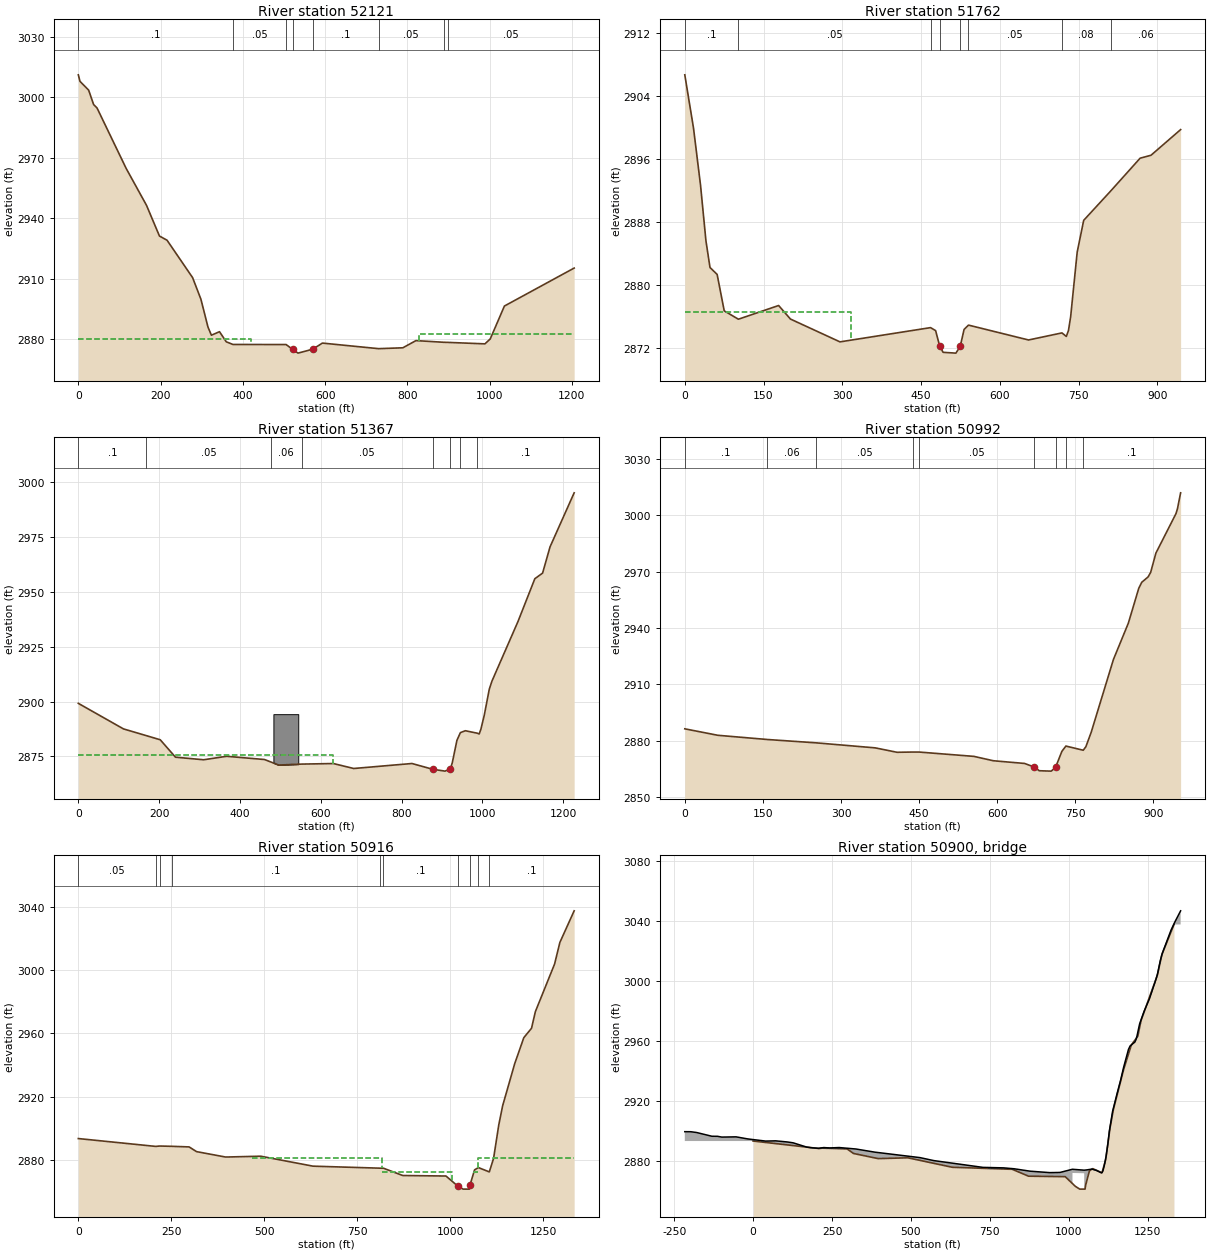
Type RM Length L Ch R = 1 ,52121   ,376.7,358.9,338.4
XS GIS Cut Line= 4
2222825.12749739498293.3488005992222913.31266572498611.507054969
 2223257.4077343498983.2680587152223390.55004727499327.363127299
#Sta/Elev= 30
       0 3011.09       4 3007.87    25.1 3003.51    37.2 2996.36    45.5 2994.67
   116.2 2964.78   165.9 2946.41   197.3 2931.23   215.7 2929.18   277.9 2910.64
   298.1 2899.94   315.3 2886.13   323.6 2882.12   343.3 2883.87   359.7 2878.87
     376 2877.53   505.1 2877.51  520.92 2875.17   534.1 2873.25   569.9 2875.19
   593.5 2878.22   730.3 2875.46   789.1 2875.89     821 2879.45   888.7 2878.62
   898.2 2878.57   988.8 2877.84  1001.7  2880.3  1036.1 2896.57  1205.7 2915.38
#Mann= 8 ,-1,0
       0      .1       0     376     .05       0   505.1      .1       0
  520.92    .045       0   569.9      .1       0   730.3     .05       0
   888.7     .07       0   898.2     .05       0
#XS Ineff= 2 , 0
          418.74 2880.03  828.17         2882.51
Permanent Ineff=
       F       F
Bank Sta=520.92,569.9
XS Rating Curve= 0 ,0
Exp/Cntr(USF)=0,0
Exp/Cntr=0.3,0.1

Type RM Length L Ch R = 1 ,51762   ,319.9,394.6,385
XS GIS Cut Line= 4
2222504.46180258498626.5227116592222641.23248987 498890.53363077
2222952.77685469499140.001999236 2223015.5965949499379.779483935
#Sta/Elev= 30
       0 2906.71    16.6 2899.94      30 2892.67    40.3  2885.6      48 2882.23
    61.6 2881.35    75.1 2876.72   102.1 2875.66   178.7  2877.4   201.2 2875.68
   295.5 2872.78     468 2874.59   477.7 2874.21   485.6  2872.2     492 2871.45
   516.3 2871.35  524.51  2872.2   531.9 2874.36   540.3 2874.91   654.7 2873.02
   718.3 2873.92   726.6 2873.47   730.7 2874.22   734.9    2876   747.3 2884.18
   759.7 2888.22     811 2891.94   867.2 2896.12   887.9 2896.49   944.3 2899.75
#Mann= 8 ,-1,0
       0      .1       0   102.1     .05       0     468      .1       0
   485.6    .045       0  524.51      .1       0   540.3     .05       0
   718.3     .08       0     811     .06       0
#XS Ineff= 2 , 0
           316.7 2876.52
Permanent Ineff=
       F       F
Bank Sta=485.6,524.51
XS Rating Curve= 0 ,0
Exp/Cntr(USF)=0,0
Exp/Cntr=0.3,0.1

Type RM Length L Ch R = 1 ,51367   ,359.4,375.8,373.1
XS GIS Cut Line= 4
2222155.42375487498632.726315648 2222230.2882539498830.930342893
2222699.92604215499449.9983364992222768.23699317499678.413078967
#Sta/Elev= 30
       0 2899.16   111.7  2887.5   202.7 2882.54   240.5 2874.58   310.1 2873.41
   367.2 2874.99   460.7 2873.52   495.9    2871   552.5 2871.43   631.4 2871.68
   681.6 2869.42   825.8  2871.7   877.4 2869.06   907.6 2868.22     921 2869.28
   925.7  2872.1   937.1 2882.26   945.7 2885.79   957.8 2886.66   987.9 2885.52
   992.2 2885.18   996.4 2887.33  1004.8 2893.74  1017.3 2905.67  1023.8  2909.3
  1088.3 2936.53    1130 2956.06  1149.2 2958.62  1167.6  2970.6  1227.3 2995.26
#Mann= 8 ,-1,0
       0      .1       0   168.7     .05       0     477     .06       0
   552.5     .05       0   877.4    .045       0     921      .1       0
   945.7    .016       0   987.9      .1       0
#XS Ineff= 2 , 0
          630.77 2875.76
Permanent Ineff=
       F       F
#Block Obstruct= 1 ,-1
  482.85   544.4 2894.22
Bank Sta=877.4,921
XS Rating Curve= 0 ,0
Exp/Cntr(USF)=0,0
Exp/Cntr=0.3,0.1

Type RM Length L Ch R = 1 ,50992   ,76.3,75.1,75.3
BEGIN DESCRIPTION:
xs 4
END DESCRIPTION:
XS GIS Cut Line= 4
2221985.20723725498883.7622553772222068.82260845499212.191417743
2222347.91023825499561.5525585992222446.21905346499695.506384178
#Sta/Elev= 30
       0 2886.27    63.4 2882.83   158.3 2880.59   252.6  2878.8   365.8 2876.13
   407.5 2873.78   438.8 2873.91   450.1  2873.9   555.2  2871.6   592.4 2869.28
   652.5 2867.84   671.1 2865.93   680.7 2863.96   703.7 2863.75     712 2865.72
   724.1 2874.25   731.9  2877.1   765.1 2874.87   770.2 2876.72   780.5 2884.47
   823.2 2923.21   851.8 2942.51   871.8 2961.07   877.5 2964.26   889.8 2967.15
   894.7 2969.59   904.7  2979.8   943.4 3000.89   946.2 3003.51   952.2  3011.9
#Mann= 9 ,-1,0
       0      .1       0   158.3     .06       0   252.6     .05       0
   438.8    .016       0   450.1     .05       0   671.1    .045       0
     712      .1       0   731.9    .016       0   765.1      .1       0
Bank Sta=671.1,712
XS Rating Curve= 0 ,0
Exp/Cntr(USF)=0,0
Exp/Cntr=0.5,0.3

Type RM Length L Ch R = 1 ,50916   ,50.2,49.4,49.2
BEGIN DESCRIPTION:
xs 3
END DESCRIPTION:
XS GIS Cut Line= 6
2221532.02006036498765.3579331722221746.77688206499022.132393899
2221961.59335325499257.5352205812222104.94577267499394.455159647
2222158.24346707499445.9150025182222416.46160719499762.025465865
#Sta/Elev= 30
       0 2893.42   208.4 2888.45   218.6 2888.69   252.7  2888.5   298.1 2888.13
     318 2885.15   396.2 2881.72   490.5 2882.25   631.3 2875.95   810.6 2874.68
   820.9 2874.64   872.8 2870.03   989.1  2869.7 1021.03  2863.3 1035.16 2861.41
 1051.97 2861.41  1053.9 2864.09  1065.9 2873.56  1076.2 2875.06  1105.6 2872.32
  1117.1 2880.82  1131.1 2902.07  1141.7 2914.36  1173.9 2940.78  1198.5  2957.3
  1219.2 2963.23  1229.5 2973.73  1281.2 3003.87  1295.5 3017.58  1333.9 3037.58
#Mann= 10 ,-1,0
       0     .05       0   208.4    .016       0   218.6     .07       0
   252.7      .1       0   810.6    .016       0   820.9      .1       0
 1021.03    .045       0  1053.9     .07       0  1076.2    .016       0
  1105.6      .1       0
#XS Ineff= 4 ,-1
  468.51     816 2881.41     816  1004.9 2872.39  1063.6    1074 2872.21
    1074  1333.9 2881.21
Permanent Ineff=
       F       F       F       F
Bank Sta=1021.03,1053.9
XS Rating Curve= 0 ,0
Exp/Cntr(USF)=0,0
Exp/Cntr=0.5,0.3

Type RM Length L Ch R = 3 ,50900   ,,,
BEGIN DESCRIPTION:
Bridge No.: 54075OLD050
JV notes: road deck updated based on surveyed data
channel burned per survey data
END DESCRIPTION:
Bridge Culvert--1,0,-1,-1, 0
Deck Dist Width WeirC Skew NumUp NumDn MinLoCord MaxHiCord MaxSubmerge Is_Ogee
10,12,2.6,0, 60, 60, , , 0.98, 0, 0,0,,
  -216.5 -197.73-178.874-130.398 -113.35 -99.143 -54.107 -16.742  39.763  71.146
 108.111 126.594  169.72 182.041 206.685 223.837 243.056  272.61 325.806 385.823
 528.843 572.672 728.234 793.843 826.999 878.153 940.393   972.6  1011.6 1012.06
 1049.31 1058.131073.481 1088.621103.7581106.4071108.8051112.9691118.8971123.943
1128.9891139.214 1154.221164.3131174.4051189.544 1194.591209.7281213.3021216.154
1224.8671238.9741256.0881276.999 1281.761290.4681296.6831324.5461335.8831354.835
2899.6572899.6282899.0922896.5992896.5892896.0572896.2142894.8282893.3932893.559
2892.812 2892.252889.4022888.9982888.5862889.0762888.8262889.0932888.1252886.026
2882.3882880.4042875.8922875.5642874.9692873.3492872.393 2872.52 2874.63 2874.63
 2874.03 2874.242874.7482873.8082872.2132872.6632873.6762877.1122883.5052890.962
2900.1022913.1912925.6812933.6382942.6992954.4132956.7052959.2962960.903 2962.97
 2971.41 2979.732988.1483001.2453004.8263013.5893018.3573033.8813038.9733046.671
                                                                                
                                                                                
                                                                         2872.16
 2871.97
                                                                                
                                                                                
  -226.5 -207.73-188.874-140.398 -123.35-109.143 -64.107 -26.742  29.763  61.146
  98.111 116.594  159.72 172.041 196.685 213.837 233.056  262.61 315.806 375.823
 518.843 562.672 718.234 783.843 816.999 868.153 930.393   962.6  1001.6 1002.06
 1039.31 1048.131063.481 1078.621093.7581096.4071098.8051102.9691108.8971113.943
1118.9891129.214 1144.221154.3131164.4051179.544 1184.591199.7281203.3021206.154
1214.8671228.9741246.0881266.999 1271.761280.4681286.6831314.5461325.8831344.835
2899.6572899.6282899.0922896.5992896.5892896.0572896.2142894.8282893.3932893.559
2892.812 2892.252889.4022888.9982888.5862889.0762888.8262889.0932888.1252886.026
2882.3882880.4042875.8922875.5642874.9692873.3492872.393 2872.52 2874.63 2874.63
 2874.03 2874.242874.7482873.8082872.2132872.6632873.6762877.1122883.5052890.962
2900.1022913.1912925.6812933.6382942.6992954.4132956.7052959.2962960.903 2962.97
 2971.41 2979.732988.1483001.2453004.8263013.5893018.3573033.8813038.9733046.671
                                                                                
                                                                                
                                                                         2872.16
 2871.97
                                                                                
                                                                                
BR Coef=-1 ,-1 , 0 ,, 0 ,,,0.8,0,1,0,
WSPro=,,,, 1 ,,,, 0 ,,,, 0 ,,,,-1 ,-1 ,-1 , 0 , 0 , 0 , 0 , 0
BR U #Sta/Elev= 30
       0 2893.42   208.4 2888.45   218.6 2888.69   252.7  2888.5   298.1 2888.13
     318 2885.15   396.2 2881.72   490.5 2882.25   631.3 2875.95   810.6 2874.68
   820.9 2874.64   872.8 2870.03   989.1  2869.7 1021.03  2863.3 1035.16 2861.41
 1051.97 2861.41  1053.9 2864.09  1065.9 2873.56  1076.2 2875.06  1105.6 2872.32
  1117.1 2880.82  1131.1 2902.07  1141.7 2914.36  1173.9 2940.78  1198.5  2957.3
  1219.2 2963.23  1229.5 2973.73  1281.2 3003.87  1295.5 3017.58  1333.9 3037.58
BR U #Mann= 10
       0     .05   208.4    .016   218.6     .07   252.7      .1   810.6    .016
   820.9      .1 1021.03     .04  1053.9     .07  1076.2    .016  1105.6      .1
BR D #Sta/Elev= 30
       0 2893.59   115.2 2892.77   195.9 2889.16   207.2 2889.03     309 2887.09
   381.1 2882.39   416.6 2883.98   451.2    2881   566.6 2879.12   743.4 2872.16
   888.8 2870.93   967.9 2868.93     986 2868.89 1003.02 2862.05 1020.71 2860.27
 1036.72 2861.32 1038.61 2862.97  1051.3 2872.58  1059.8 2873.89    1088 2871.73
  1093.9 2874.47    1104 2883.34  1113.7 2898.27  1124.9 2911.15  1170.5  2952.3
    1193 2958.72  1203.4 2968.11  1219.1 2977.68  1235.8 2985.41  1291.6    3024
BR D #Mann= 9
       0     .05   195.9    .016   207.2     .05   888.8     .07   967.9     .06
 1003.02     .04 1038.61     .07  1059.8    .016    1088      .1
BC Design=,, 0 ,, 0 ,,,,,,
BC Use User HTab Curves=0
BC User HTab FreeFlow(D)= 0

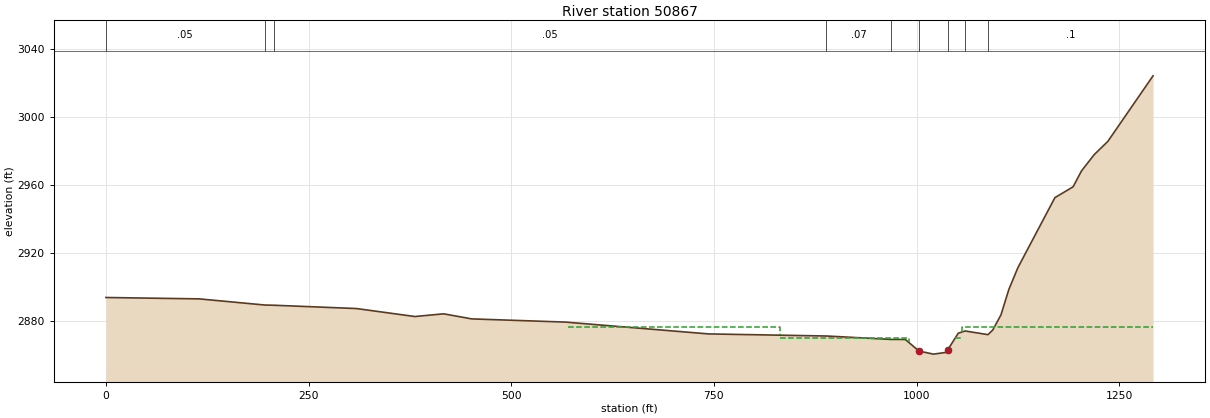
Type RM Length L Ch R = 1 ,50867   ,132.4,131.1,131.8
BEGIN DESCRIPTION:
xs 2
END DESCRIPTION:
XS GIS Cut Line= 4
2221499.30114272498809.2112139152221736.00050925499061.317048083
2222038.52751025499383.4522806322222363.46391873499768.613971723
#Sta/Elev= 30
       0 2893.59   115.2 2892.77   195.9 2889.16   207.2 2889.03     309 2887.09
   381.1 2882.39   416.6 2883.98   451.2    2881   566.6 2879.12   743.4 2872.16
   888.8 2870.93   967.9 2868.93     986 2868.89 1003.02 2862.05 1020.71 2860.27
 1036.72 2861.32 1038.61 2862.97  1051.3 2872.58  1059.8 2873.89    1088 2871.73
  1093.9 2874.47    1104 2883.34  1113.7 2898.27  1124.9 2911.15  1170.5  2952.3
    1193 2958.72  1203.4 2968.11  1219.1 2977.68  1235.8 2985.41  1291.6    3024
#Mann= 9 ,-1,0
       0     .05       0   195.9    .016       0   207.2     .05       0
   888.8     .07       0   967.9     .06       0 1003.02    .045       0
 1038.61     .07       0  1059.8    .016       0    1088      .1       0
#XS Ineff= 4 ,-1
  570.25     831    2876     831     990  2869.9  1047.3    1056  2869.9
    1056  1291.6    2876
Permanent Ineff=
       F       F       F       F
Bank Sta=1003.02,1038.61
XS Rating Curve= 0 ,0
Exp/Cntr(USF)=0,0
Exp/Cntr=0.5,0.3