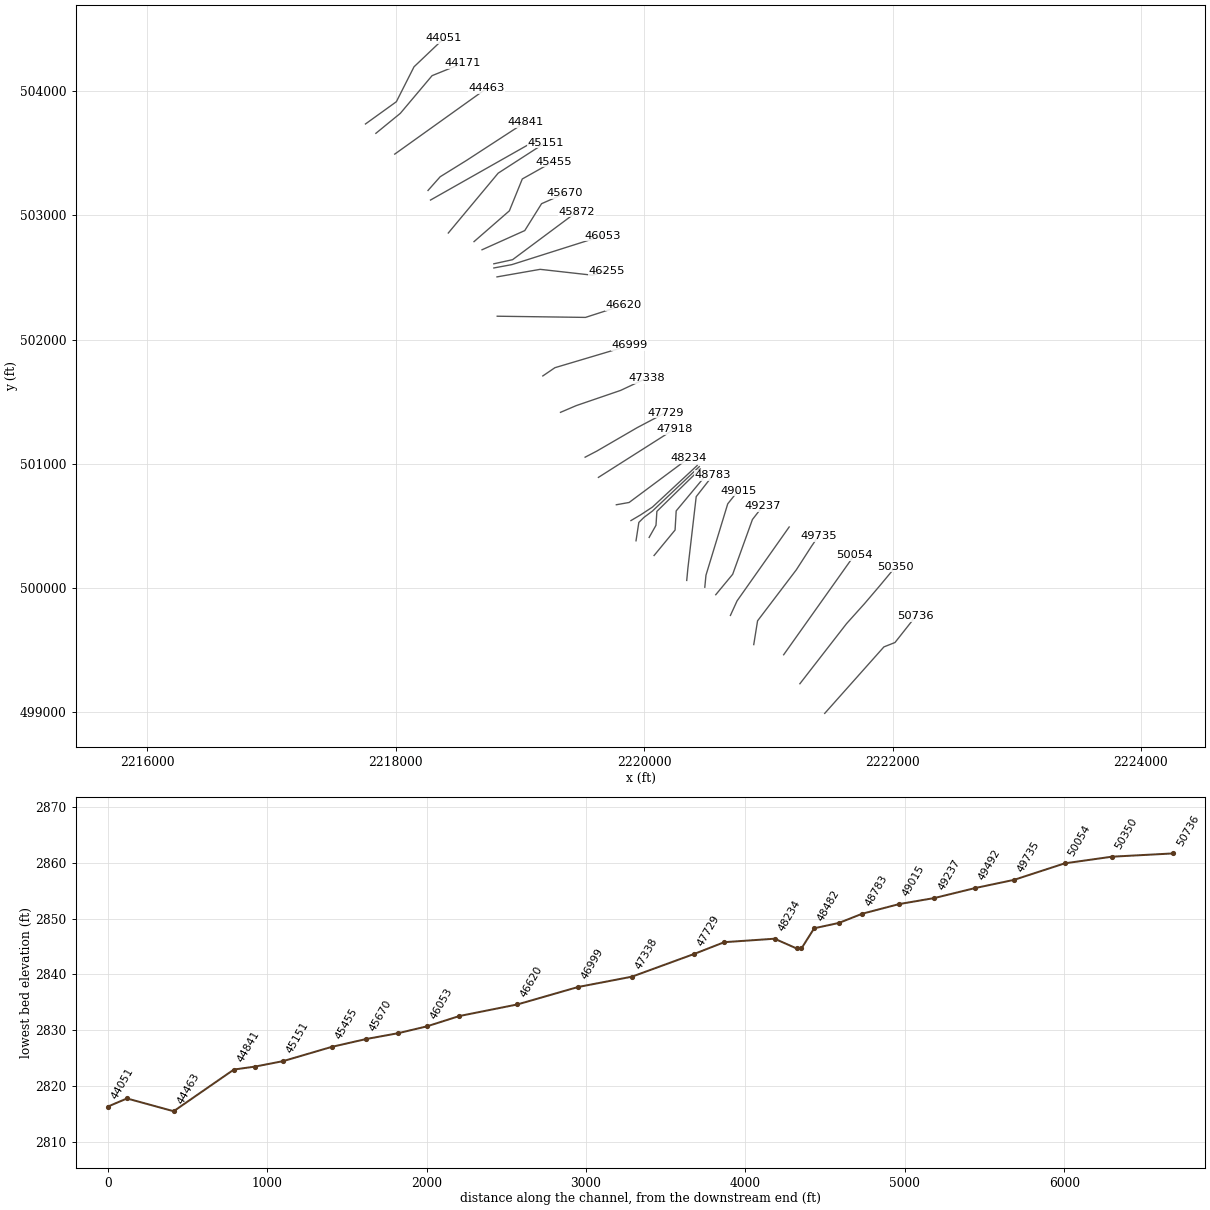
HEC-RAS study OLDFLDFK1.prj: OLDFLDFK1

--- OLDFLDFK1.g01 (geometry) --- (continued)

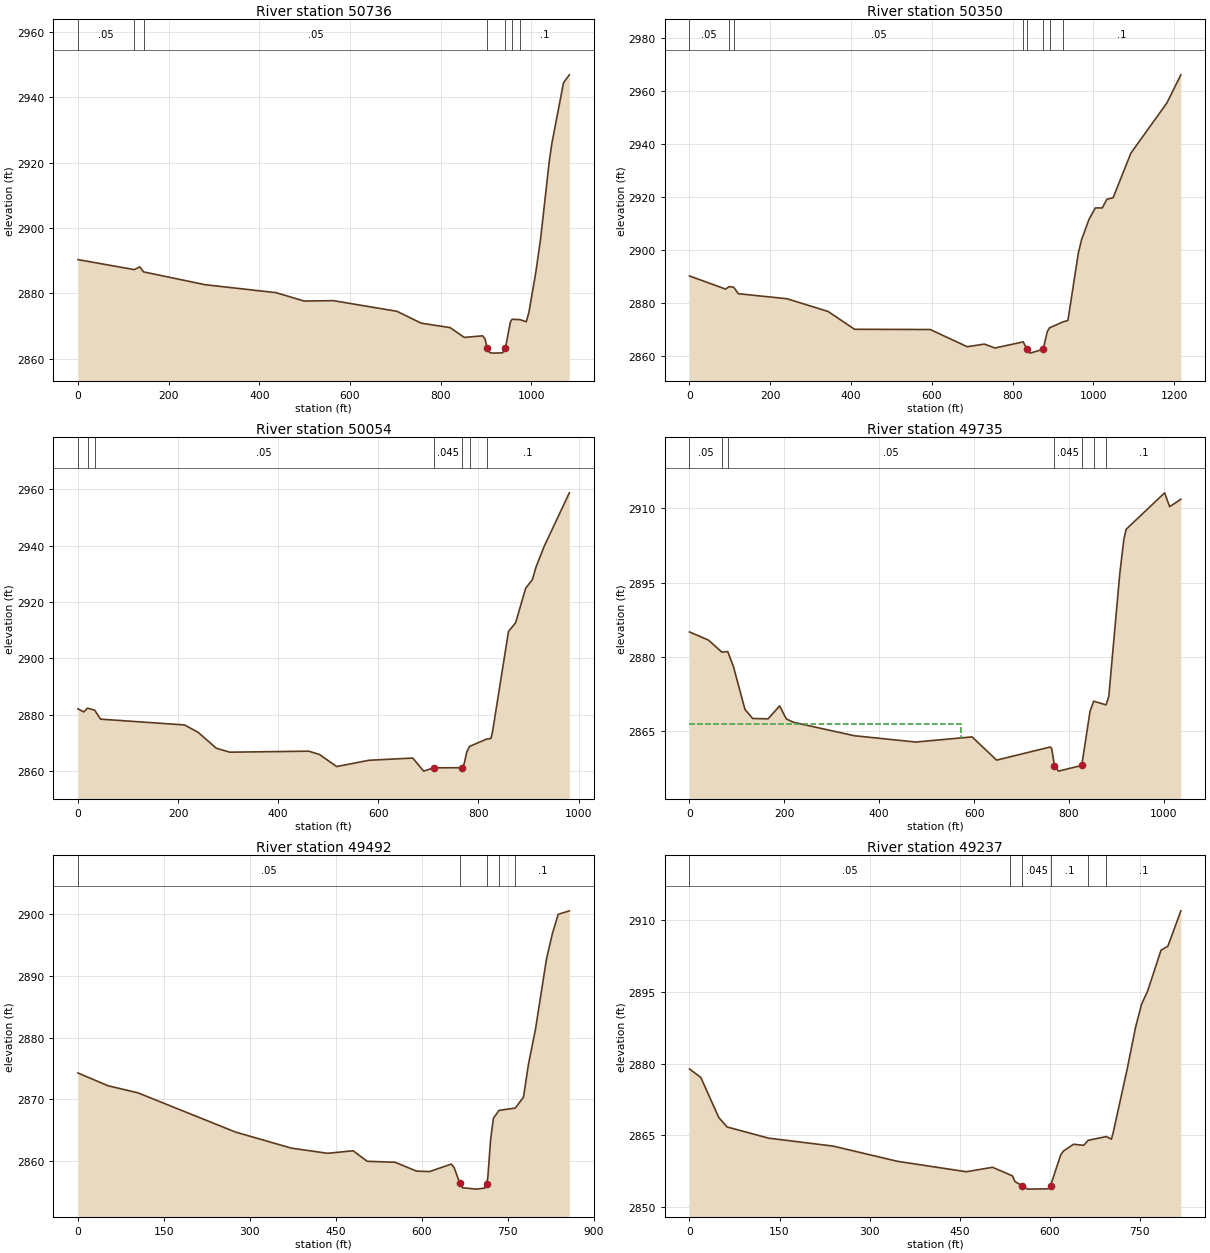
Type RM Length L Ch R = 1 ,50736   ,395.7,385.8,384.9
BEGIN DESCRIPTION:
xs 1
END DESCRIPTION:
XS GIS Cut Line= 4
2221453.63437121498987.3358319272221930.08536945499522.942746698
2222019.50216009499558.4256001262222187.58346835499771.248224544
#Sta/Elev= 30
       0 2890.31   124.2 2887.25   136.3 2888.09   144.8 2886.55   280.7 2882.63
   437.1  2880.2   498.9 2877.64   563.5 2877.76   703.8  2874.5   757.2 2870.88
   821.2 2869.51   852.5 2866.51     893    2867   898.1 2866.03   903.2  2863.2
   908.3 2861.88   915.2 2861.71   936.8  2861.8   943.2  2863.3   954.2 2871.25
   957.9 2872.06   975.5 2871.94   989.2 2871.29     995 2874.16  1010.3 2886.44
  1020.7 2896.56    1040 2920.46  1045.9 2926.02  1071.4 2944.42  1084.2 2946.82
#Mann= 7 ,-1,0
       0     .05       0   124.2    .016       0   144.8     .05       0
   903.2    .045       0   943.2     .06       0   957.9    .016       0
   975.5      .1       0
Bank Sta=903.2,943.2
XS Rating Curve= 0 ,0
Exp/Cntr(USF)=0,0
Exp/Cntr=0.3,0.1

Type RM Length L Ch R = 1 ,50350   ,283.2,295.8,297.5
XS GIS Cut Line= 5
2221253.59845982499226.1127188432221629.91769998499711.119471809
2221773.76030509499871.1940754012221892.56260476 500010.62815753
 2222023.5402463500167.815171171
#Sta/Elev= 30
       0 2890.28    89.5 2885.31    98.1 2886.25   109.5 2886.01   120.9 2883.57
   241.8 2881.66   343.3 2876.86   408.8 2870.13   596.2 2870.04   687.7 2863.55
   730.2 2864.53   756.5 2863.06   826.5 2865.37  835.512862.721   843.6 2861.12
     876 2862.58   886.1 2869.27   891.8 2870.68   925.3 2872.95   937.2 2873.45
   963.1 2898.99   971.2 2904.06   989.3 2911.61  1005.1 2915.98  1022.3 2915.98
  1033.7 2919.25  1049.2 2919.84  1093.3 2936.72  1182.2 2955.61  1216.9 2966.27
#Mann= 8 ,-1,0
       0     .05       0    98.1    .016       0   109.5     .05       0
   826.5      .1       0  835.51    .045       0     876      .1       0
   891.8    .016       0   925.3      .1       0
Bank Sta=835.51,876
XS Rating Curve= 0 ,0
Exp/Cntr(USF)=0,0
Exp/Cntr=0.3,0.1

Type RM Length L Ch R = 1 ,50054   ,314.5,319.3,320.3
XS GIS Cut Line= 2
2221122.94856668499459.7203122362221690.78334703500260.239269487
#Sta/Elev= 30
       0 2882.05    11.6 2880.96    19.1 2882.29    33.5 2881.57      45 2878.39
   212.7 2876.34   240.1  2873.7   276.4 2868.05   303.2 2866.66     461 2867.01
   482.4 2865.84   516.7 2861.55   581.5 2863.79   668.7 2864.57   690.5 2859.93
   710.6 2861.11     768 2861.14   771.7 2862.73   776.6 2866.73   782.3 2868.71
   816.7 2871.34   824.9 2871.52   828.2 2874.02     860 2909.56   874.1 2912.57
   894.3 2924.89   907.8 2927.97   914.7  2932.3   931.5 2939.85   981.5 2958.77
#Mann= 7 ,-1,0
       0     .05       0    19.1    .016       0    33.5     .05       0
   710.6    .045       0     768      .1       0   782.3    .016       0
   816.7      .1       0
Bank Sta=710.6,768
XS Rating Curve= 0 ,0
Exp/Cntr(USF)=0,0
Exp/Cntr=0.3,0.1

Type RM Length L Ch R = 1 ,49735   ,245.2,242.6,241.3
XS GIS Cut Line= 5
2220882.08471258499541.6484650842220912.85015355499733.138912462
2221225.41499321500144.9645396432221346.66822226500333.271561387
2221403.44476746500416.656821802
#Sta/Elev= 30
       0 2885.05      40  2883.4    68.4 2880.96    80.6 2881.09    92.7 2878.04
     117  2869.4   133.2 2867.58   165.6 2867.51     190 2870.12     204 2867.51
   219.3 2866.81   347.7  2864.1   477.3 2862.83   595.7 2863.87   647.4 2859.18
   760.4 2861.83   763.5 2861.51  769.42 2858.07   777.8 2856.96   826.9 2858.11
   844.4 2869.05     852 2871.07   878.1 2870.33   883.9 2872.04     907 2896.72
   915.5 2903.62   920.5 2905.76  1001.6 2913.12  1012.2 2910.33  1035.8 2911.82
#Mann= 7 ,-1,0
       0     .05       0    68.4    .016       0    80.6     .05       0
  769.42    .045       0   826.9     .06       0     852    .016       0
   878.1      .1       0
#XS Ineff= 2 , 0
          571.43 2866.48
Permanent Ineff=
       F       F
Bank Sta=769.42,826.9
XS Rating Curve= 0 ,0
Exp/Cntr(USF)=0,0
Exp/Cntr=0.3,0.1

Type RM Length L Ch R = 1 ,49492   ,223.1,255.7,262.5
XS GIS Cut Line= 3
2220694.25590604499776.718953043 2220747.8236602 499893.96849391
2221167.38143502500489.489996818
#Sta/Elev= 30
       0 2874.27    52.7  2872.2   104.4 2871.07     275 2864.72   372.6 2862.12
   435.7 2861.29   480.2  2861.7   504.6    2860   553.4 2859.84   590.8 2858.41
   613.7 2858.34   651.5 2859.55   656.4 2858.98   666.2 2856.46   671.1 2855.72
   695.5  2855.5   710.2 2855.68   712.9 2856.39   715.1 2857.32     720 2863.47
   724.9 2866.95   734.7 2868.23     763  2868.6   777.4 2870.36     786 2875.64
   798.3 2881.32   817.5 2892.67   827.6 2896.72   837.9 2899.91   857.4 2900.48
#Mann= 5 ,-1,0
       0     .05       0   666.2    .045       0   712.9      .1       0
   734.7    .016       0     763      .1       0
Bank Sta=666.2,712.9
XS Rating Curve= 0 ,0
Exp/Cntr(USF)=0,0
Exp/Cntr=0.3,0.1

Type RM Length L Ch R = 1 ,49237   ,217.7,222,227.5
XS GIS Cut Line= 4
2220576.17639804499943.5893106032220712.51671633500108.370486172
 2220871.4562049500549.642124275 2220954.8716258500656.817750155
#Sta/Elev= 30
       0 2878.86    18.8  2877.1    48.8 2868.69    62.7 2866.72   131.8 2864.38
   239.2 2862.72   346.5 2859.53   461.2 2857.35   504.9 2858.28   537.9  2856.5
   542.4 2855.29   554.7 2854.38   563.4 2853.71   597.4 2853.77   601.6 2854.44
   618.6  2860.9   622.9 2861.66   639.9  2863.1   656.9 2862.88   664.3 2863.93
   694.5 2864.71     703 2864.16   705.9 2865.51   729.7 2879.09   743.1 2887.51
   753.3 2892.43   763.4 2895.18   785.7 2903.73   797.1 2904.55   818.7 2911.96
#Mann= 6 ,-1,0
       0     .05       0   533.5      .1       0   554.7    .045       0
   601.6      .1       0   664.3    .016       0   694.5      .1       0
Bank Sta=554.7,601.6
XS Rating Curve= 0 ,0
Exp/Cntr(USF)=0,0
Exp/Cntr=0.3,0.1

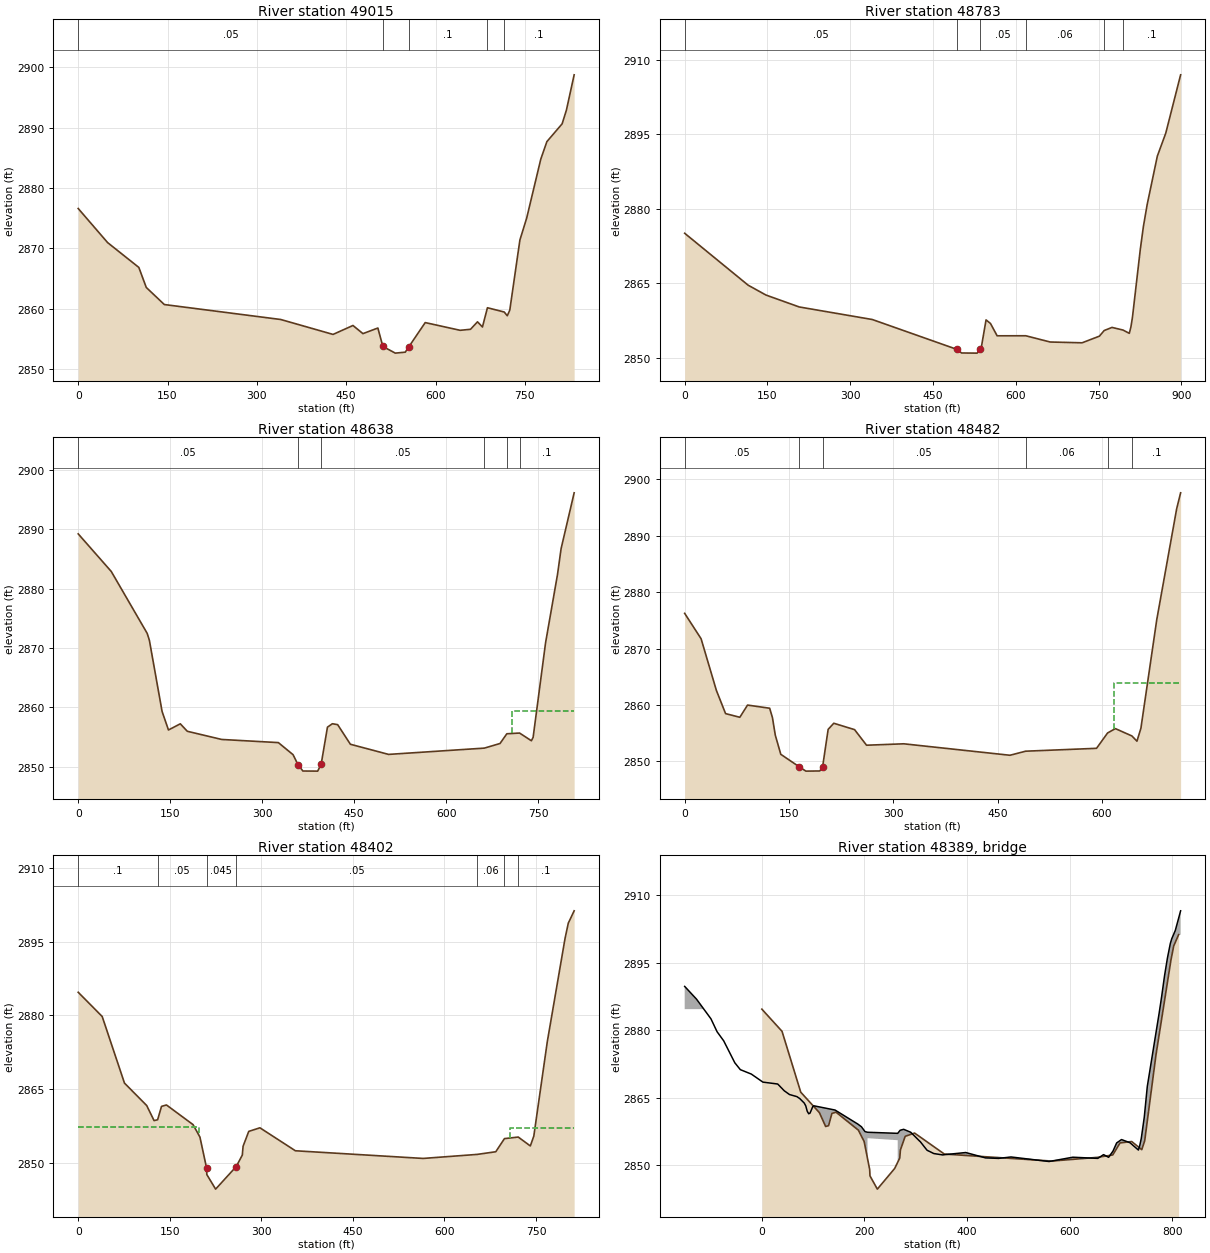
Type RM Length L Ch R = 1 ,49015   ,218.2,231.6,262.2
XS GIS Cut Line= 4
2220487.93162924500004.051917699 2220497.3047798500100.626309531
2220672.60001094500676.0105834612220756.33954503500781.039829608
#Sta/Elev= 30
       0 2876.58    49.4 2870.93   101.8 2866.82   114.3  2863.5   144.6 2860.67
   340.2 2858.19   427.9 2855.72   461.4  2857.2   478.1 2855.85   503.2 2856.78
   511.6 2853.72   532.5 2852.62   549.2 2852.78   554.9 2853.63   582.7 2857.68
   641.4  2856.4   658.8 2856.57   670.5 2857.81   678.8 2856.95   687.2 2860.14
   715.4 2859.43   720.5 2858.81   724.7 2859.73   741.7 2871.36   753.1    2875
   776.8 2884.77     787 2887.66   812.6 2890.61   819.8 2892.88   832.8 2898.73
#Mann= 5 ,-1,0
       0     .05       0   511.6    .045       0   554.9      .1       0
   687.2    .016       0   715.4      .1       0
Bank Sta=511.6,554.9
XS Rating Curve= 0 ,0
Exp/Cntr(USF)=0,0
Exp/Cntr=0.3,0.1

Type RM Length L Ch R = 1 ,48783   ,141.5,145,62
XS GIS Cut Line= 4
2220342.42248637500058.6428509412220351.61879185500155.779875468
2220418.71002655500733.9724911832220553.52480557500906.410818947
#Sta/Elev= 30
       0 2875.04   115.1 2864.57   147.3 2862.59   207.6 2860.19     340 2857.66
   492.6 2851.67   501.7 2850.92   529.9 2850.89   535.9  2851.8   535.9 2851.82
   537.9 2852.35     546 2857.58     554 2856.87   566.1 2854.38   617.9 2854.39
   662.2 2853.13     720 2852.97   751.4 2854.31     760 2855.44   774.2 2856.07
   794.1 2855.54   805.5 2854.88   808.4 2856.14   811.2 2858.07   825.4 2871.74
   831.1 2876.42   837.9 2880.82   856.3 2890.57   871.6 2895.21   898.5 2906.96
#Mann= 6 ,-1,0
       0     .05       0   492.6    .045       0   535.9     .05       0
   617.9     .06       0     760    .016       0   794.1      .1       0
Bank Sta=492.6,535.9
XS Rating Curve= 0 ,0
Exp/Cntr=0.3,0.1

Type RM Length L Ch R = 1 ,48638   ,155.6,156.3,94.4
XS GIS Cut Line= 4
2220079.45200711  500259.55294712220248.48896892500464.893149031
2220257.56477895500619.1819195432220506.01507852500917.549174282
#Sta/Elev= 30
       0 2889.26    53.9 2882.92   112.5 2872.48   116.1  2871.3   136.8 2859.31
   147.2 2856.19   166.5 2857.23   177.9 2855.97     234 2854.59   326.4 2854.06
   350.4 2852.02   358.4 2850.35   366.4 2849.27   390.5 2849.25  396.22 2850.42
   406.5 2856.67   414.5 2857.24   423.1 2857.09   443.9 2853.78   506.2 2852.07
   662.4 2853.13   687.9 2853.91     699 2855.55   719.8 2855.67   739.1 2854.37
   741.9 2854.95   762.2  2870.9   781.7 2882.44   787.5 2886.76   808.8 2896.18
#Mann= 6 ,-1,0
       0     .05       0   358.4    .045       0  396.22     .05       0
   662.4     .06       0     699    .016       0   719.8      .1       0
#XS Ineff= 2 , 0
                          707.04         2859.37
Permanent Ineff=
       F       F
Bank Sta=358.4,396.22
XS Rating Curve= 0 ,0
Exp/Cntr(USF)=0,0
Exp/Cntr=0.3,0.1

Type RM Length L Ch R = 1 ,48482   ,105.2,79.6,23.8
BEGIN DESCRIPTION:
xs 4
END DESCRIPTION:
XS GIS Cut Line= 4
2220039.78063563500405.4894711612220094.84099232500503.143688696
2220102.11311491500615.3421513972220451.17499886500957.131912771
#Sta/Elev= 30
       0 2876.23    23.6 2871.73    45.6 2862.58    58.8 2858.47    79.3 2857.82
    90.4 2859.98   122.2 2859.42   126.2 2857.76   130.3 2854.65   138.2 2851.26
   164.3 2849.08   174.3 2848.28   194.3 2848.31   198.3 2849.03   206.3 2855.68
   214.4 2856.76   244.3 2855.63   261.5 2852.87     315 2853.12   467.7 2851.09
   490.2 2851.81   592.2 2852.32   608.1 2855.04   619.3 2855.81   643.1 2854.51
   650.3 2853.58     656 2855.87   678.8 2875.11   707.4 2894.74   713.1 2897.58
#Mann= 6 ,-1,0
       0     .05       0   164.3    .045       0   198.3     .05       0
   490.2     .06       0   608.1    .016       0   643.1      .1       0
#XS Ineff= 2 , 0
                          617.92         2863.97
Permanent Ineff=
       F       F
Bank Sta=164.3,198.3
XS Rating Curve= 0 ,0
Exp/Cntr(USF)=0,0
Exp/Cntr=0.5,0.3

Type RM Length L Ch R = 1 ,48402   ,32.2,31.2,21.9
BEGIN DESCRIPTION:
xs 3
channel burned per available survey data
END DESCRIPTION:
XS GIS Cut Line= 5
2219934.05135887500378.292053343 2219956.8278529500526.339264505
2219997.69156277 500566.533077492220066.69094173500618.115137487
2220443.40968714500975.406873297
#Sta/Elev= 30
       0  2884.7    39.3 2879.77    75.8 2866.23   112.2 2861.67   124.3  2858.6
   130.1 2858.78   136.5  2861.5   144.6 2861.78   188.1 2857.79   199.4 2855.26
   210.2 2849.02  210.72 2847.63  225.11 2844.67  258.88 2849.26  268.85 2851.59
   270.1 2853.38   279.4 2856.41   297.7 2857.14   355.8 2852.47   565.1 2850.91
   653.6 2851.73   684.1 2852.27   698.3 2854.94   720.9 2855.26   740.7 2853.45
   746.4 2855.45   768.5 2874.64   797.6 2895.66   802.9 2898.75   812.5 2901.26
#Mann= 7 ,-1,0
       0      .1       0   130.1     .05       0   210.2    .045       0
  258.88     .05       0   653.6     .06       0   698.3    .016       0
   720.9      .1       0
#XS Ineff= 3 ,-1
       0     198 2857.32     273     708 2852.29     708   812.5 2857.06
Permanent Ineff=
       F       F       F
Bank Sta=210.2,258.88
XS Rating Curve= 0 ,0
Exp/Cntr(USF)=0,0
Exp/Cntr=0.5,0.3

Type RM Length L Ch R = 3 ,48389   ,,,
BEGIN DESCRIPTION:
Bridge No.: 54075OLD040
JV notes: road deck cut from surveyed data
only partial survey - US xs obtained, US xs burned based on available survey data - "Abandon bridge. Deck heavily damaged. Shots on Upstream only"
DS invert assumed based on imagery and available survey data, and dropped
END DESCRIPTION:
Bridge Culvert--1,0,-1,-1, 0
Deck Dist Width WeirC Skew NumUp NumDn MinLoCord MaxHiCord MaxSubmerge Is_Ogee
8,12,2.6,0, 60, 60, , , 0.98, 0, 0,0,,
  -150.5-127.515 -99.253 -87.318 -74.446 -52.741 -42.017 -20.554   2.006  30.821
  43.837  53.872  68.279  74.042  82.686  85.568  88.449  91.331  93.918  99.235
 101.072 142.655 186.926  194.08  200.99     206  264.82 269.513 276.365  290.07
  309.04 322.031 335.162 352.138 397.453 436.019 461.272  485.72 559.901 606.314
 654.872 666.189 675.934 684.525 691.653 701.092 717.659 734.092 736.921 739.748
 745.555 751.357 774.563 779.361 785.019 790.678 796.336 799.166 806.016 816.367
2889.7592886.9392882.5442879.6732877.6542872.7652871.245 2870.262868.4712868.051
2866.5272865.7072865.2462864.7952863.7962863.1852861.9782861.434 2861.592863.024
 2863.212862.2622859.1492858.5432857.475 2857.32 2857.082857.7612857.977 2857.33
2855.1882853.3212852.5842852.2832852.8122851.6162851.5052851.8242850.8132851.771
2851.5062852.3472851.747 2853.132854.9452855.6982854.9892853.362 2854.492855.998
2860.7262867.4862883.862 2887.482892.1392896.0972899.3342900.3912902.2122906.572
                                                                                
                                                                                
                                            2856 2855.55
                                                                                
                                                                                
                                                                                
  -261.5-238.515-210.253-198.318-185.446-163.741-153.017-131.554-108.994 -80.179
 -67.163 -57.128 -42.721 -36.958 -28.314 -25.432 -22.551 -19.669 -17.082 -11.765
  -9.928  31.655  75.926   83.08   89.99      95  153.82 158.513 165.365  179.07
  198.04 211.031 224.162 241.138 286.453 325.019 350.272  374.72 448.901 495.314
 543.872 555.189 564.934 573.525 580.653 590.092 606.659 623.092 625.921 628.748
 634.555 640.357 663.563 668.361 674.019 679.678 685.336 688.166 695.016 705.367
2889.7592886.9392882.5442879.6732877.6542872.7652871.245 2870.262868.4712868.051
2866.5272865.7072865.2462864.7952863.7962863.1852861.9782861.434 2861.592863.024
 2863.212862.2622859.1492858.5432857.475 2857.32 2857.082857.7612857.977 2857.33
2855.1882853.3212852.5842852.2832852.8122851.6162851.5052851.8242850.8132851.771
2851.5062852.3472851.747 2853.132854.9452855.6982854.9892853.362 2854.492855.998
2860.7262867.4862883.862 2887.482892.1392896.0972899.3342900.3912902.2122906.572
                                                                                
                                                                                
                                            2856 2855.55
                                                                                
                                                                                
                                                                                
BR Coef=-1 ,-1 , 0 ,, 0 ,,,0.8,0,1,0,
WSPro=,,,, 1 ,,,, 0 ,,,, 0 ,,,,-1 ,-1 ,-1 , 0 , 0 , 0 , 0 , 0
BR U #Sta/Elev= 30
       0  2884.7    39.3 2879.77    75.8 2866.23   112.2 2861.67   124.3  2858.6
   130.1 2858.78   136.5  2861.5   144.6 2861.78   188.1 2857.79   199.4 2855.26
   210.2 2849.02  210.72 2847.63  225.11 2844.67  258.88 2849.26  268.85 2851.59
   270.1 2853.38   279.4 2856.41   297.7 2857.14   355.8 2852.47   565.1 2850.91
   653.6 2851.73   684.1 2852.27   698.3 2854.94   720.9 2855.26   740.7 2853.45
   746.4 2855.45   768.5 2874.64   797.6 2895.66   802.9 2898.75   812.5 2901.26
BR U #Mann= 7
       0      .1   130.1     .05   210.2     .04  258.88     .05   653.6     .06
   698.3    .016   720.9      .1
BR D #Sta/Elev= 30
       0 2864.93    12.8 2864.68    78.2 2859.67    86.8 2856.21    97.9 2848.95
   104.3 2844.67   127.4 2844.67  140.34 2848.68   152.5 2852.25   159.8 2855.91
   167.1 2856.77   221.1 2852.27   279.9 2852.74   349.7 2851.18   392.8 2851.57
   452.9 2850.75   547.8 2851.42   565.3 2852.27     579 2852.95   587.5 2854.99
   597.1 2855.65   612.9 2854.92   627.6 2853.62   633.1 2854.85   638.6 2858.86
     644 2864.68   671.3 2884.52   683.7 2895.24   691.1 2899.68   696.2 2901.67
BR D #Mann= 6
       0     .05    97.9     .04  140.34     .05   565.3     .06   587.5    .016
   612.9      .1
BC Design=,, 0 ,, 0 ,,,,,,
BC Use User HTab Curves=0
BC User HTab FreeFlow(D)= 0

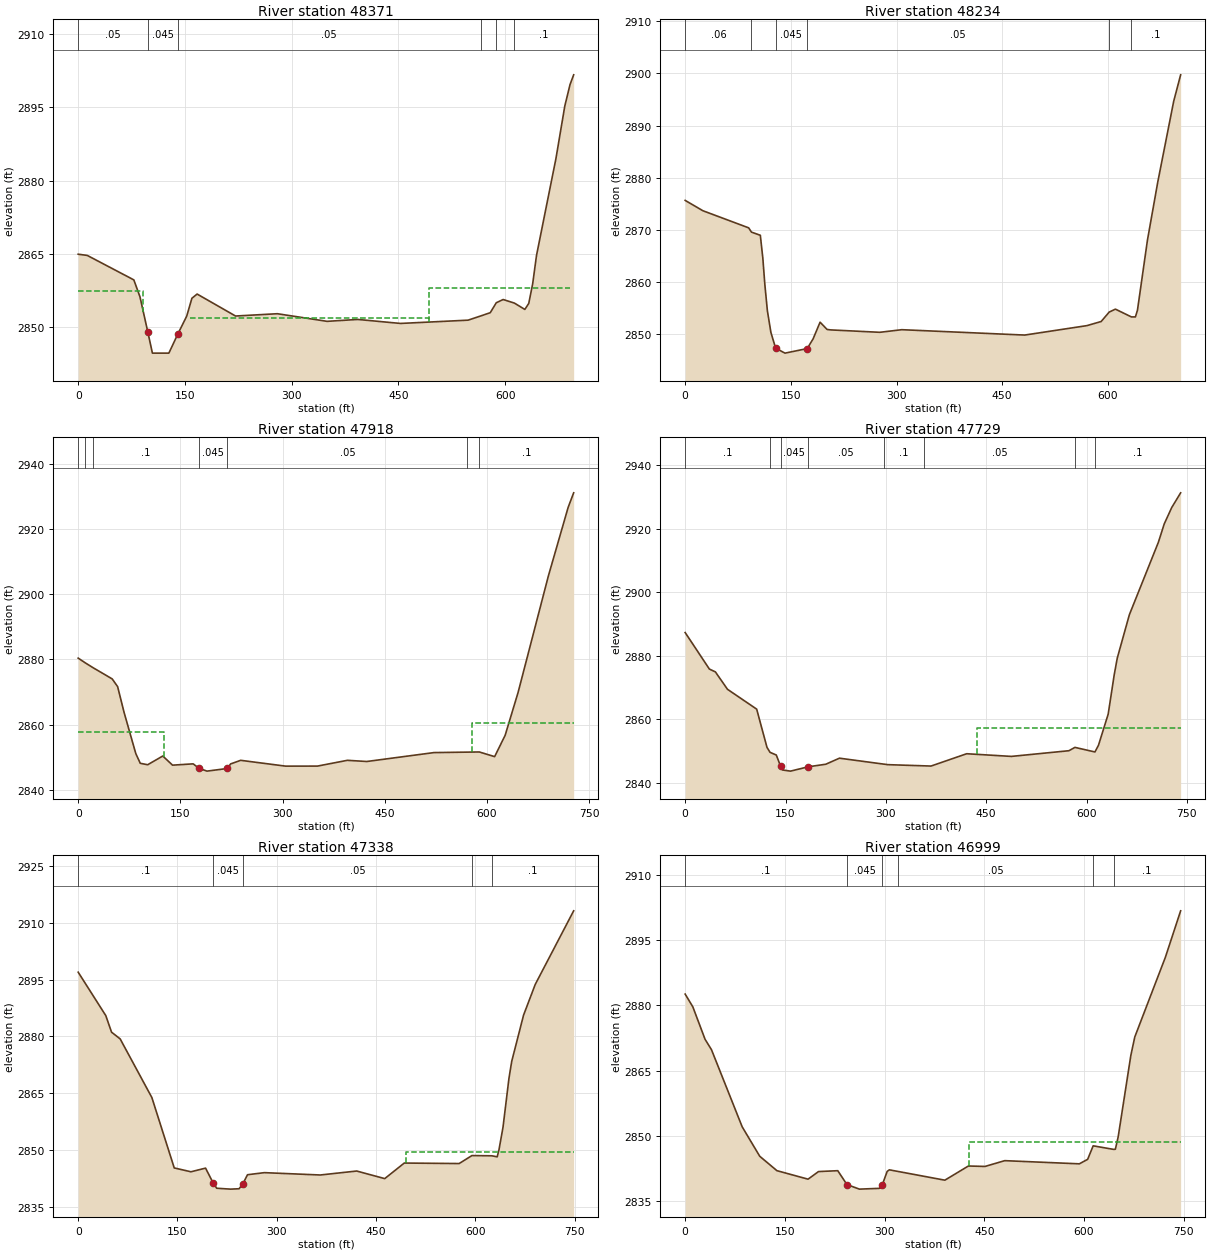
Type RM Length L Ch R = 1 ,48371   ,137.2,137.5,123.9
BEGIN DESCRIPTION:
xs 2
only partial survey data collected - invert assumed based on imagery and available survey data
END DESCRIPTION:
XS GIS Cut Line= 4
2219893.18764901500541.0769959332219971.56558433500587.299880866
2220066.02104484500649.6002909922220426.35951873500984.634056493
#Sta/Elev= 30
       0 2864.93    12.8 2864.68    78.2 2859.67    86.8 2856.21    97.9 2848.95
   104.3 2844.67   127.4 2844.67  140.34 2848.68   152.5 2852.25   159.8 2855.91
   167.1 2856.77   221.1 2852.27   279.9 2852.74   349.7 2851.18   392.8 2851.57
   452.9 2850.75   547.8 2851.42   565.3 2852.27     579 2852.95   587.5 2854.99
   597.1 2855.65   612.9 2854.92   627.6 2853.62   633.1 2854.85   638.6 2858.86
     644 2864.68   671.3 2884.52   683.7 2895.24   691.1 2899.68   696.2 2901.67
#Mann= 6 ,-1,0
       0     .05       0    97.9    .045       0  140.34     .05       0
   565.3     .06       0   587.5    .016       0   612.9      .1       0
#XS Ineff= 3 ,-1
       0    91.7 2857.32   157.3  493.35  2851.8  493.35  690.54 2858.03
Permanent Ineff=
       F       F       F
Bank Sta=97.9,140.34
XS Rating Curve= 0 ,0
Exp/Cntr(USF)=0,0
Exp/Cntr=0.5,0.3

Type RM Length L Ch R = 1 ,48234   ,311.1,315.6,292.1
BEGIN DESCRIPTION:
xs 1
END DESCRIPTION:
XS GIS Cut Line= 3
2219775.47614494500668.5634939212219878.54136566500687.001918779
2220358.53316553501044.610514704
#Sta/Elev= 30
       0 2875.68    25.1  2873.7    90.1 2870.42    94.1  2869.6   106.7 2868.99
   110.3 2864.54   113.1 2859.57   116.7 2854.54   121.7 2850.38   128.4 2847.36
   141.7 2846.41   173.2 2847.28   181.6 2849.14   191.5 2852.34   201.5 2850.94
   206.5 2850.86   276.3  2850.4   307.5  2850.9   481.9 2849.87   570.3 2851.68
   590.5 2852.47   601.9 2854.28   610.7 2854.84   633.4 2853.35   639.1 2853.35
     642 2854.63   656.2 2868.07   670.7  2879.1   693.4 2894.65   703.3 2899.74
#Mann= 6 ,-1,0
       0     .06       0    94.1     .05       0   128.4    .045       0
   173.2     .05       0   601.9    .016       0   633.4      .1       0
Bank Sta=128.4,173.2
XS Rating Curve= 0 ,0
Exp/Cntr(USF)=0,0
Exp/Cntr=0.3,0.1

Type RM Length L Ch R = 1 ,47918   ,184.7,188.7,176.1
XS GIS Cut Line= 2
2219631.33388687500889.1872679382220245.08554016501279.447099233
#Sta/Elev= 30
       0 2880.41    10.5 2878.95    22.3 2877.42    49.9 2874.05    57.9 2871.68
    67.4 2863.75    84.6 2851.15    91.1 2848.19     102 2847.75   124.2 2850.42
   138.5 2847.62   168.7 2848.02   177.4 2846.67     189 2845.79     219  2846.6
   223.7 2847.99   238.5  2849.1   304.4 2847.32   351.2 2847.33   395.1  2849.1
   423.7 2848.74   522.2 2851.47   571.4 2851.61   588.8 2851.66   611.3 2850.23
   626.7 2856.75   645.7 2869.88   690.2  2905.6   719.2  2926.6   727.3 2931.06
#Mann= 7 ,-1,0
       0      .1       0    10.5     .07       0    22.3      .1       0
   177.4    .045       0     219     .05       0   571.4    .016       0
   588.8      .1       0
#XS Ineff= 2 , 0
          126.65 2857.71   577.8          2860.6
Permanent Ineff=
       F       F
#Block Obstruct= 2 , 0
           55.25 2900.41
Bank Sta=177.4,219
XS Rating Curve= 0 ,0
Exp/Cntr(USF)=0,0
Exp/Cntr=0.3,0.1

Type RM Length L Ch R = 1 ,47729   ,396.5,390.9,357.5
XS GIS Cut Line= 4
2219524.12458172501051.8671391272219618.85464808501101.334327392
2219943.52513462 501290.003471972220171.89020978501410.461580847
#Sta/Elev= 30
       0 2887.35    36.2 2875.84    45.2 2874.95    63.2 2869.48   106.9 2863.21
   122.3 2851.17   126.9  2849.6   136.2 2848.76   142.8 2845.14   145.4 2844.05
   157.5 2843.68   183.8 2845.04   210.2 2845.85   230.6 2847.76   302.7 2845.72
   367.5 2845.28   420.8 2849.16   487.6 2848.32   573.6 2850.11   582.6 2851.16
   612.5 2849.72   617.8 2851.83   632.3 2861.64   641.4 2874.13   645.9 2879.32
     664 2892.99   707.3 2915.78   716.1  2921.6   727.3 2926.75   740.6 2931.38
#Mann= 8 ,-1,0
       0      .1       0  126.87     .05       0   142.8    .045       0
   183.8     .05       0  296.87      .1       0  356.87     .05       0
   582.6    .016       0   612.5      .1       0
#XS Ineff= 2 , 0
                          436.28         2857.21
Permanent Ineff=
       F       F
Bank Sta=142.8,183.8
XS Rating Curve= 0 ,0
Exp/Cntr(USF)=0,0
Exp/Cntr=0.3,0.1

Type RM Length L Ch R = 1 ,47338   ,345.2,339,337.9
XS GIS Cut Line= 4
2219325.87482199501413.3096702112219453.22111503501467.770157357
2219810.58113497501590.2935927632220020.68381269501689.181526404
#Sta/Elev= 30
       0 2897.01    41.7 2885.52    50.4 2881.14    63.4 2879.36   111.3 2863.84
   145.1 2845.21   170.3 2844.19   192.4 2845.16  204.082841.162   209.3 2839.83
   230.1  2839.6   243.1  2839.7     249 2841.07   255.8 2843.41   281.2 2843.96
   365.7 2843.34   420.7 2844.39   463.1 2842.38   492.6  2846.5   575.5 2846.37
   594.8 2848.48   624.9 2848.42     633 2848.15   635.8 2850.12   641.8 2856.02
   650.7 2868.85   654.9  2873.4   672.8 2885.64   690.5 2893.79   748.5 2913.25
#Mann= 5 ,-1,0
       0      .1       0  204.08    .045       0     249     .05       0
   594.8    .016       0   624.9      .1       0
#XS Ineff= 2 , 0
                          495.46         2849.42
Permanent Ineff=
       F       F
Bank Sta=204.08,249
XS Rating Curve= 0 ,0
Exp/Cntr=0.3,0.1

Type RM Length L Ch R = 1 ,46999   ,442.5,379.7,345.8
XS GIS Cut Line= 3
2219183.46962433501706.6714251382219280.92288676501773.076424111
2219882.29722233501952.298250446
#Sta/Elev= 30
       0 2882.61    11.6 2879.66    29.9 2872.22    39.6 2869.82    85.8 2852.07
   112.2  2845.3     138 2841.99   184.9 2840.03   200.6 2841.78   229.6 2841.98
  243.37 2838.79   262.1 2837.74   292.4 2837.92   296.6 2838.76   303.9 2841.81
   307.1 2842.18   390.7  2839.8   426.1 2843.06   451.1 2842.96   480.8 2844.29
     593 2843.56   605.5 2844.59   613.8  2847.7   644.8 2846.88   647.2 2846.92
   651.4 2849.73   670.5 2868.52   676.4 2872.74   722.4 2891.07   745.4 2901.77
#Mann= 6 ,-1,0
       0      .1       0  243.37    .045       0   296.6      .1       0
   320.8     .05       0   613.8    .016       0   644.8      .1       0
#XS Ineff= 2 , 0
                          427.72         2848.59
Permanent Ineff=
       F       F
Bank Sta=243.37,296.6
XS Rating Curve= 0 ,0
Exp/Cntr(USF)=0,0
Exp/Cntr=0.3,0.1

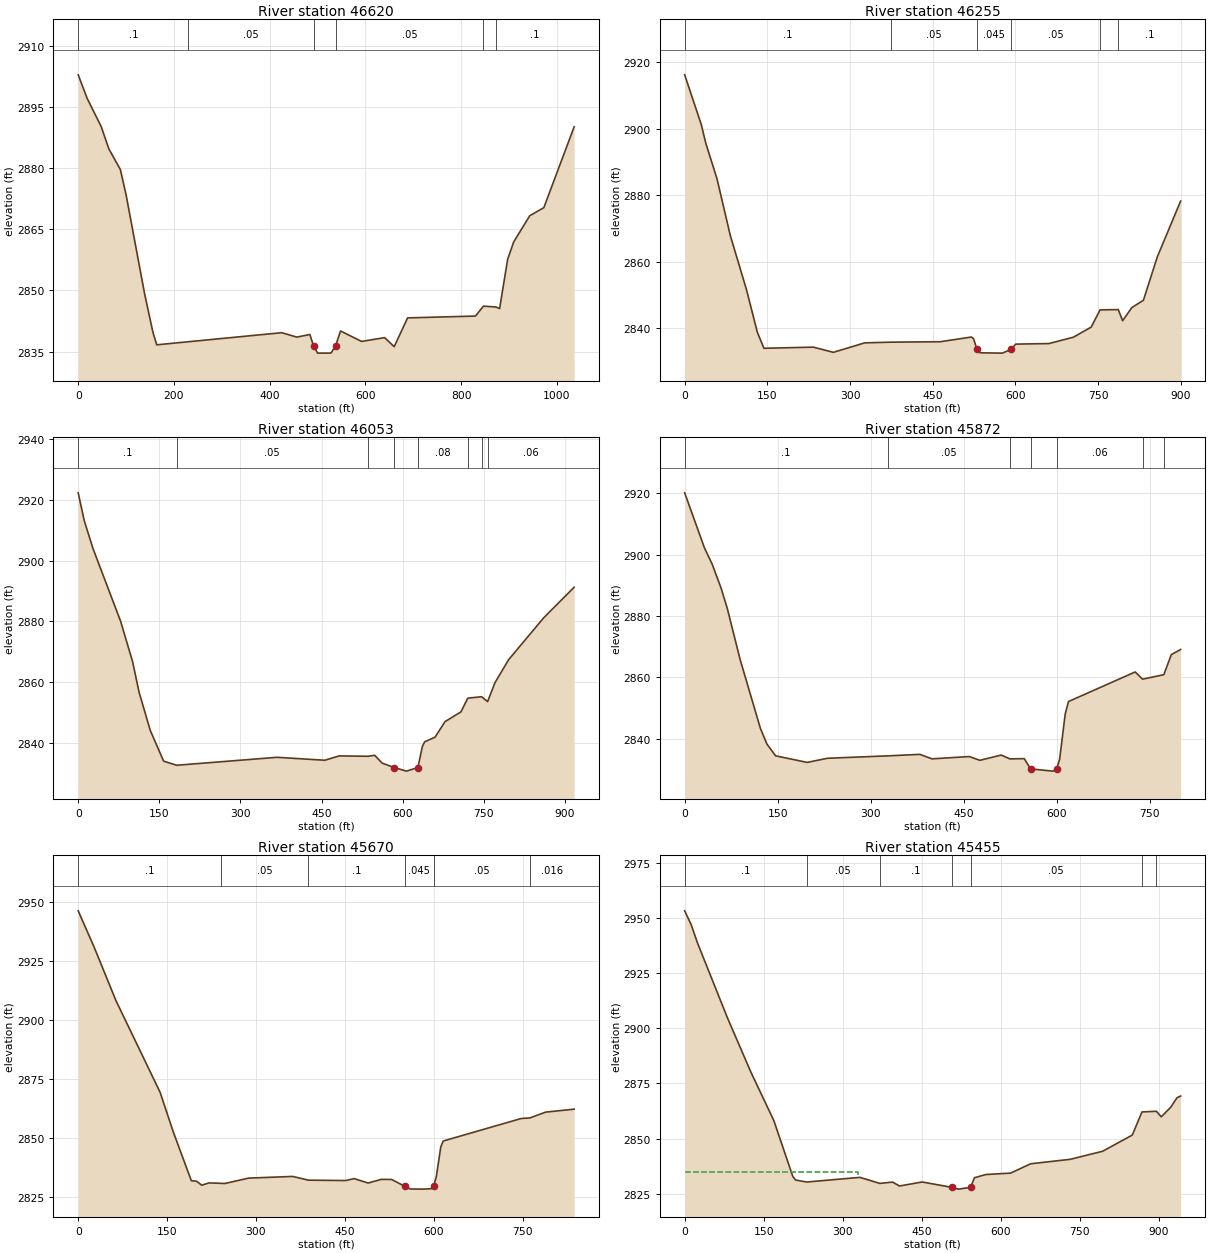
Type RM Length L Ch R = 1 ,46620   ,372.3,364.3,358.2
XS GIS Cut Line= 3
2218816.17766463502187.9715106312219527.03849867502178.365283144
2219836.35902376502278.270049009
#Sta/Elev= 30
       0 2902.87    18.5 2897.15      48 2890.18      64 2884.71      88 2879.66
     100 2873.45   139.1 2848.94     156 2839.77     164 2836.66   425.1 2839.63
   456.7 2838.55   483.8 2839.19   491.9 2836.33   500.1 2834.62     528 2834.63
  537.612836.392     548 2840.05   592.1 2837.49   640.1 2838.42   660.1 2836.21
   688.1 2843.26   829.8 2843.71   846.6 2846.14   872.9 2845.93   880.3 2845.54
   897.1 2857.63   909.7 2861.89   943.3 2868.32   972.7  2870.3    1036 2890.12
#Mann= 6 ,-1,0
       0      .1       0     230     .05       0   491.9    .045       0
  537.61     .05       0   846.6    .016       0   872.9      .1       0
Bank Sta=491.9,537.61
XS Rating Curve= 0 ,0
Exp/Cntr(USF)=0,0
Exp/Cntr=0.3,0.1

Type RM Length L Ch R = 1 ,46255   ,91.7,202.1,215.2
XS GIS Cut Line= 4
2218814.48727887502504.9112841012219162.05393126502565.750749948
2219582.64801074502518.5084744962219700.54822284502555.532398375
#Sta/Elev= 30
       0 2916.28    30.1 2901.34    38.3  2895.7    58.6 2885.02    82.9 2867.84
   112.3 2851.54   131.7 2838.87   143.8    2834   233.5 2834.34   269.7 2832.78
   326.6 2835.63   375.1 2835.84   463.7 2835.97     520 2837.38     524 2836.92
  530.15 2833.67   536.1 2832.63   576.4 2832.54   592.5 2833.71   600.5 2835.25
   660.9 2835.42   705.2 2837.33   737.4 2840.36   753.6 2845.56   786.6 2845.63
   794.5  2842.3   811.2 2846.24   832.2 2848.44   857.3 2861.45   899.7 2878.28
#Mann= 6 ,-1,0
       0      .1       0   375.1     .05       0  530.15    .045       0
   592.5     .05       0   753.6    .016       0   786.6      .1       0
Bank Sta=530.15,592.5
XS Rating Curve= 0 ,0
Exp/Cntr(USF)=0,0
Exp/Cntr=0.3,0.1

Type RM Length L Ch R = 1 ,46053   ,70.3,180.9,188
XS GIS Cut Line= 3
2218789.21763177  502576.85018432218934.07283261502603.751864455
2219667.66095683502836.554865796
#Sta/Elev= 30
       0  2922.3    11.1 2913.18    27.4 2903.92    78.3 2880.08   100.6  2866.7
   112.6 2856.64   133.2 2844.13   157.9 2833.99     182 2832.63   367.8 2835.25
     456 2834.28   482.6 2835.71   535.7 2835.59   548.2 2835.91     562 2833.34
   584.8 2831.85     607  2830.7   628.1 2831.89   636.3 2838.76   640.5 2840.34
   659.8 2841.88   678.3    2847   707.7  2850.2   720.3 2854.71   745.9 2855.19
     757 2853.58   770.6 2859.82   795.8 2867.37   860.5 2881.13     917 2891.23
#Mann= 8 ,-1,0
       0      .1       0     182     .05       0   535.7      .1       0
   584.8    .045       0   628.1     .08       0   720.3    .016       0
   745.9     .08       0     757     .06       0
Bank Sta=584.8,628.1
XS Rating Curve= 0 ,0
Exp/Cntr(USF)=0,0
Exp/Cntr=0.3,0.1

Type RM Length L Ch R = 1 ,45872   ,154,202.4,212.7
XS GIS Cut Line= 3
2218788.94635357502610.4000266332218940.06957572 502643.57801454
2219457.43568201503028.890945224
#Sta/Elev= 30
       0 2920.11    31.9 2902.17    44.3  2896.9    58.8 2889.03    68.8 2882.41
    89.3 2865.91   122.1 2843.41   132.6  2838.3   146.6 2834.46   197.6 2832.31
   230.3 2833.66   327.5 2834.44   379.3 2834.93   398.9 2833.47   458.9 2834.22
   476.1 2832.99   510.4  2834.7   524.7 2833.45   547.6 2833.54   557.8 2830.21
   593.7 2829.47   599.72830.024   604.7 2833.34   613.7 2848.12     619 2852.14
   726.6 2861.77   738.4 2859.42   772.7 2860.88   784.8 2867.41   799.8 2869.09
#Mann= 7 ,-1,0
       0      .1       0   327.5     .05       0   524.7      .1       0
   557.8    .045       0   599.7     .06       0   738.4    .016       0
   772.7     .06       0
Bank Sta=557.8,599.7
XS Rating Curve= 0 ,0
Exp/Cntr=0.3,0.1

Type RM Length L Ch R = 1 ,45670   ,198.1,215.3,219.5
XS GIS Cut Line= 4
2218694.09589494502723.4684552732219038.08792165502878.066332519
2219173.52932715503094.7993854062219360.40569787503177.368678004
#Sta/Elev= 30
       0 2946.11    27.1 2930.62    63.7 2908.13   138.2 2869.37   160.2 2852.78
   190.9 2831.97   199.6 2831.77   208.6 2830.07   220.7 2831.04   247.7  2830.8
   287.3 2833.06   361.9 2833.78   388.6  2832.2   451.6 2832.04   465.7 2832.86
   489.3 2830.99   511.5 2832.54     529  2832.5   550.92829.648     560 2828.47
   583.6 2828.41   595.7 2828.59   599.72829.609   604.4 2833.68   611.9 2846.24
     616 2848.76   747.5 2858.27   762.4 2858.53   788.7 2860.97     837 2862.23
#Mann= 6 ,-1,0
       0      .1       0   240.4     .05       0   388.6      .1       0
   550.9    .045       0   599.7     .05       0   762.4    .016       0
Bank Sta=550.9,599.7
XS Rating Curve= 0 ,0
Exp/Cntr(USF)=0,0
Exp/Cntr=0.3,0.1

Type RM Length L Ch R = 1 ,45455   ,269.4,303.9,222.5
XS GIS Cut Line= 4
2218629.56459537502789.1167864192218914.15957665503037.269727407
2219018.27969175503294.0993446532219268.16796798503434.661500038
#Sta/Elev= 30
       0 2953.39    12.3 2947.14    24.4 2938.75    81.3 2904.73   125.5 2880.24
   169.2 2858.17   205.1 2832.86   210.4 2831.14   231.7 2830.24   332.5 2832.35
   370.4 2829.62   394.8  2830.2   407.7 2828.43   450.9 2830.25     507 2827.83
   519.9 2827.01   542.7 2827.81   550.1 2832.19   571.7 2833.64   618.6 2834.28
   656.9 2838.53   731.8 2840.54   793.5 2844.22   849.7 2851.57     868 2862.05
   895.5 2862.37   904.7 2859.85   922.7 2864.22   934.5  2868.5   941.4 2869.27
#Mann= 7 ,-1,0
       0      .1       0   231.7     .05       0   370.4      .1       0
     507    .045       0   542.7     .05       0     868    .016       0
   895.5      .1       0
#XS Ineff= 2 , 0
          328.42 2834.59
Permanent Ineff=
       F       F
Bank Sta=507,542.7
XS Rating Curve= 0 ,0
Exp/Cntr(USF)=0,0
Exp/Cntr=0.3,0.1

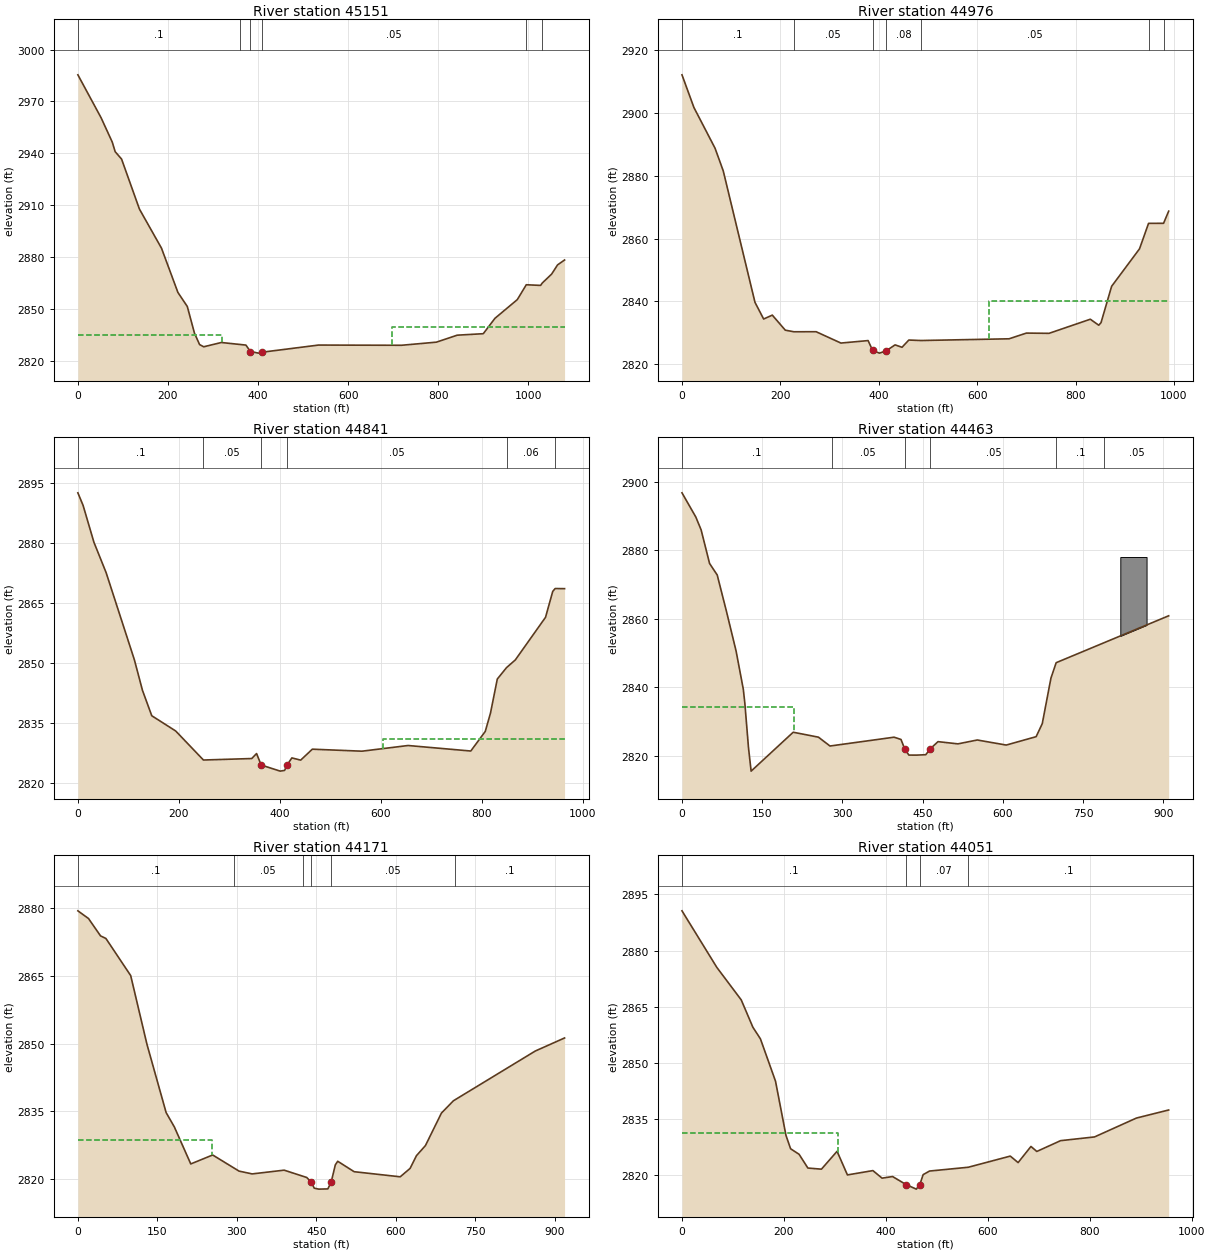
Type RM Length L Ch R = 1 ,45151   ,179.5,174.4,116.6
XS GIS Cut Line= 3
2218422.32233767502858.4861892252218823.86264662503340.718809074
2219204.26925511503586.638232742
#Sta/Elev= 30
       0 2985.37    51.5 2960.57    76.4 2946.44    82.8 2940.92      97 2936.67
   136.7 2907.73   185.7 2885.11   222.1 2859.53   242.9 2851.45   258.8 2836.04
   270.2  2829.4   279.4 2828.13   318.5  2830.6   373.1 2829.11  382.96  2825.4
   400.9 2824.46   409.4    2825   534.3 2829.12   718.4    2829   795.9  2830.8
   842.2 2834.84     900 2835.69     926  2844.6   975.6 2855.41   995.5 2863.99
  1027.3 2863.62  1031.2 2865.05  1051.8 2870.16  1064.9 2875.46  1080.5 2878.32
#Mann= 6 ,-1,0
       0      .1       0     360     .05       0  382.96    .045       0
   409.4     .05       0   995.5    .016       0  1031.2     .05       0
#XS Ineff= 2 , 0
          319.66 2834.68   697.8         2839.57
Permanent Ineff=
       F       F
Bank Sta=382.96,409.4
XS Rating Curve= 0 ,0
Exp/Cntr(USF)=0,0
Exp/Cntr=0.3,0.1

Type RM Length L Ch R = 1 ,44976   ,130.6,135.4,138.4
XS GIS Cut Line= 2
2218279.02687454 503124.036489992219139.75315936503611.665695708
#Sta/Elev= 30
       0 2912.24    24.3 2901.81    67.2 2888.84    83.9  2881.6   148.4 2839.68
     166 2834.37   183.6 2835.61     210 2830.81   227.7  2830.3   272.6 2830.32
   323.1  2826.7   378.3 2827.49   387.5 2824.36   401.3 2823.49   415.1 2824.21
   433.1 2826.12   447.3 2825.36   461.1 2827.66   485.9 2827.51   664.9 2828.06
   700.1 2829.88   746.1  2829.8     830  2834.3   847.2 2832.39   851.8 2833.21
   873.3 2844.79     930 2856.74   948.4 2864.87   978.9 2864.89   989.3 2868.76
#Mann= 7 ,-1,0
       0      .1       0   227.7     .05       0   387.5    .045       0
   415.1     .08       0   485.9     .05       0   948.4    .016       0
   978.9      .1       0
#XS Ineff= 2 , 0
                          623.35         2840.16
Permanent Ineff=
       F       F
Bank Sta=387.5,415.1
XS Rating Curve= 0 ,0
Exp/Cntr(USF)=0,0
Exp/Cntr=0.3,0.1

Type RM Length L Ch R = 1 ,44841   ,370.1,377.6,380.2
XS GIS Cut Line= 4
2218259.07045812503201.4877255282218356.99999075503311.900126613
2218569.37456067503443.7303245282219043.75605938503752.511919189
#Sta/Elev= 30
       0 2892.58    10.3 2889.45    31.8  2880.2    55.9 2872.62   111.9 2850.79
   127.9 2843.15   146.3  2836.8   193.7 2832.98   248.6 2825.72   344.3 2826.09
   353.8 2827.34   362.9 2824.47   400.6 2822.94   409.3 2823.12  414.32 2824.51
   423.7 2826.25   441.1 2825.69   464.2 2828.43   562.5 2827.93   653.8 2829.35
   777.9 2827.97   806.6 2832.88   816.9 2837.45   830.4 2845.98   848.7 2848.84
   866.1 2850.77   925.9 2861.43   940.2 2867.92     945 2868.63   963.6  2868.6
#Mann= 6 ,-1,0
       0      .1       0   248.6     .05       0   362.9    .045       0
  414.32     .05       0   848.7     .06       0     945    .016       0
#XS Ineff= 2 , 0
                          603.36         2830.89
Permanent Ineff=
       F       F
Bank Sta=362.9,414.32
XS Rating Curve= 0 ,0
Exp/Cntr(USF)=0,0
Exp/Cntr=0.3,0.1

Type RM Length L Ch R = 1 ,44463   ,264.7,292.8,311.8
XS GIS Cut Line= 2
2217991.03306539503494.3127071192218731.22206539504023.931707119
#Sta/Elev= 30
       0 2896.83    25.8 2889.78    35.8    2886    51.6 2876.18    65.9 2872.81
    83.2 2862.16   101.2 2850.58   114.7  2839.4   117.6 2835.27   124.4  2822.3
   129.3 2815.47     208 2826.84   255.2  2825.4   276.8 2822.81   396.7 2825.39
   409.6 2824.73  416.36 2822.02   424.3 2820.16   438.7 2820.15   455.9 2820.27
   464.5 2822.01   478.8 2824.09   516.1 2823.44   552.3 2824.57   606.4 2823.09
   662.3 2825.54   673.8 2829.35     690 2842.65   699.8 2847.17   910.2 2860.88
#Mann= 6 ,-1,0
       0      .1       0     280     .05       0  416.36    .045       0
   464.5     .05       0     700      .1       0     790     .05       0
#XS Ineff= 2 , 0
          209.58 2834.17
Permanent Ineff=
       F       F
#Block Obstruct= 1 ,-1
  819.73  868.86 2878.06
Bank Sta=416.36,464.5
XS Rating Curve= 0 ,0
Exp/Cntr=0.3,0.1

Type RM Length L Ch R = 1 ,44171   ,93.5,119.8,142
XS GIS Cut Line= 4
2217839.20543767503661.8781886172218036.15199269503822.951428922
2218291.67764384504126.5082175122218539.54038722504227.065182189
#Sta/Elev= 30
       0  2879.4    20.1 2877.69    42.8 2873.85    52.9 2873.28    99.7 2865.06
   130.4 2849.84   166.6 2834.71   182.1 2831.54   213.1 2823.34   254.5 2825.32
   304.2 2821.75     329 2821.13   389.4 2821.96     432 2820.34   440.8 2819.27
   446.2 2817.97   454.7 2817.76   471.8 2817.81   478.1 2819.29     486 2823.15
   490.5 2823.93   521.5 2821.62   608.5 2820.49   627.1 2822.35     639 2825.15
   656.1 2827.41   686.3 2834.61   708.9 2837.33   863.3 2848.34   918.7 2851.24
#Mann= 6 ,-1,0
       0      .1       0  294.43     .05       0  424.43      .1       0
   440.8    .045       0   478.1     .05       0  711.21      .1       0
#XS Ineff= 2 , 0
          252.39 2828.73
Permanent Ineff=
       F       F
Bank Sta=440.8,478.1
XS Rating Curve= 0 ,0
Exp/Cntr(USF)=0,0
Exp/Cntr=0.3,0.1

Type RM Length L Ch R = 1 ,44051   ,274.8,250.8,200.9
XS GIS Cut Line= 4
2217755.34125859503737.1882789112218004.07264466503916.506254917
2218146.32403802504197.8908903972218387.55448491504427.342623177
#Sta/Elev= 30
       0 2890.62    68.4 2875.51   116.3 2866.83   139.1 2859.54   153.9 2856.44
   183.5 2845.14     204 2830.68   213.1 2827.09   229.8 2825.61     247 2821.94
   273.6 2821.64   304.3 2826.41   324.6  2820.1   374.6 2821.26   392.5 2819.24
   413.2 2819.67   439.8 2817.52   459.8 2816.31  466.61 2817.53   473.2 2820.18
   485.8 2821.14   561.7 2822.15   644.1 2825.13   659.5  2823.4   684.7  2827.7
   696.2 2826.37   742.8 2829.25   809.5 2830.25   891.5 2835.28   954.9 2837.44
#Mann= 4 ,-1,0
       0      .1       0   439.8    .045       0  466.61     .07       0
   561.7      .1       0
#XS Ineff= 2 , 0
          305.92 2831.26
Permanent Ineff=
       F       F
Bank Sta=439.8,466.61
XS Rating Curve= 0 ,0
Exp/Cntr(USF)=0,0
Exp/Cntr=0.3,0.1