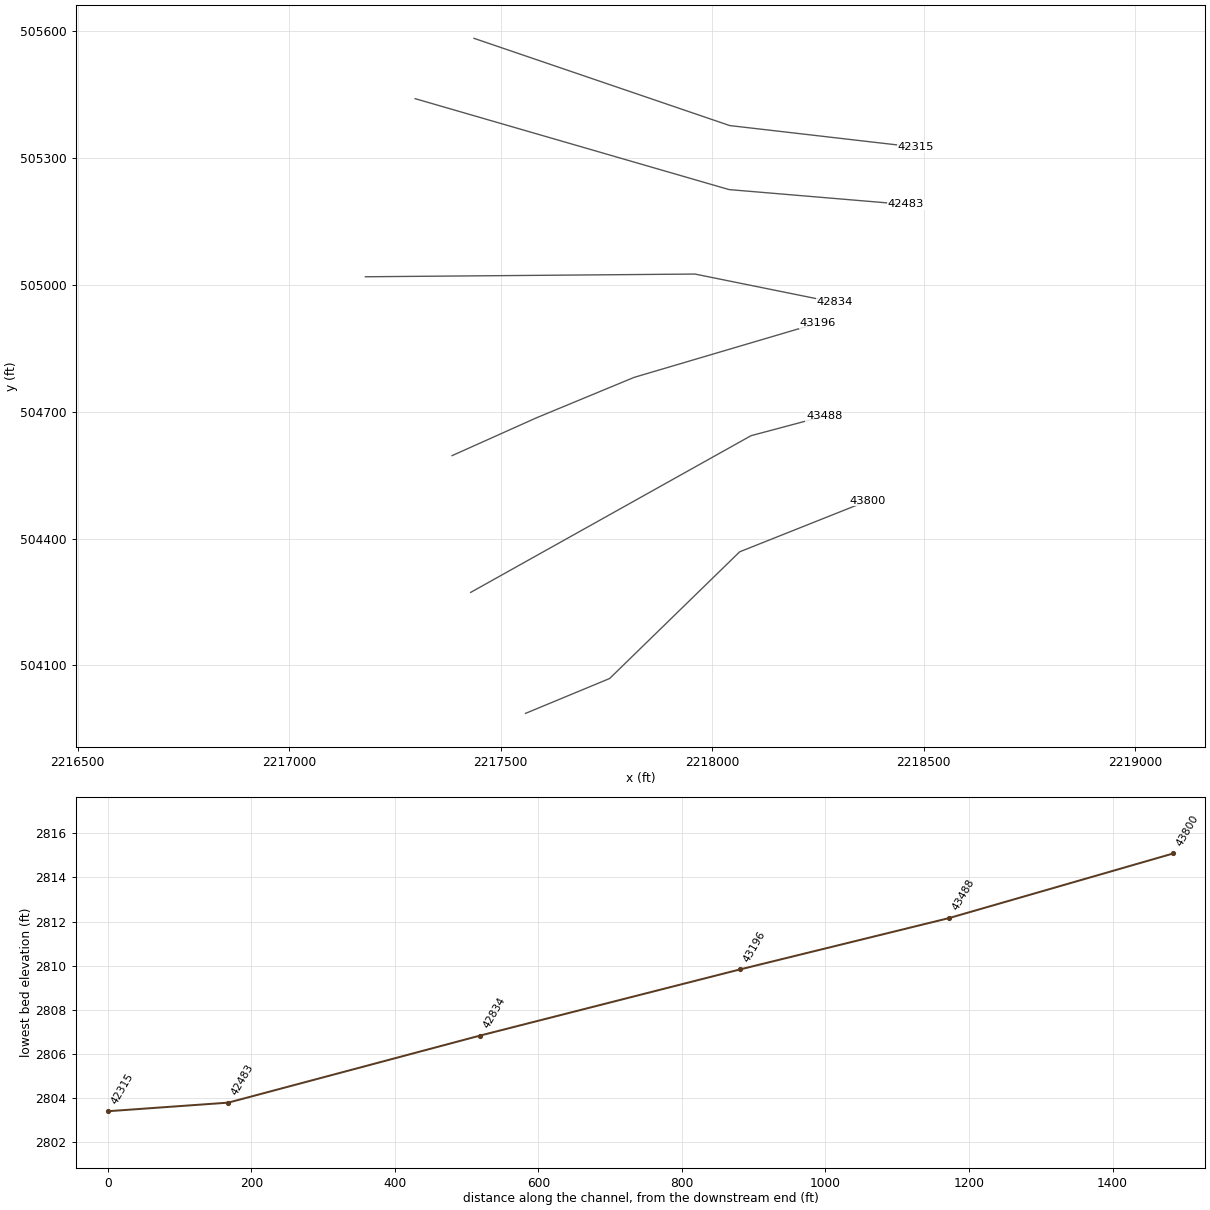
HEC-RAS study OLDFLDFK1.prj: OLDFLDFK1

--- OLDFLDFK1.g01 (geometry) --- (continued)

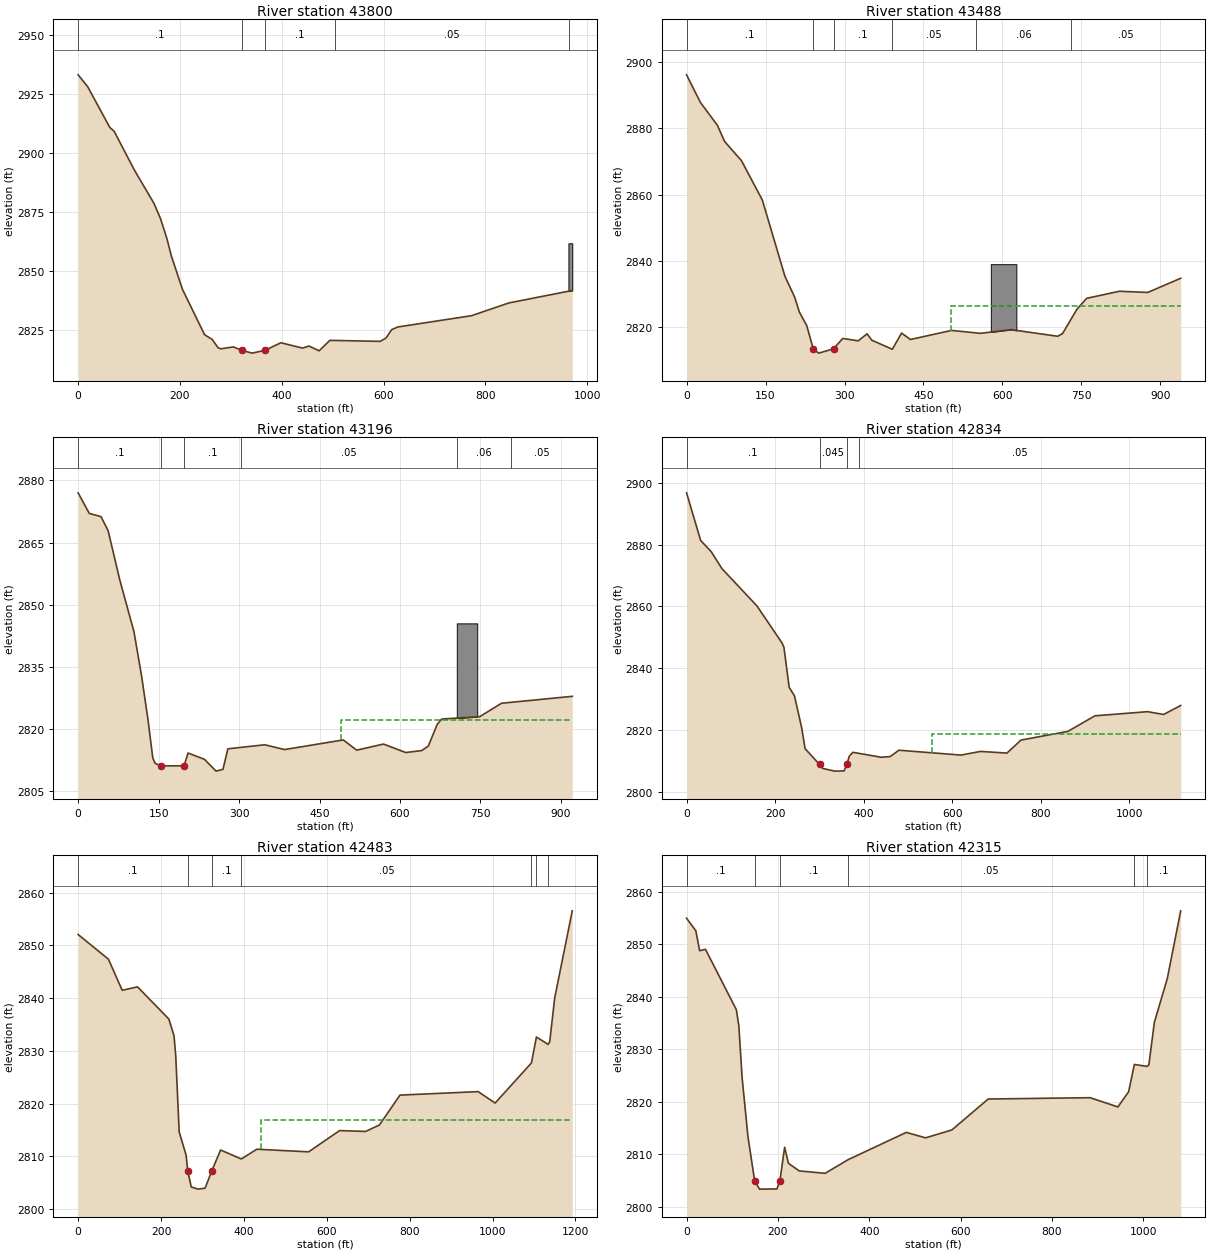
Type RM Length L Ch R = 1 ,43800   ,323.2,312.4,265.6
XS GIS Cut Line= 4
2217558.76993461503986.4039326732217757.57139556 504068.87085259
2218064.97067515504368.5851501852218368.01445969504489.348299529
#Sta/Elev= 30
       0 2932.96    18.8 2927.94    62.1 2910.72    70.8 2909.06   110.3  2892.7
   148.8 2878.59   161.7 2872.17   174.3 2863.68   183.4 2856.08   205.2 2842.01
   248.4 2822.91   263.6 2820.85   274.7 2817.42   280.3 2816.91     305 2817.72
   321.9 2816.25   341.8 2815.09  367.462816.298   398.3 2819.49   440.8 2817.22
   453.5 2818.09   473.5 2816.07   494.5  2820.5   593.5 2820.07   604.8 2821.47
   616.1 2825.05   628.2 2826.17   772.9 2830.95   846.1 2836.34   970.8 2841.62
#Mann= 5 ,-1,0
       0      .1       0   321.9    .045       0  367.46      .1       0
  505.23     .05       0  964.56     .06       0
#Block Obstruct= 1 ,-1
  963.21  970.78 2861.62
Bank Sta=321.9,367.46
XS Rating Curve= 0 ,0
Exp/Cntr=0.3,0.1

Type RM Length L Ch R = 1 ,43488   ,293.5,291.5,281.1
XS GIS Cut Line= 3
2217429.03841551504272.5228753152218091.86811211504643.323256314
2218264.78020688504689.433148252
#Sta/Elev= 30
       0 2896.14    26.5 2887.77    58.5 2880.94    72.3 2876.04   104.4 2870.21
   143.9 2858.37   186.9 2835.34   205.3 2829.07   214.4 2824.49   228.2 2820.51
   240.9 2813.28   251.1 2812.16   279.1 2813.47   296.7  2816.6   326.1 2815.86
   342.8 2817.99   351.9 2816.05   390.8 2813.33   408.4 2818.21   425.3 2816.27
   503.2 2819.01   558.3 2818.13   615.8 2819.25   704.8 2817.25   714.1 2818.07
   741.5 2825.42   759.8 2828.69   821.9 2830.83   875.9 2830.47   938.5 2834.75
#Mann= 6 ,-1,0
       0      .1       0   240.9    .045       0   279.1      .1       0
     390     .05       0     550     .06       0     730     .05       0
#XS Ineff= 2 , 0
                          502.54         2826.38
Permanent Ineff=
       F       F
#Block Obstruct= 1 ,-1
  577.85  626.38    2839
Bank Sta=240.9,279.1
XS Rating Curve= 0 ,0
Exp/Cntr(USF)=0,0
Exp/Cntr=0.3,0.1

Type RM Length L Ch R = 1 ,43196   ,376.1,362.2,319.4
XS GIS Cut Line= 4
2217385.19522091504596.125521581 2217584.6593008504685.590657257
2217815.43199821504781.2270360392218249.55130906504909.493886154
#Sta/Elev= 30
       0 2876.99    20.8 2872.02    42.7 2871.24    55.9 2867.86    77.8 2855.89
   104.1 2843.48   118.1 2832.93   130.2 2822.29   139.2    2813   143.6 2811.69
   154.9 2811.11  197.47 2811.11   204.9  2814.2   235.4 2812.68   257.1 2809.83
     270 2810.26   279.1 2815.21     348 2816.19   384.7 2815.03   494.2 2817.36
   519.2 2814.89   569.3 2816.36   610.6 2814.32   640.2 2814.78   652.7 2815.86
   669.4 2821.13   677.7  2822.4   748.6 2822.98   789.3 2826.21   921.1 2827.88
#Mann= 6 ,-1,0
       0      .1       0   154.9    .045       0  197.47      .1       0
  304.25     .05       0  706.02     .06       0  806.02     .05       0
#XS Ineff= 2 , 0
                          489.58         2822.21
Permanent Ineff=
       F       F
#Block Obstruct= 1 ,-1
   705.8  743.95 2845.49
Bank Sta=154.9,197.47
XS Rating Curve= 0 ,0
Exp/Cntr(USF)=0,0
Exp/Cntr=0.3,0.1

Type RM Length L Ch R = 1 ,42834   ,360.8,350.8,324.9
XS GIS Cut Line= 3
2217180.23843032       505019.262217959.30217279505025.651110297
2218290.04996205504958.639898586
#Sta/Elev= 30
       0  2896.7    31.9 2881.31    55.9 2877.67    79.9 2872.24   159.3 2860.14
   216.1 2848.14   220.1 2846.78   231.9 2833.89   243.9 2831.12   260.2 2820.79
   267.9 2814.07   300.5 2808.99   307.9 2807.69   335.1 2806.83   355.9 2806.89
  362.372809.067   367.9 2811.69   375.9  2812.9     440 2811.31     460 2811.53
     480 2813.58     620 2812.01     664 2813.19     724 2812.66   755.7 2816.86
   861.5 2819.65   922.8 2824.69  1041.5 2826.03  1077.9 2825.12  1116.6 2828.03
#Mann= 4 ,-1,0
       0      .1       0   300.5    .045       0  362.37      .1       0
     390     .05       0
#XS Ineff= 2 , 0
                          554.37         2818.72
Permanent Ineff=
       F       F
Bank Sta=300.5,362.37
XS Rating Curve= 0 ,0
Exp/Cntr=0.3,0.1

Type RM Length L Ch R = 1 ,42483   ,170.6,167.9,166.2
XS GIS Cut Line= 3
2217297.93543032505440.5379772752218039.99448368505225.460642027
2218458.45350042505190.233941254
#Sta/Elev= 30
       0 2852.08    73.1  2847.4   106.4  2841.5   143.4 2842.15   218.9 2836.05
   231.4 2832.89   235.6 2829.04   243.9 2814.64   260.5 2810.27   264.7 2807.19
     273  2804.2   289.7 2803.79   306.3 2803.97     323 2807.32   343.8 2811.21
   393.8 2809.51   431.3 2811.36   556.2 2810.86   630.9 2814.89   693.7 2814.73
     727 2815.95   776.8 2821.62   965.5 2822.28  1006.3 2820.11  1093.9 2827.72
    1106 2832.64  1134.1 2831.24  1138.1 2831.74  1150.1 2840.07  1192.5 2856.57
#Mann= 7 ,-1,0
       0      .1       0   264.7    .045       0     323      .1       0
   393.8     .05       0  1093.9     .06       0    1106    .016       0
  1134.1      .1       0
#XS Ineff= 2 , 0
                          442.14         2816.88
Permanent Ineff=
       F       F
Bank Sta=264.7,323
XS Rating Curve= 0 ,0
Exp/Cntr=0.3,0.1

Type RM Length L Ch R = 1 ,42315   ,193,190.6,182.3
XS GIS Cut Line= 3
2217436.99786297505583.2764826362218041.51925124505376.910414509
2218481.37467748505326.047738282
#Sta/Elev= 30
       0 2854.93    20.3 2852.54    28.7 2848.74    41.4 2849.01     109 2837.53
   114.4  2834.5   121.7 2824.52   134.4 2813.38   149.1 2804.96   159.7  2803.4
   197.8 2803.44  204.37 2805.01   214.7 2811.36   223.1  2808.3   246.8 2806.86
   303.5 2806.41   353.2 2808.98     481 2814.19   523.2 2813.15   580.8 2814.66
   660.3 2820.54   883.4 2820.79   944.1 2819.03   967.6 2821.92   980.2 2827.12
  1007.9 2826.74  1011.9 2827.04    1024 2835.14  1052.2 2843.43  1081.6 2856.33
#Mann= 6 ,-1,0
       0      .1       0   149.1    .045       0  204.37      .1       0
   353.2     .05       0   980.2    .016       0  1007.9      .1       0
Bank Sta=149.1,204.37
XS Rating Curve= 0 ,0
Exp/Cntr(USF)=0,0
Exp/Cntr=0.3,0.1