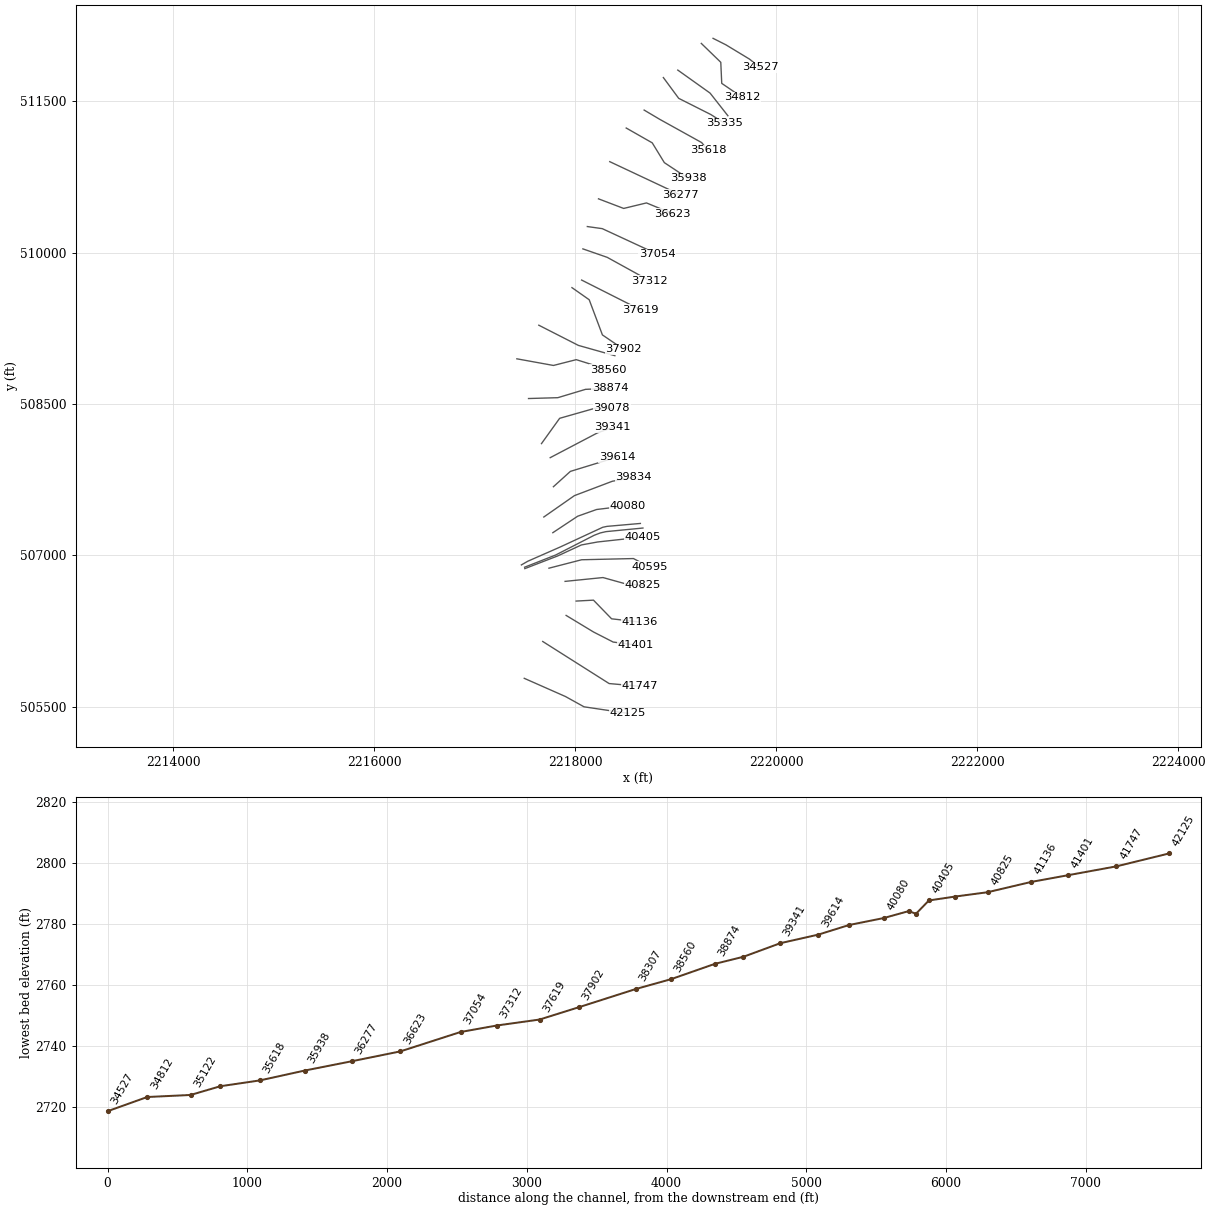
HEC-RAS study OLDFLDFK1.prj: OLDFLDFK1

--- OLDFLDFK1.g01 (geometry) --- (continued)

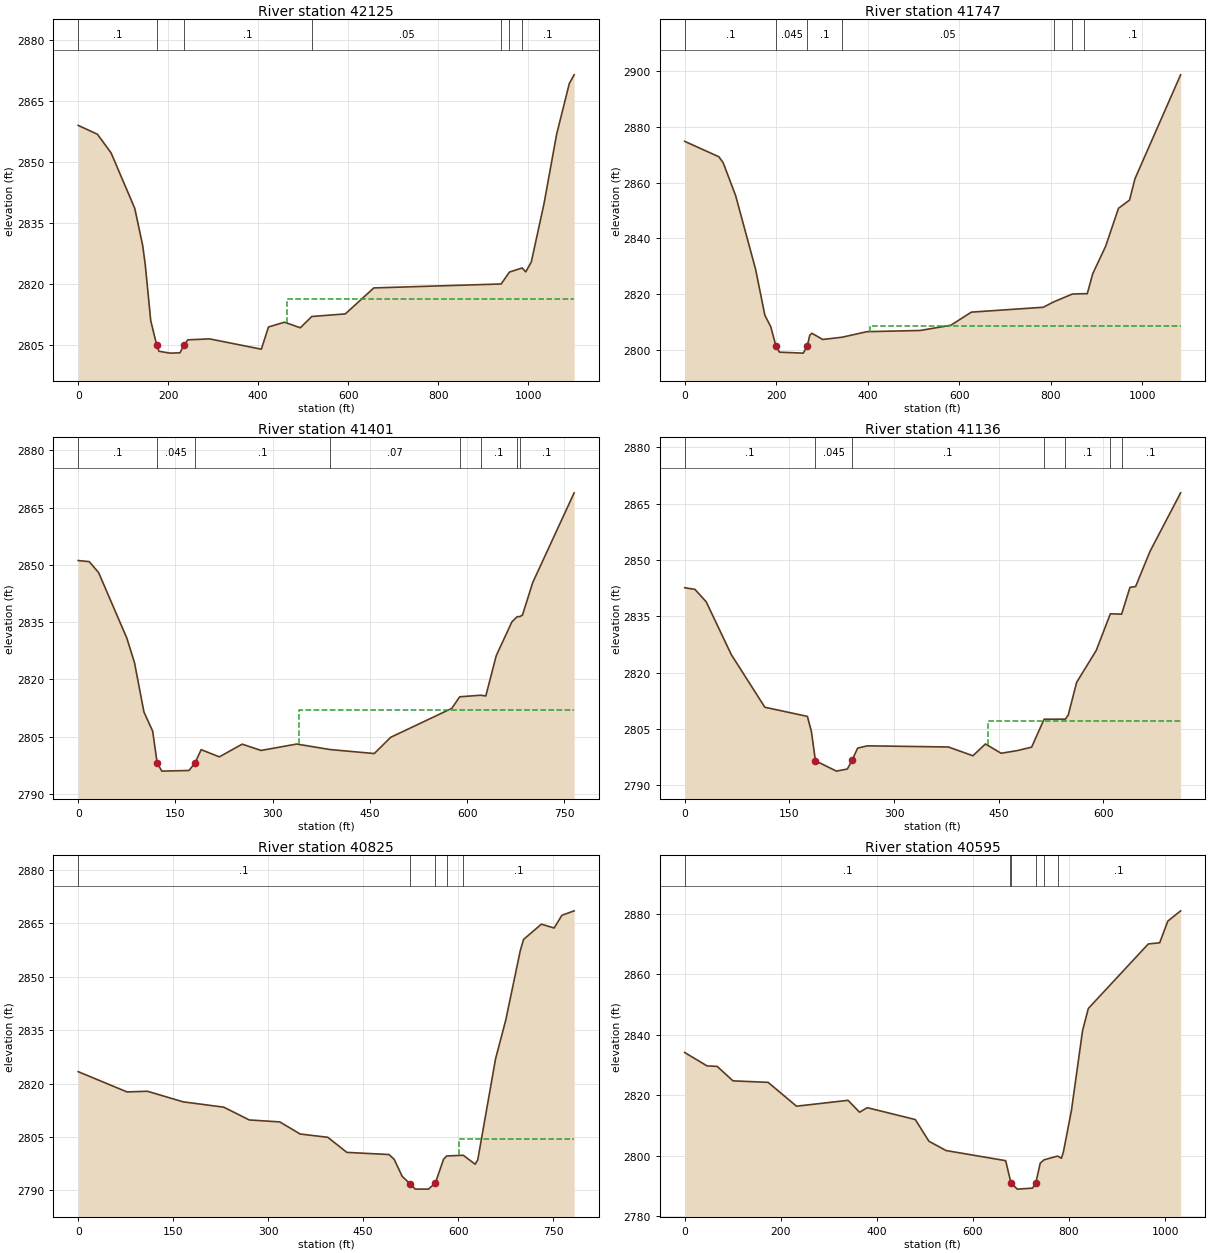
Type RM Length L Ch R = 1 ,42125   ,382.3,377.6,361.1
XS GIS Cut Line= 4
2217493.07842698505782.5687139852217903.58605337505602.024759519
2218088.02562112505500.1987481562218526.54102986505435.201130809
#Sta/Elev= 30
       0 2859.05    42.7 2856.87      73 2852.31   125.7 2838.66   143.2 2829.61
   149.1 2824.75   161.2 2811.09   174.72804.971   179.4 2803.56   203.7 2803.09
   226.2 2803.17     235 2805.02   243.7 2806.36   291.9 2806.59   407.1 2804.06
   422.9 2809.51   458.5 2810.69   493.7 2809.32   519.2 2812.09   593.8 2812.73
   657.1 2819.11   940.1 2820.08   958.5    2823   986.8 2824.02   994.9 2823.06
  1007.1 2825.47  1035.4  2839.8  1063.4 2856.84  1091.6 2869.33  1102.4 2871.47
#Mann= 7 ,-1,0
       0      .1       0   174.7    .045       0     235      .1       0
   519.2     .05       0   940.1     .07       0   958.5    .016       0
   986.8      .1       0
#XS Ineff= 2 , 0
                          465.13         2816.48
Permanent Ineff=
       F       F
Bank Sta=174.7,235
XS Rating Curve= 0 ,0
Exp/Cntr(USF)=0,0
Exp/Cntr=0.3,0.1

Type RM Length L Ch R = 1 ,41747   ,345.9,346.6,348.2
XS GIS Cut Line= 3
2217676.87908467506147.6584807812218337.78753578505730.748207845
2218639.42307887505703.850770881
#Sta/Elev= 30
       0 2874.82    74.8 2869.29    84.3  2867.1   111.5  2855.3     155 2828.97
   175.3 2812.48   188.3 2808.28   199.6 2801.35   207.3 2799.19   259.3 2798.85
   268.1 2801.43   273.5 2805.29   278.2 2805.97   301.8 2803.75   344.4 2804.56
   398.6 2806.55   514.7 2806.97   581.9 2808.85   626.9 2813.56   783.8  2815.3
   807.9 2817.31   847.7 2820.05   873.6 2820.17   880.2 2820.17   892.2 2827.33
   920.4  2837.2   948.5 2850.81   972.6 2853.74   984.6 2861.45  1084.3 2898.68
#Mann= 7 ,-1,0
       0      .1       0   199.6    .045       0   268.1      .1       0
   344.4     .05       0   807.9     .06       0   847.7    .016       0
   873.6      .1       0
#XS Ineff= 2 , 0
                          405.49         2808.56
Permanent Ineff=
       F       F
Bank Sta=199.6,268.1
XS Rating Curve= 0 ,0
Exp/Cntr(USF)=0,0
Exp/Cntr=0.3,0.1

Type RM Length L Ch R = 1 ,41401   ,271.9,264.9,243.7
XS GIS Cut Line= 4
2217909.71507997506405.9407607372218182.16665049506241.799510154
2218378.13369122506141.8947442892218603.32653522506113.078036431
#Sta/Elev= 30
       0 2851.14      17 2850.86    31.5 2847.98    75.2 2830.73    86.9 2824.33
   101.4 2811.46   114.9 2806.41   121.8  2798.1     129 2795.95     171 2796.12
   180.3 2798.16   189.7 2801.58   217.7 2799.69     253 2803.02   282.1 2801.37
   337.1 2803.05   388.4 2801.61   456.8 2800.56     482 2804.81   576.3 2812.39
   588.5 2815.43   620.7 2815.84   628.8 2815.65   644.9 2826.21   669.1 2835.09
   677.2 2836.43   681.2 2836.45   685.3 2836.83   701.2 2845.38   765.1 2868.89
#Mann= 8 ,-1,0
       0      .1       0   121.8    .045       0   180.3      .1       0
   388.4     .07       0   588.5    .016       0   620.7      .1       0
   677.2    .016       0   681.2      .1       0
#XS Ineff= 2 , 0
                          340.28         2811.91
Permanent Ineff=
       F       F
Bank Sta=121.8,180.3
XS Rating Curve= 0 ,0
Exp/Cntr(USF)=0,0
Exp/Cntr=0.3,0.1

Type RM Length L Ch R = 1 ,41136   ,293.4,311,330.2
XS GIS Cut Line= 4
2218009.45260867506548.1910698312218181.89299924506557.266879862
2218362.27472359506372.3472504982218640.22140576506340.581915393
#Sta/Elev= 30
       0 2842.59    14.7 2842.15    30.8 2838.85    66.8 2824.78   114.9 2810.75
   175.9 2808.31   181.7 2804.22   187.4 2796.49   217.5 2793.73   233.2  2794.3
   239.9 2796.62   247.9 2799.86   261.9 2800.47     378 2800.16   413.1 2797.83
     431 2800.96   453.6 2798.49   477.2 2799.22   497.3 2800.13   515.1 2807.56
   545.6 2807.58   549.7 2808.64   561.8 2817.39   589.9 2825.89   610.1 2835.65
   626.2 2835.54   638.2 2842.68   646.3 2842.91   666.8 2852.22   710.8 2867.87
#Mann= 7 ,-1,0
       0      .1       0   187.4    .045       0   239.9      .1       0
   515.1    .016       0   545.6      .1       0   610.1    .016       0
   626.2      .1       0
#XS Ineff= 2 , 0
                          434.48         2807.09
Permanent Ineff=
       F       F
Bank Sta=187.4,239.9
XS Rating Curve= 0 ,0
Exp/Cntr(USF)=0,0
Exp/Cntr=0.3,0.1

Type RM Length L Ch R = 1 ,40825   ,220.1,229.7,237.6
XS GIS Cut Line= 4
2217899.44253955506743.353638417 2218276.4890111506781.228571339
2218490.20664723506721.925468292 2218671.5958156506703.334068841
#Sta/Elev= 30
       0 2823.36    77.1 2817.67   109.3 2817.86   165.6 2814.89   229.9 2813.39
   270.1  2809.8   318.3 2809.25   350.5 2805.85   394.1 2804.93   424.2 2800.69
   490.7 2800.09     499 2798.73   511.5 2793.97   523.9 2791.88   532.2 2790.38
     553 2790.37   563.9 2792.06   576.9 2798.78     582 2799.69   608.1 2799.88
   626.8 2797.36   630.9 2798.61     659 2826.97   675.1 2837.84     698 2857.33
   703.2  2860.5   731.4  2864.8   751.5 2863.71   763.7 2867.28   783.1 2868.54
#Mann= 5 ,-1,0
       0      .1       0   523.9    .045       0   563.9      .1       0
     582    .016       0   608.1      .1       0
#XS Ineff= 2 , 0
                          601.69          2804.5
Permanent Ineff=
       F       F
Bank Sta=523.9,563.9
XS Rating Curve= 0 ,0
Exp/Cntr(USF)=0,0
Exp/Cntr=0.3,0.1

Type RM Length L Ch R = 1 ,40595   ,189.9,190.3,192.6
XS GIS Cut Line= 4
2217738.73638326506873.9803176222218063.99827731506957.562272934
2218579.73379387506969.4795540132218739.80122895506886.114656148
#Sta/Elev= 30
       0 2834.17    46.5 2829.73    67.6 2829.57   100.6 2824.78   173.6 2824.29
   232.8  2816.4     340 2818.34     364 2814.41     380 2815.91     480 2811.98
   508.4  2804.8   544.1 2801.73   668.1 2798.38   677.52792.078   679.8    2791
   692.1 2788.97   724.1  2789.3   730.6 2790.94   740.1 2797.59   748.1 2798.67
   776.1  2799.9   784.1  2799.2   788.1 2801.17   804.9 2814.91   828.1 2841.39
   840.1 2848.72   964.9 2870.06   988.7 2870.45  1005.5 2877.61  1032.2 2881.02
#Mann= 6 ,-1,0
       0      .1       0   677.5    .045       0   679.8    .045       0
   730.6      .1       0   748.1    .016       0   776.1      .1       0
Bank Sta=679.8,730.6
XS Rating Curve= 0 ,0
Exp/Cntr(USF)=0,0
Exp/Cntr=0.3,0.1

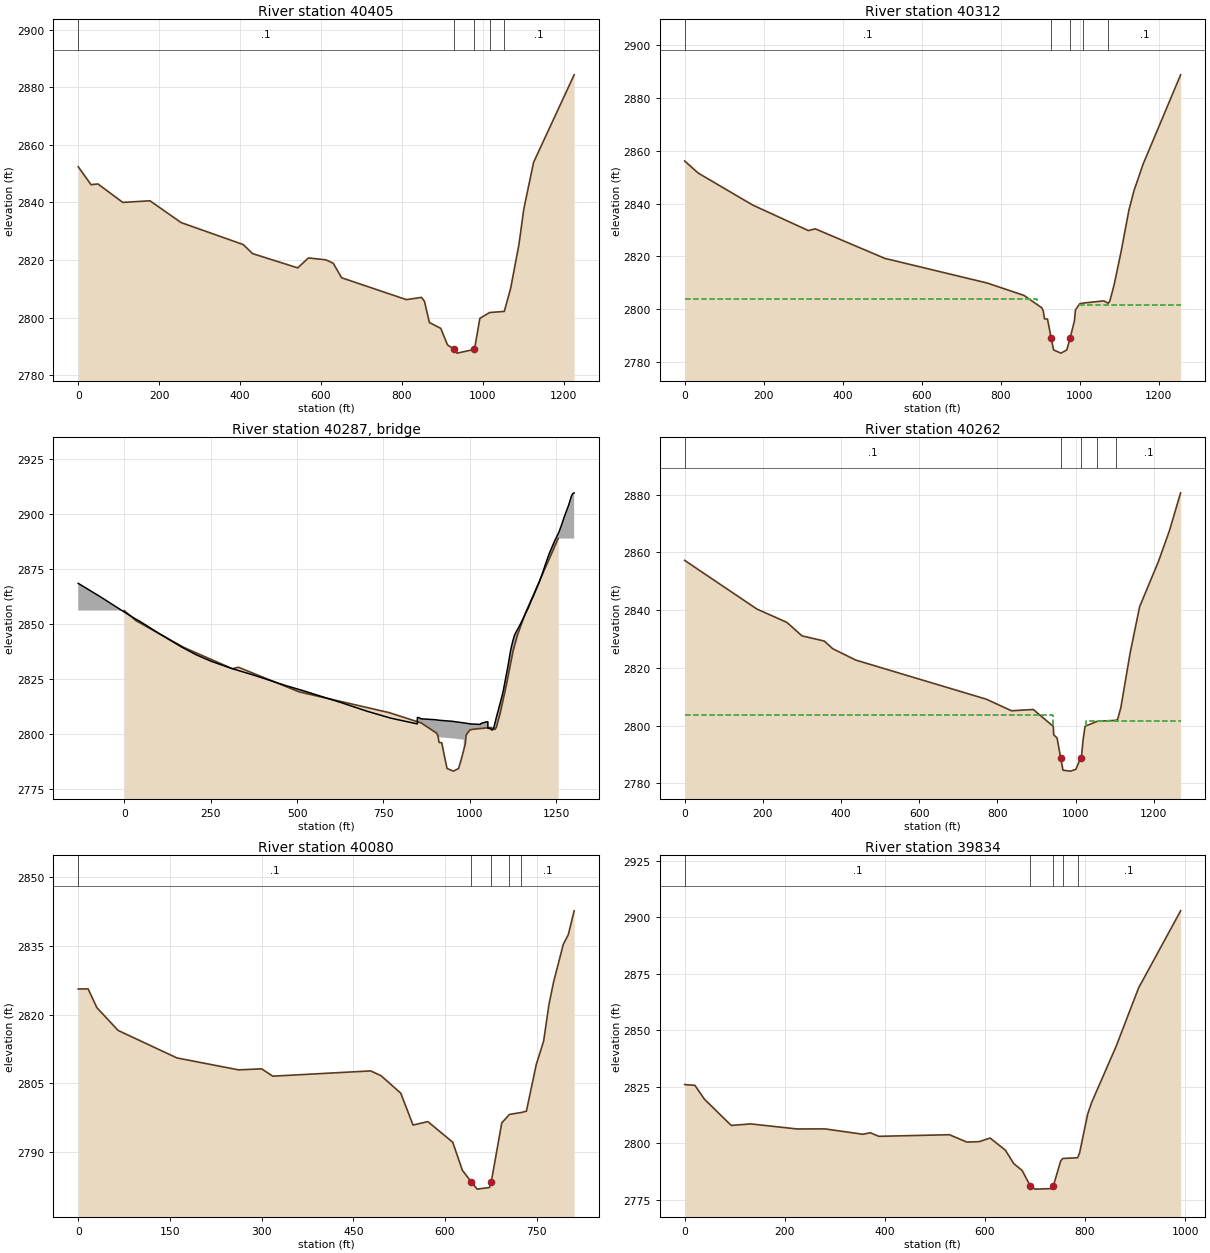
Type RM Length L Ch R = 1 ,40405   ,93,92.4,94.9
BEGIN DESCRIPTION:
xs 4
END DESCRIPTION:
XS GIS Cut Line= 5
2217498.61744236506869.6914078342217824.92736262506995.040121975
2218061.62672915507104.2859834482218222.69434542507133.698330768
2218671.89518339507182.640765868
#Sta/Elev= 30
       0  2852.4    31.7 2846.17    48.8 2846.43   110.1 2840.02   177.4 2840.57
   254.5    2833   407.9 2825.37     431 2822.23   542.6 2817.27     569 2820.73
   612.3 2820.07   630.4 2818.88     651 2813.85   811.1 2806.25   848.5 2807.03
   855.9 2805.66     868  2798.3   896.2 2796.26   912.7 2790.55   928.4 2789.05
   936.4 2787.67   979.4 2788.97   992.8 2799.77  1016.9 2801.77  1053.1 2802.16
  1068.8 2810.15  1089.3 2825.35  1101.4 2837.73  1125.5 2853.91  1225.8 2884.32
#Mann= 5 ,-1,0
       0      .1       0   928.4    .045       0   979.4      .1       0
  1016.9    .016       0  1053.1      .1       0
Bank Sta=928.4,979.4
XS Rating Curve= 0 ,0
Exp/Cntr(USF)=0,0
Exp/Cntr=0.5,0.3

Type RM Length L Ch R = 1 ,40312   ,50.7,50.4,50.3
BEGIN DESCRIPTION:
xs 3
channel burned per surveyed xs
END DESCRIPTION:
XS GIS Cut Line= 6
2217496.28200792506883.495506287  2217805.602533507004.533972624
2218188.85940349507199.9921509512218249.23282629507223.149080243
2218307.12514952507236.3816112672218674.32788543507271.944038393
#Sta/Elev= 30
       0 2856.19    34.2 2851.61   171.7 2839.51     313 2829.79   330.6 2830.45
   506.5 2819.25     766 2809.88   858.8  2805.2   903.6 2800.54   907.6 2799.34
  910.88 2796.31  918.51 2796.21   927.7 2789.05  933.91  2784.5  952.49  2783.3
  967.32 2784.51  975.65 2788.97  986.67  2795.6   989.1 2799.65    1000 2802.02
  1009.1 2802.29  1060.7 2803.12  1072.4 2802.21  1076.4 2803.15    1087 2809.17
  1104.8 2821.87  1124.6 2837.61  1137.3  2844.9  1160.8 2855.13  1255.4 2888.87
#Mann= 5 ,-1,0
       0      .1       0   927.7    .045       0  975.65     .06       0
  1009.1    .016       0  1072.4      .1       0
#XS Ineff= 2 , 0
           891.7  2803.7  997.05         2801.61
Permanent Ineff=
       F       F
Bank Sta=927.7,975.65
XS Rating Curve= 0 ,0
Exp/Cntr(USF)=0,0
Exp/Cntr=0.5,0.3

Type RM Length L Ch R = 3 ,40287   ,,,
BEGIN DESCRIPTION:
Bridge No.: 54075OLD030
JV notes: road deck updated based on surveyed data
channel burned per survey data
END DESCRIPTION:
Bridge Culvert--1,0,-1,-1, 0
Deck Dist Width WeirC Skew NumUp NumDn MinLoCord MaxHiCord MaxSubmerge Is_Ogee
15,24,2.6,0, 60, 60, , , 0.98, 0, 0,0,,
    -133 -67.652  -6.689  34.253  43.301  99.864 165.325 208.471  251.22 310.855
 374.563 467.308 510.714 628.271 704.008 771.352     848     848 852.843   858.2
  904.04  906.76   948.1  982.05 1002.56 1029.661031.7481036.526 1048.57    1052
    10521057.6261064.6291068.6441077.3421092.7321096.7471108.7911112.8061116.776
1120.8361124.8511128.865 1132.881144.9241168.5321177.0421185.0721201.1311213.175
 1217.191229.2341245.2931257.4351265.3671273.3971285.4411293.4711297.4851301.566
2868.544 2862.342856.2152852.2272851.5022845.8832839.7122836.107  2833.22829.905
2826.8912822.1372820.1592814.376 2810.422807.3422804.7372807.6372807.601 2807.06
  2806.6 2806.45 2805.93 2805.21 2804.72 2804.51 2804.892805.1812805.6642805.662
2802.7622802.6632801.9412802.7762808.1612817.2782819.9712829.9152833.5132837.282
2840.2682842.7942844.9322846.2372849.6782857.3242860.5192863.2982869.3582874.613
 2876.622881.972 2887.862891.796 2895.162898.9352903.9492908.0922909.3022909.645
                                                                                
                                                                                
          2798.7  2798.2 2797.57
                                                                                
                                                                                
                                                                                
     -93 -27.652  33.311  74.253  83.301 139.864 205.325 248.471  291.22 350.855
 414.563 507.308 550.714 668.271 744.008 811.352     888     888 892.843   898.2
  944.04  946.76   988.1 1022.05 1042.56 1069.661071.7481076.526 1088.57    1092
    10921097.6261104.6291108.6441117.3421132.7321136.7471148.7911152.8061156.776
1160.8361164.8511168.865 1172.881184.9241208.5321217.0421225.0721241.1311253.175
 1257.191269.2341285.2931297.4351305.3671313.3971325.4411333.4711337.4851341.566
2868.544 2862.342856.2152852.2272851.5022845.8832839.7122836.107  2833.22829.905
2826.8912822.1372820.1592814.376 2810.422807.3422804.7372807.6372807.601 2807.06
  2806.6 2806.45 2805.93 2805.21 2804.72 2804.51 2804.892805.1812805.6642805.662
2802.7622802.6632801.9412802.7762808.1612817.2782819.9712829.9152833.5132837.282
2840.2682842.7942844.9322846.2372849.6782857.3242860.5192863.2982869.3582874.613
 2876.622881.972 2887.862891.796 2895.162898.9352903.9492908.0922909.3022909.645
                                                                                
                                                                                
          2798.7  2798.2 2797.57
                                                                                
                                                                                
                                                                                
BR Coef=-1 ,-1 , 0 ,, 0 ,,,0.8,0,1,0,
WSPro=,,,, 1 ,,,, 0 ,,,, 0 ,,,,-1 ,-1 ,-1 , 0 , 0 , 0 , 0 , 0
BR U #Sta/Elev= 30
       0 2856.19    34.2 2851.61   171.7 2839.51     313 2829.79   330.6 2830.45
   506.5 2819.25     766 2809.88   858.8  2805.2   903.6 2800.54   907.6 2799.34
  910.88 2796.31  918.51 2796.21   927.7 2789.05  933.91  2784.5  952.49  2783.3
  967.32 2784.51  975.65 2788.97  986.67  2795.6   989.1 2799.65    1000 2802.02
  1009.1 2802.29  1060.7 2803.12  1072.4 2802.21  1076.4 2803.15    1087 2809.17
  1104.8 2821.87  1124.6 2837.61  1137.3  2844.9  1160.8 2855.13  1255.4 2888.87
BR U #Mann= 5
       0      .1   927.7     .04  975.65     .06  1009.1    .016  1072.4      .1
BR D #Sta/Elev= 30
       0 2857.24   184.9 2840.37   261.3 2835.77     300 2831.09     357 2829.29
   378.9 2826.61   438.1 2822.67   771.7 2809.13   836.1 2805.12   891.8 2805.57
   943.1  2799.7  943.95  2796.8  952.62 2795.71  961.91 2788.79  967.85 2784.51
  987.19  2784.2 1000.76 2784.85  1012.7 2788.64 1015.31  2789.5  1019.3  2795.2
  1024.3 2799.75  1055.4 2801.46  1103.6 2801.81  1107.6 2802.19  1115.7 2806.15
  1139.7 2825.26  1163.8 2841.17    1212 2856.87  1240.1 2867.53  1268.7 2880.66
BR D #Mann= 5
       0      .1  961.91     .04  1012.7     .06  1055.4    .016  1103.6      .1
BC Design=,, 0 ,, 0 ,,,,,,
BC Use User HTab Curves=0
BC User HTab FreeFlow(D)= 0

Type RM Length L Ch R = 1 ,40262   ,181.3,181.4,182.7
BEGIN DESCRIPTION:
xs 2
channel burned per surveyed xs
END DESCRIPTION:
XS GIS Cut Line= 6
2217464.37832994506906.3953688582217528.05988549506942.784829174
2217851.42986238507084.2075044922218274.04382196507279.387337094
2218317.04954779507288.4847021732218648.68985657507317.430863788
#Sta/Elev= 30
       0 2857.24   184.9 2840.37   261.3 2835.77     300 2831.09     357 2829.29
   378.9 2826.61   438.1 2822.67   771.7 2809.13   836.1 2805.12   891.8 2805.57
   943.1  2799.7  943.95  2796.8  952.62 2795.71  961.91 2788.79  967.85 2784.51
  987.19  2784.2 1000.76 2784.85  1012.7 2788.64 1015.31  2789.5  1019.3  2795.2
  1024.3 2799.75  1055.4 2801.46  1103.6 2801.81  1107.6 2802.19  1115.7 2806.15
  1139.7 2825.26  1163.8 2841.17    1212 2856.87  1240.1 2867.53  1268.7 2880.66
#Mann= 5 ,-1,0
       0      .1       0  961.91    .045       0  1012.7     .06       0
  1055.4    .016       0  1103.6      .1       0
#XS Ineff= 2 , 0
           942.4  2803.7  1026.4         2801.61
Permanent Ineff=
       F       F
Bank Sta=961.91,1012.7
XS Rating Curve= 0 ,0
Exp/Cntr(USF)=0,0
Exp/Cntr=0.5,0.3

Type RM Length L Ch R = 1 ,40080   ,239.4,246.7,252.8
BEGIN DESCRIPTION:
xs 1
END DESCRIPTION:
XS GIS Cut Line= 4
2217777.29742581507225.6387951652218024.47098279507388.888307216
2218213.01267277507455.5676853772218525.71596345507493.505952262
#Sta/Elev= 30
       0  2825.6    16.2 2825.62    30.6 2821.51    65.3 2816.54   161.6 2810.54
   262.3 2807.94   300.1 2808.16   318.2 2806.56   478.3 2807.71   495.3 2806.67
   527.6 2802.85   547.7 2795.89   571.9 2796.64   612.6 2792.14   628.3 2786.04
   642.4 2783.56   652.5  2781.9   672.7 2782.26   675.6 2783.46   692.8 2796.35
   705.3 2798.21     725 2798.64   733.1 2798.92   749.2 2809.09   761.3 2814.24
     770 2822.21   777.4 2827.04   793.5 2835.37   801.6 2837.44   811.2 2842.66
#Mann= 5 ,-1,0
       0      .1       0   642.4    .045       0   675.6      .1       0
   705.3    .016       0     725      .1       0
Bank Sta=642.4,675.6
XS Rating Curve= 0 ,0
Exp/Cntr(USF)=0,0
Exp/Cntr=0.3,0.1

Type RM Length L Ch R = 1 ,39834   ,221.7,219.7,217.9
XS GIS Cut Line= 4
2217687.80946827507381.1666597362217992.43673046507593.132999193
2218369.00084795507735.3051660012218582.74862372507774.959970627
#Sta/Elev= 30
       0 2825.93    20.4 2825.61    39.4 2819.48      93 2807.85     132 2808.52
   224.4 2806.28   280.2 2806.31   356.2 2803.93   370.8  2804.6   387.9 2803.02
     529 2803.73   563.8 2800.47   588.9 2800.68   610.3 2802.26     641 2796.86
   657.3 2791.01   674.4 2787.87   690.6 2781.03   699.9 2779.63   733.6 2779.86
  736.58    2781   751.4 2792.12   755.6 2793.22   785.2 2793.53   789.1 2795.64
   805.3 2812.91   813.5 2818.16   862.3 2842.96     907 2868.73     991  2902.9
#Mann= 5 ,-1,0
       0      .1       0   690.6    .045       0  736.58      .1       0
   755.6    .016       0   785.2      .1       0
Bank Sta=690.6,736.58
XS Rating Curve= 0 ,0
Exp/Cntr=0.3,0.1

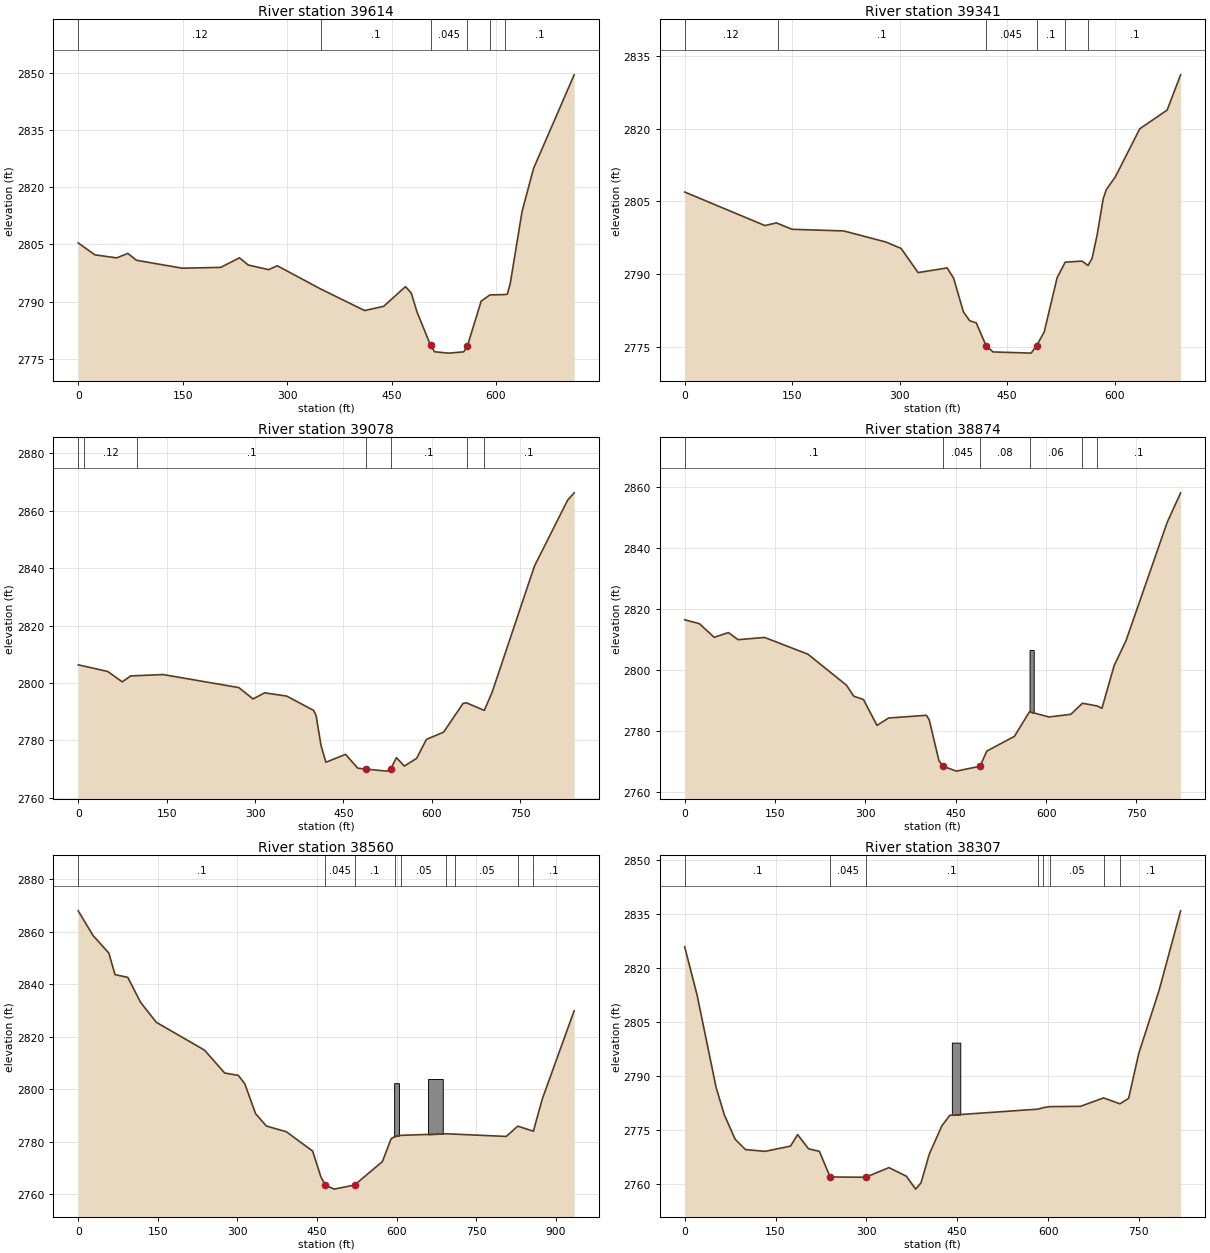
Type RM Length L Ch R = 1 ,39614   ,266.8,273.3,280.8
XS GIS Cut Line= 4
2217783.15194803507681.2139928512217952.09057502507833.288686369
2218311.55875436 507943.098934162218415.91796151507974.533079728
#Sta/Elev= 30
       0 2805.39    23.9 2802.26    55.2 2801.46    71.3 2802.63    83.7 2800.83
   149.4 2798.75   204.6 2798.97   231.6 2801.47   244.1  2799.6   273.4 2798.37
   285.9  2799.4     348 2793.32   411.4 2787.65   438.7 2788.77     470 2793.92
   478.3 2792.24   486.5  2787.3     506 2778.55   511.8 2776.85   531.6 2776.49
   553.6 2776.82   558.8 2778.33   578.7 2790.13   591.3 2791.75   612.9 2791.84
   616.3 2791.97   620.5 2794.82   637.4 2813.63   653.9  2824.9   712.2 2849.45
#Mann= 6 ,-1,0
       0     .12       0     348      .1       0     506    .045       0
   558.8     .08       0   591.3    .016       0   612.9      .1       0
Bank Sta=506,558.8
XS Rating Curve= 0 ,0
Exp/Cntr(USF)=0,0
Exp/Cntr=0.3,0.1

Type RM Length L Ch R = 1 ,39341   ,271,262.7,254.7
XS GIS Cut Line= 3
     2217751.379      507969.3272218222.98619015508215.616540353
2218373.93718675508269.173024658
#Sta/Elev= 30
       0 2806.91     112 2799.99     128 2800.54   149.8 2799.22     222 2798.88
   280.7  2796.6   302.1 2795.27   325.8 2790.28   366.4 2791.25   375.4 2789.12
     389 2782.19   397.7 2780.36     407  2779.9   420.6 2775.21   430.3 2773.91
   483.6 2773.66   491.2 2775.21   501.8 2778.02   519.8 2789.22   531.1 2792.43
   554.5 2792.66     563 2791.76   568.7 2793.23   575.7 2798.09   584.2 2805.55
   588.5 2807.41   601.2 2810.07   635.2 2819.97   673.4 2823.82   692.2  2831.1
#Mann= 6 ,-1,0
       0     .12       0     130      .1       0   420.6    .045       0
   491.2      .1       0   531.1    .016       0     563      .1       0
Bank Sta=420.6,491.2
XS Rating Curve= 0 ,0
Exp/Cntr=0.3,0.1

Type RM Length L Ch R = 1 ,39078   ,204,204.2,204.8
XS GIS Cut Line= 4
2217664.50702149508108.5301588182217845.18286932 508359.23540502
2218200.93221309508460.0777386882218363.40041733508457.276562753
#Sta/Elev= 30
       0  2806.3    50.1 2803.97    74.7 2800.36    89.1 2802.43   143.8  2802.9
   272.4 2798.36   296.6  2794.4   316.3 2796.53   353.7 2795.39   399.4 2790.39
   403.6 2788.58   411.9 2778.16   420.2 2772.33   453.5 2775.07   474.3 2770.25
   487.9 2769.94   523.6 2769.23   530.1 2769.95   539.8 2773.93   553.3 2770.99
   574.1 2773.69   590.7  2780.3   619.8 2782.81   652.9 2792.86   658.7 2793.04
   688.8  2790.4     702 2796.64     774 2840.74   830.3 2863.73   841.3 2866.26
#Mann= 7 ,-1,0
       0      .1       0      10     .12       0     100      .1       0
   487.9    .045       0   530.1      .1       0   658.7    .016       0
   688.8      .1       0
Bank Sta=487.9,530.1
XS Rating Curve= 0 ,0
Exp/Cntr(USF)=0,0
Exp/Cntr=0.3,0.1

Type RM Length L Ch R = 1 ,38874   ,315,313.8,311.6
XS GIS Cut Line= 4
2217535.65292847508555.3177204852217826.97522574508563.721248291
2218102.89105535 508646.355938382218346.59336172508656.160054153
#Sta/Elev= 30
       0 2816.58    24.5 2815.29      49 2810.82    72.6 2812.38    88.6 2810.05
   132.6 2810.78   204.6 2805.29   268.6 2795.11   280.6 2791.52   296.9 2790.39
   319.3 2781.92   338.6 2784.34   401.3 2785.23     406 2783.76   422.1  2770.4
   428.5 2768.57     451 2766.91  490.53 2768.52   501.5 2773.46   547.5 2778.33
   572.5  2786.4   604.8 2784.68   641.1 2785.55   660.4 2789.19   684.8  2788.3
   692.8 2787.53   712.9 2801.46   732.9  2809.8   800.9 2848.46   823.4 2858.24
#Mann= 6 ,-1,0
       0      .1       0   428.5    .045       0  490.53     .08       0
   572.5     .06       0   660.4    .016       0   684.8      .1       0
#Block Obstruct= 1 ,-1
  572.57  579.47 2806.65
Bank Sta=428.5,490.53
XS Rating Curve= 0 ,0
Exp/Cntr(USF)=0,0
Exp/Cntr=0.3,0.1

Type RM Length L Ch R = 1 ,38560   ,275.3,253.1,198.3
XS GIS Cut Line= 4
2217419.40412716508948.8829393832217783.55699874508883.055304906
2218010.45224949508940.4794115782218325.58454221508842.438253845
#Sta/Elev= 30
       0    2868    27.9  2858.6    57.7  2851.9    69.3 2843.68    93.4 2842.63
   117.5 2833.09   147.1 2825.49   237.9 2814.89   275.8 2806.17   301.6 2805.25
   313.8 2802.06   334.1 2790.65   354.4 2785.95   392.1 2783.76   441.5  2776.4
   457.3 2766.46   465.6  2763.4   482.1 2761.89   520.5 2763.45   572.9 2772.39
   589.4  2781.1   597.6  2782.1   607.8 2782.39   692.9 2782.99   710.6 2782.84
   806.2 2781.98   827.9 2785.91   857.3 2783.97     874  2796.2   934.1  2829.9
#Mann= 9 ,-1,0
       0      .1       0   465.6    .045       0   520.5      .1       0
   597.6    .016       0   607.8     .05       0   692.9    .016       0
   710.6     .05       0   827.9    .016       0   857.3      .1       0
#Block Obstruct= 2 ,-1
     595   604.1 2802.29  658.96  686.66 2803.87
Bank Sta=465.6,520.5
XS Rating Curve= 0 ,0
Exp/Cntr(USF)=0,0
Exp/Cntr=0.3,0.1

Type RM Length L Ch R = 1 ,38307   ,440.4,405.2,344
XS GIS Cut Line= 3
  2217637.899815 509281.935312422218031.46106901509081.938796306
2218394.73670624 508979.93904607
#Sta/Elev= 30
       0 2826.01    20.5 2812.57    51.9 2786.91    65.4 2779.32    83.3 2772.52
   100.4 2769.64   132.7 2769.15   174.8 2770.61   186.5  2773.8   204.5 2769.85
   222.4 2769.16   240.1 2762.03   298.7 2761.95   337.2 2764.63     366 2762.24
   381.3 2758.65   390.2 2760.39   403.9  2768.4   424.7 2776.26   437.8 2779.17
   583.5 2780.88   592.2  2781.3   603.1 2781.57   653.5 2781.66   691.5    2784
   718.7 2782.36     733 2783.89   749.7 2796.37   783.3 2813.92   818.8 2835.99
#Mann= 8 ,-1,0
       0      .1       0   240.1    .045       0   298.7      .1       0
   583.5     .05       0   592.2    .016       0   603.1     .05       0
   691.5    .016       0   718.7      .1       0
#Block Obstruct= 1 ,-1
  441.11     455 2799.36
Bank Sta=240.1,298.7
XS Rating Curve= 0 ,0
Exp/Cntr(USF)=0,0
Exp/Cntr=0.3,0.1

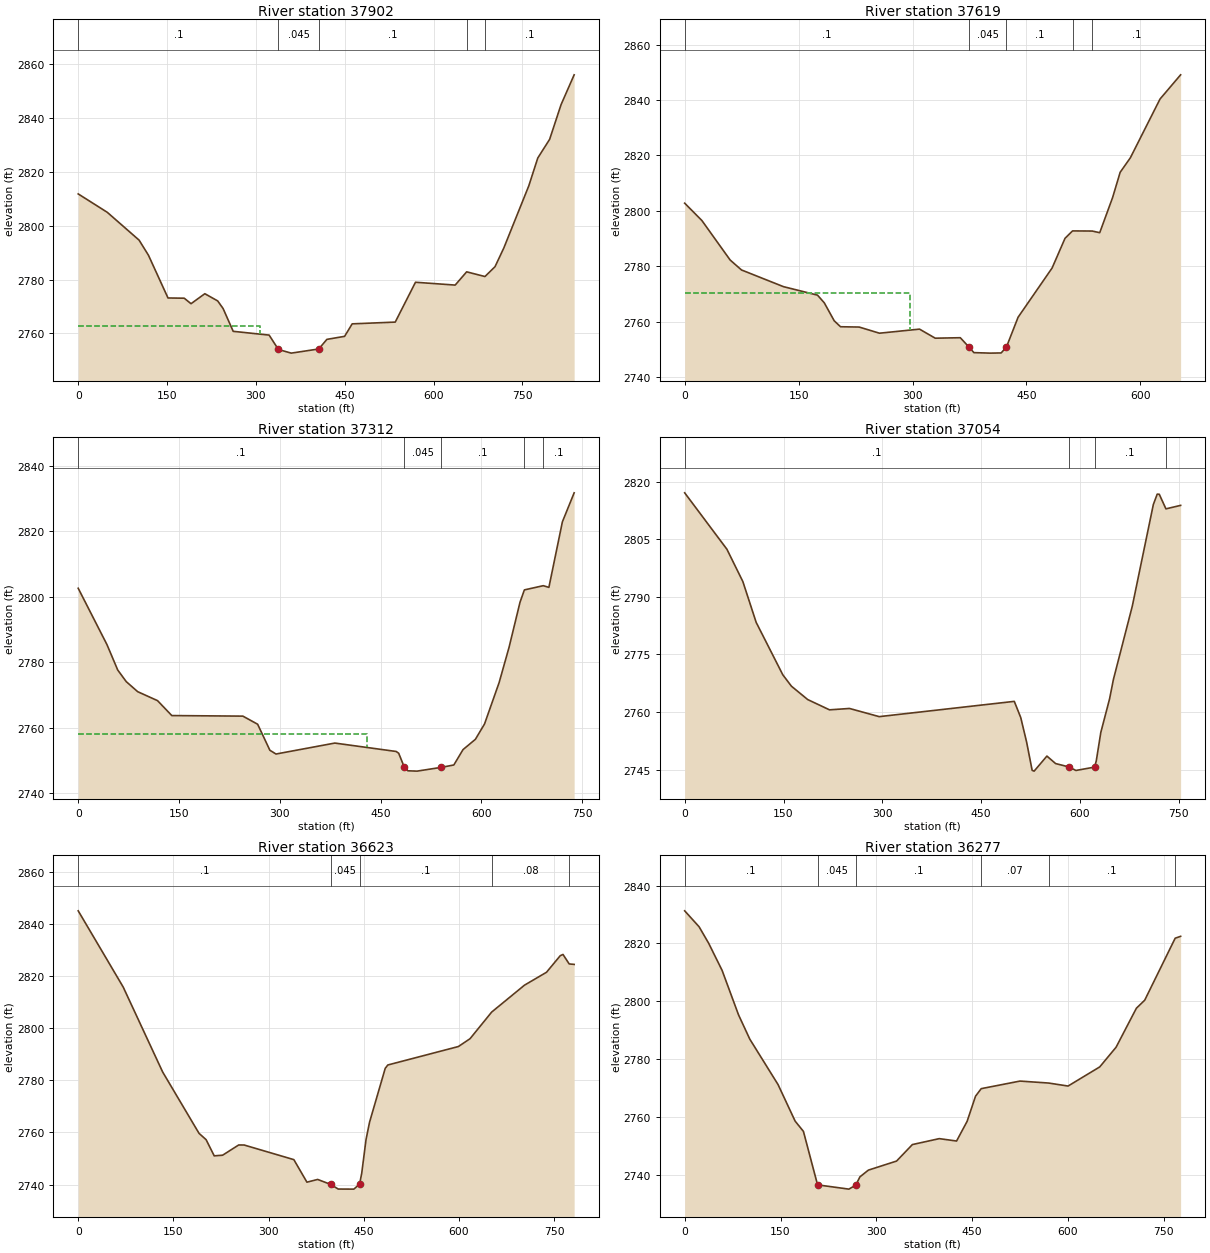
Type RM Length L Ch R = 1 ,37902   ,249.3,282.8,314.2
XS GIS Cut Line= 4
2217967.91171284 509654.176559662218139.30634251509534.328709844
2218270.96161147509185.5823059092218482.48841203509042.238055611
#Sta/Elev= 30
       0 2811.73    49.1 2804.91   102.8  2794.6   118.7 2788.97   151.6 2773.16
     179 2773.08   190.5 2771.04   213.8 2774.74   235.5 2772.07   244.6 2769.27
   261.7  2760.8   322.4  2759.4     338 2754.07   359.7 2752.72   406.2 2754.26
   419.9 2757.82   449.8 2758.94   462.6 2763.57   535.3 2764.22   569.5 2778.99
   636.5 2777.94   655.9 2782.85   686.8 2781.11   703.8 2784.76   718.7 2791.72
   760.9 2814.77     776 2825.05     796 2831.96   815.3 2844.82   837.4 2855.87
#Mann= 5 ,-1,0
       0      .1       0     338    .045       0   406.2      .1       0
   655.9    .016       0   686.8      .1       0
#XS Ineff= 2 , 0
          307.78 2762.84
Permanent Ineff=
       F       F
Bank Sta=338,406.2
XS Rating Curve= 0 ,0
Exp/Cntr=0.3,0.1

Type RM Length L Ch R = 1 ,37619   ,309.2,307,304.7
XS GIS Cut Line= 2
2218063.93554386509729.3670104542218647.30861734509436.023810525
#Sta/Elev= 30
       0 2802.77    22.7 2796.49    59.9 2782.25    74.8 2778.67   130.1 2772.64
   174.9 2769.58   183.8 2766.82   196.9 2760.33   205.2 2758.18   229.7 2758.07
   256.5 2755.85   309.2 2757.32   329.9 2754.05   362.9 2754.22   374.4 2750.83
   380.8 2748.84   402.5 2748.66   416.7 2748.73  423.692750.869     439 2761.61
   483.8 2779.38   500.8 2790.09   510.7 2792.76   536.6 2792.71   546.5 2792.12
   563.4 2804.76   573.4 2813.91   586.8 2819.13   625.9 2840.35     653 2849.08
#Mann= 5 ,-1,0
       0      .1       0   374.4    .045       0  423.69      .1       0
   510.7    .016       0   536.6      .1       0
#XS Ineff= 2 , 0
          297.25 2770.22
Permanent Ineff=
       F       F
Bank Sta=374.4,423.69
XS Rating Curve= 0 ,0
Exp/Cntr(USF)=0,0
Exp/Cntr=0.3,0.1

Type RM Length L Ch R = 1 ,37312   ,252.8,258.3,260.2
XS GIS Cut Line= 3
2218076.56783317510038.2859954492218318.58160237509954.505100126
2218741.14792063509722.383801312
#Sta/Elev= 30
       0 2802.62    42.9 2785.35    58.8 2777.63    71.5 2774.07    88.5    2771
   118.1 2768.25   139.3 2763.69   245.1 2763.52   267.1 2761.04   285.3 2753.08
   294.4 2751.93     382 2755.28   473.3 2752.71     477 2752.18   485.1 2748.06
   490.7  2746.8   504.4  2746.7   540.3 2747.85   559.1 2748.58   572.8 2753.28
   591.2 2756.43   604.8 2761.12   626.5 2773.76   641.3 2784.56   657.6 2798.33
   664.1 2802.12   692.2 2803.41   700.6 2802.89   720.7 2822.94   738.2 2831.81
#Mann= 5 ,-1,0
       0      .1       0   485.1    .045       0   540.3      .1       0
   664.1    .016       0   692.2      .1       0
#XS Ineff= 2 , 0
          429.56 2758.18
Permanent Ineff=
       F       F
Bank Sta=485.1,540.3
XS Rating Curve= 0 ,0
Exp/Cntr=0.3,0.1

Type RM Length L Ch R = 1 ,37054   ,387.7,430.2,448.1
XS GIS Cut Line= 3
2218120.70871503510259.652027695 2218269.5610235510238.824457551
2218816.41577242509986.467570809
#Sta/Elev= 30
       0  2817.1    64.1  2802.4    88.3 2793.97   108.5 2783.34   148.9 2769.69
     162 2766.71   186.7 2763.23   219.8 2760.55   250.1 2760.91   295.2 2758.78
   500.2 2762.76     510 2758.53   518.8 2752.23   527.3 2744.79   530.3 2744.58
   549.7  2748.5   562.9 2746.55   583.8 2745.64   593.7 2744.75     622 2745.63
   624.6 2747.24   631.5 2754.66   644.8 2763.41   650.6 2768.46   679.3 2787.59
   711.2 2814.05   717.1 2816.76   720.2 2816.73   730.3 2812.92   752.6 2813.83
#Mann= 4 ,-1,0
       0      .1       0   583.8    .045       0     622      .1       0
   730.3    .016       0
Bank Sta=583.8,622
XS Rating Curve= 0 ,0
Exp/Cntr(USF)=0,0
Exp/Cntr=0.3,0.1

Type RM Length L Ch R = 1 ,36623   ,364.8,346.5,318.6
XS GIS Cut Line= 4
2218231.74514838510534.3485187162218482.45039458510439.108536919
2218709.34564533510493.7314676562218968.45441934510387.286782118
#Sta/Elev= 30
       0 2844.97    70.9 2815.74   133.1 2783.16   190.4 2759.64   201.6 2757.19
   214.4 2750.99   227.6 2751.24   252.9 2755.16   261.5 2755.15   339.9 2749.54
   360.5  2740.9   377.4 2741.94   397.8 2740.06   409.8 2738.26   434.5 2738.23
  443.532740.165   446.9 2744.37   453.7 2757.29   459.2 2763.89   483.9 2784.54
     488 2785.84   599.2 2792.92   617.6 2795.92   651.7 2806.14   703.5 2816.47
   738.1  2821.4   759.8 2827.76   764.1 2828.24   773.9  2824.6   781.7 2824.42
#Mann= 5 ,-1,0
       0      .1       0   397.8    .045       0  443.53      .1       0
   651.7     .08       0   773.9    .016       0
Bank Sta=397.8,443.53
XS Rating Curve= 0 ,0
Exp/Cntr(USF)=0,0
Exp/Cntr=0.3,0.1

Type RM Length L Ch R = 1 ,36277   ,354.5,339.3,308.3
XS GIS Cut Line= 2
2218343.79218578510902.7031541982219046.88734552 510573.56498181
#Sta/Elev= 30
       0 2831.29    22.5  2825.8    37.5 2820.09    58.6 2810.68    84.3  2795.3
     102 2786.88   146.2 2771.17   172.9 2758.54   185.9 2754.98     208 2736.49
   257.1 2735.01   267.8  2736.4   274.3 2739.25   287.5 2741.58   331.7 2744.72
   356.4 2750.42   398.5 2752.48   425.6 2751.65   442.1 2758.46   455.3 2767.17
   464.2 2769.77   524.9 2772.39   569.7 2771.71   600.1 2770.67   649.7 2777.29
   675.3 2784.11   707.1  2797.6   720.1 2800.37   767.8 2821.82   776.3 2822.47
#Mann= 6 ,-1,0
       0      .1       0     208    .045       0   267.8      .1       0
   464.2     .07       0   569.7      .1       0   767.8    .016       0
Bank Sta=208,267.8
XS Rating Curve= 0 ,0
Exp/Cntr(USF)=0,0
Exp/Cntr=0.3,0.1

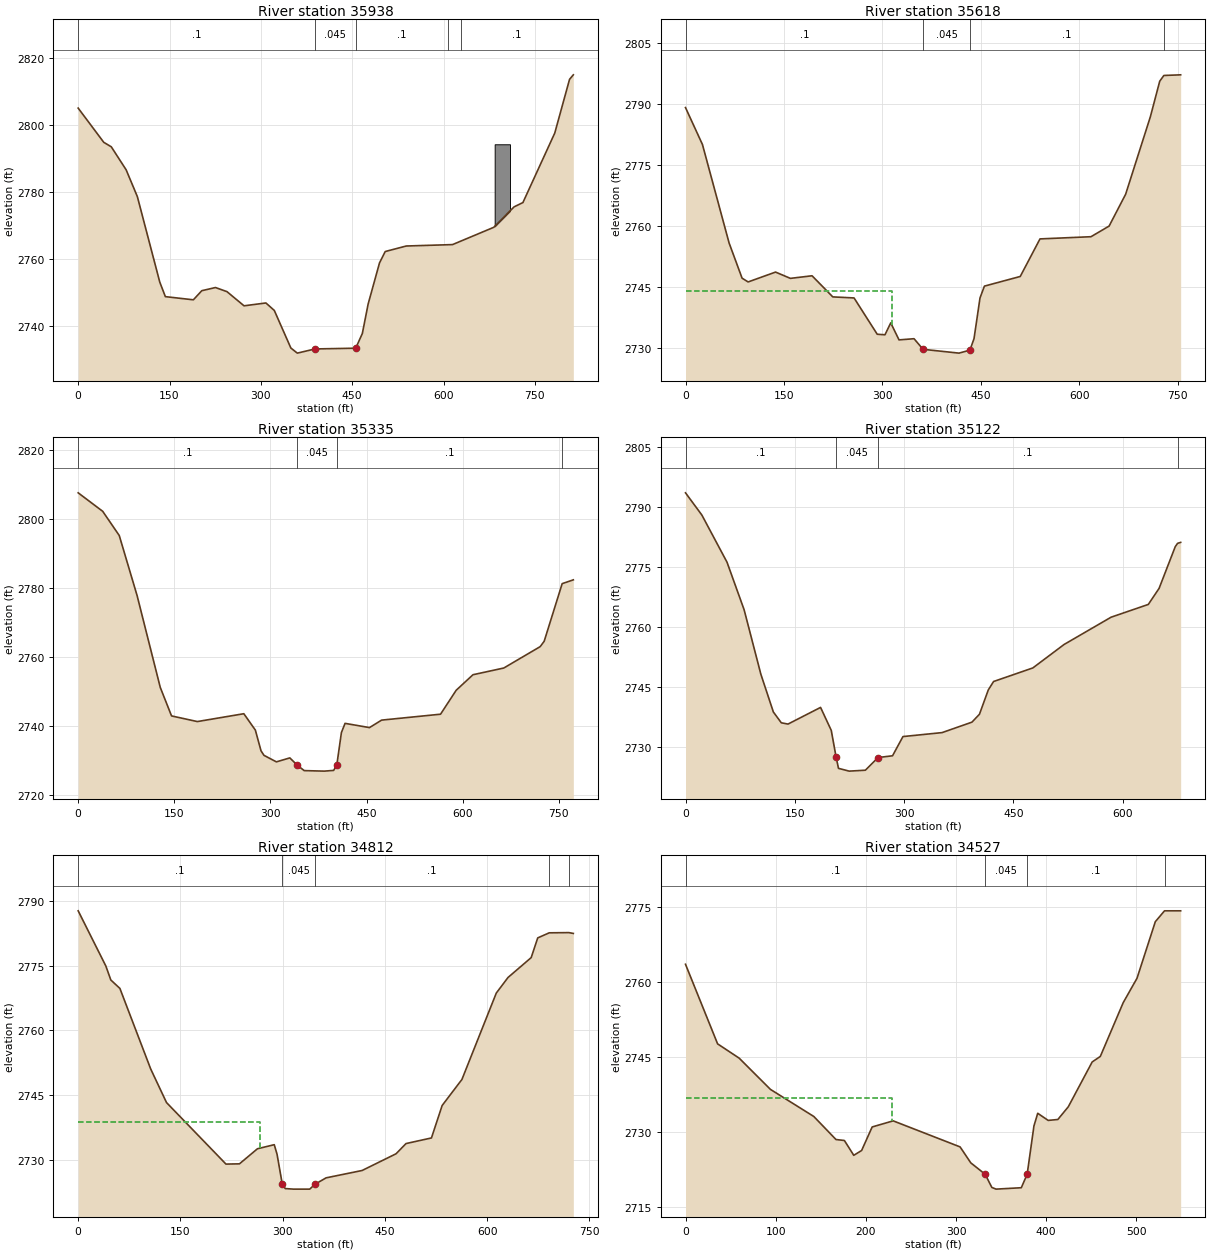
Type RM Length L Ch R = 1 ,35938   ,283.5,319.6,334.1
XS GIS Cut Line= 4
2218507.66097799511236.043090488  2218766.769752 511088.98135389
2218887.22031722510892.8990384242219125.32027171510736.033186052
#Sta/Elev= 30
       0 2805.11      42  2794.9    54.4 2793.55    78.8 2786.68    97.2 2778.68
     134 2753.16   143.2 2748.81   189.2 2747.86     203 2750.58   225.5 2751.53
   244.4  2750.3   272.4 2746.07   308.3 2746.92   322.1 2744.69   349.3 2733.47
   359.9 2731.94     389 2733.19   455.8 2733.41   466.7  2737.8   476.2 2746.59
   494.9 2758.88   504.3 2762.28   538.8 2763.93   614.8 2764.35   682.5 2769.51
     716 2775.63   730.4  2776.9   782.7 2797.65     807  2813.7   813.2 2815.05
#Mann= 5 ,-1,0
       0      .1       0     389    .045       0   455.8      .1       0
  608.06     .07       0  628.06      .1       0
#Block Obstruct= 1 ,-1
  684.02  709.12 2794.31
Bank Sta=389,455.8
XS Rating Curve= 0 ,0
Exp/Cntr(USF)=0,0
Exp/Cntr=0.3,0.1

Type RM Length L Ch R = 1 ,35618   ,279.3,283.4,282.9
XS GIS Cut Line= 4
 2218685.9906721511413.8963688332218841.50565697511322.067777854
2219258.37612863511091.7825298252219320.43738086 511016.57598523
#Sta/Elev= 30
       0 2789.19    25.8 2780.11    66.4 2755.86    86.2 2747.18    95.4 2746.25
   137.2 2748.68   159.8 2747.13   192.8 2747.77   224.4 2742.57   256.8 2742.31
   292.1 2733.37   303.9 2733.24   312.7 2736.17   325.3 2731.98   348.2 2732.27
   361.9 2729.66   416.7 2728.72   433.4 2729.46   439.6 2732.31   448.7 2742.31
   455.4 2745.22     510  2747.6   540.1 2756.85   617.8 2757.39   645.4 2760.01
   670.6 2767.86   708.3 2786.96   722.5 2795.68   728.8  2797.1   754.4 2797.26
#Mann= 4 ,-1,0
       0      .1       0   361.9    .045       0   433.4      .1       0
   728.8    .016       0
#XS Ineff= 2 , 0
          314.14 2744.12
Permanent Ineff=
       F       F
Bank Sta=361.9,433.4
XS Rating Curve= 0 ,0
Exp/Cntr(USF)=0,0
Exp/Cntr=0.3,0.1

Type RM Length L Ch R = 1 ,35335   ,215.8,212.8,204
XS GIS Cut Line= 4
2218877.41620144511736.0529949252219030.08028991511530.166563686
 2219350.8149345511369.0989474112219483.87871739      511284.847
#Sta/Elev= 30
       0 2807.62    38.3 2802.25    64.1 2795.23    91.9 2777.82   128.1 2751.13
   145.7 2742.84     186  2741.2   258.5 2743.48   276.5 2738.73   285.4 2732.68
     290 2731.39   309.3  2729.5   330.3 2730.65     342 2728.52   352.7 2726.96
     384 2726.81   398.7 2727.02  403.59 2728.58   410.8 2738.02   416.5 2740.68
   454.6 2739.45   473.5 2741.62   565.5 2743.34   589.9 2750.29   616.1  2754.8
   664.2 2756.75     721 2762.96   727.2 2764.51   755.3 2781.25   772.7 2782.35
#Mann= 4 ,-1,0
       0      .1       0     342    .045       0  403.59      .1       0
   755.3    .016       0
Bank Sta=342,403.59
XS Rating Curve= 0 ,0
Exp/Cntr=0.3,0.1

Type RM Length L Ch R = 1 ,35122   ,334.4,310.1,227.6
XS GIS Cut Line= 3
2219020.97098508511810.1783406192219342.41140669511581.988318488
2219519.33609196511357.921766375
#Sta/Elev= 30
       0 2793.45    22.5 2787.89      57 2776.12    80.5 2764.23   103.4 2748.18
   120.6 2738.72   131.5 2736.02   140.7  2735.7   185.4 2739.86   200.1 2734.12
   206.7  2727.5     210 2724.64   224.7 2723.95   246.9 2724.18   264.3 2727.34
   284.2 2727.78   298.5 2732.58   352.2 2733.57   393.2 2736.18   403.5 2738.15
   415.6 2744.21   422.9 2746.33   476.8 2749.72   519.7 2755.58   584.2 2762.39
   635.3 2765.58   650.1 2769.59   672.3 2780.01   675.5 2780.84   679.7 2781.07
#Mann= 4 ,-1,0
       0      .1       0   206.7    .045       0   264.3      .1       0
   675.5    .016       0
Bank Sta=206.7,264.3
XS Rating Curve= 0 ,0
Exp/Cntr(USF)=0,0
Exp/Cntr=0.3,0.1

Type RM Length L Ch R = 1 ,34812   ,239.3,284.3,327.8
XS GIS Cut Line= 4
2219254.95872082512074.4801056592219448.85609223511887.316495427
2219458.30152326511678.5611476282219663.34975935511539.327088469
#Sta/Elev= 30
       0 2787.66    40.6 2774.89    47.9 2771.66    61.2 2769.71   106.4 2751.07
   129.6  2743.3   216.8 2729.07   236.6 2729.13     263 2732.62   287.6 2733.56
   291.7 2731.36   299.3 2724.52   303.7 2723.41   315.7 2723.28   339.7 2723.28
   347.5 2724.42   363.7 2725.89   416.5 2727.59   466.3 2731.46   480.9 2733.82
   518.2 2735.12   533.9 2742.63   562.9 2748.65   613.3 2768.63   630.5 2772.24
   664.5 2776.84   674.1  2781.4     691 2782.57   719.8 2782.62   726.3 2782.43
#Mann= 5 ,-1,0
       0      .1       0   299.3    .045       0   347.5      .1       0
     691    .016       0   719.8      .1       0
#XS Ineff= 2 , 0
          267.27 2738.91
Permanent Ineff=
       F       F
Bank Sta=299.3,347.5
XS Rating Curve= 0 ,0
Exp/Cntr=0.3,0.1

Type RM Length L Ch R = 1 ,34527   ,202,202.2,203.6
XS GIS Cut Line= 4
2219371.95935385512124.8096205432219499.07809545512060.962512121
2219733.59508686511919.4913589142219838.28032445511837.573985526
#Sta/Elev= 30
       0 2763.51    35.6 2747.62    59.5 2744.77    94.2 2738.53   142.3 2733.12
   166.9 2728.52   176.2 2728.33   186.6 2725.37   195.3 2726.33     207 2731.03
   230.3 2732.25   304.5 2727.05   316.4 2723.86   332.3 2721.59   339.7 2718.96
   344.4 2718.62   372.4  2718.9   378.9  2721.6   386.4 2731.23   390.6 2733.76
   402.2 2732.34   412.9 2732.52   424.5 2735.06     451 2744.01     460 2745.11
   485.4 2755.85   500.7 2760.72     521 2772.01   531.2 2774.18   549.1 2774.18
#Mann= 4 ,-1,0
       0      .1       0   332.3    .045       0   378.9      .1       0
   531.2    .016       0
#XS Ineff= 2 , 0
          228.51 2736.82
Permanent Ineff=
       F       F
Bank Sta=332.3,378.9
XS Rating Curve= 0 ,0
Exp/Cntr(USF)=0,0
Exp/Cntr=0.3,0.1