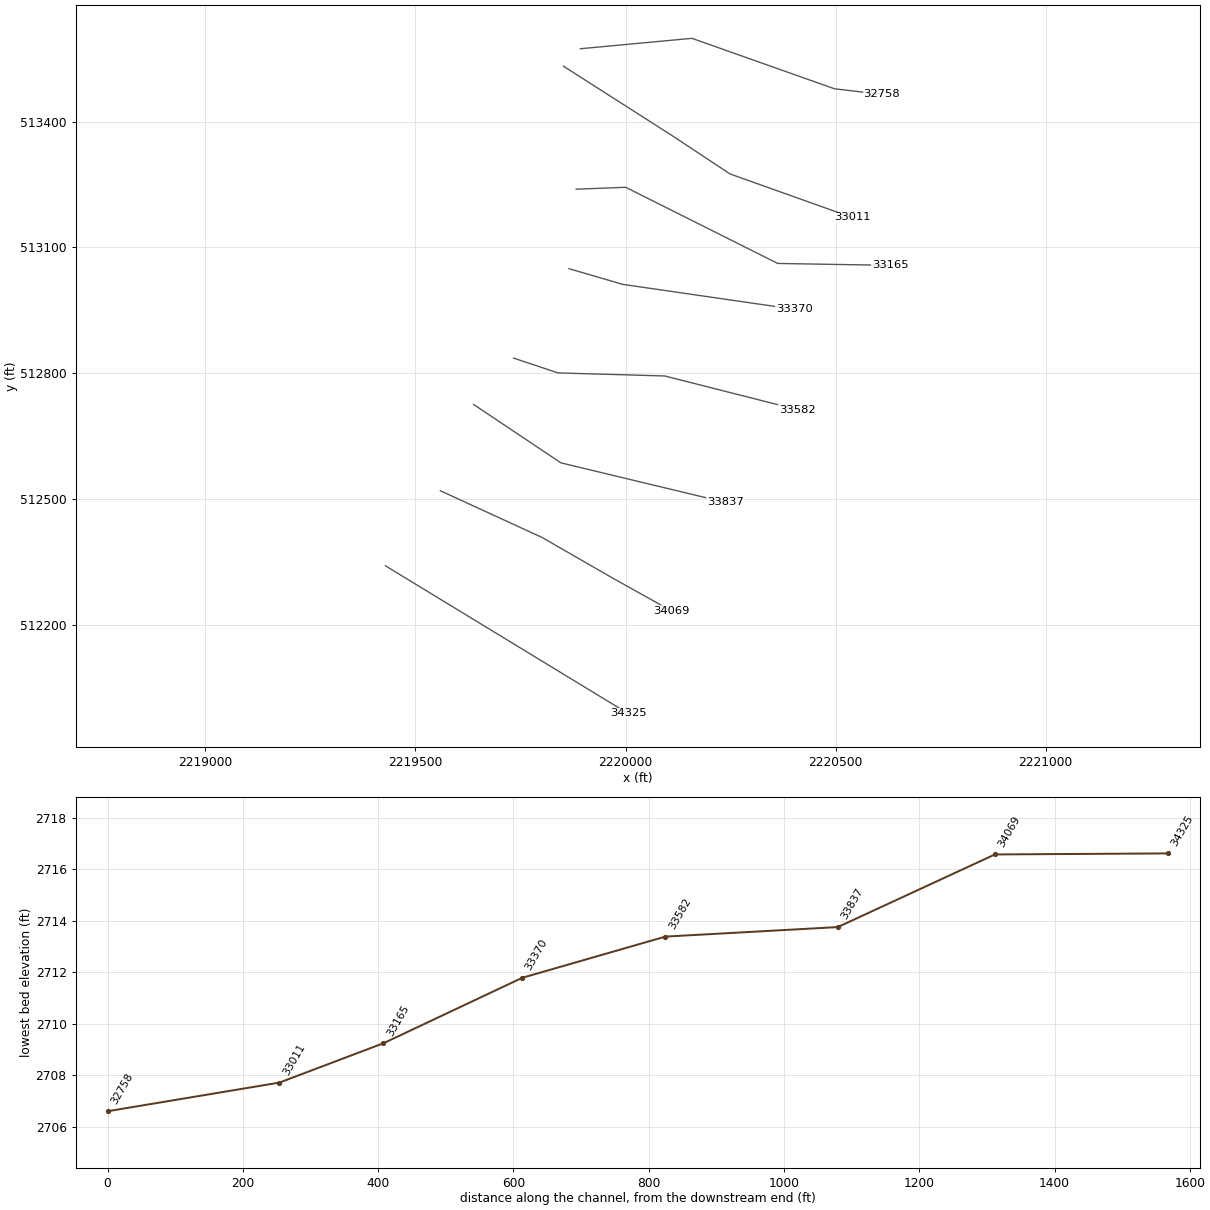
HEC-RAS study OLDFLDFK1.prj: OLDFLDFK1

--- OLDFLDFK1.g01 (geometry) --- (continued)

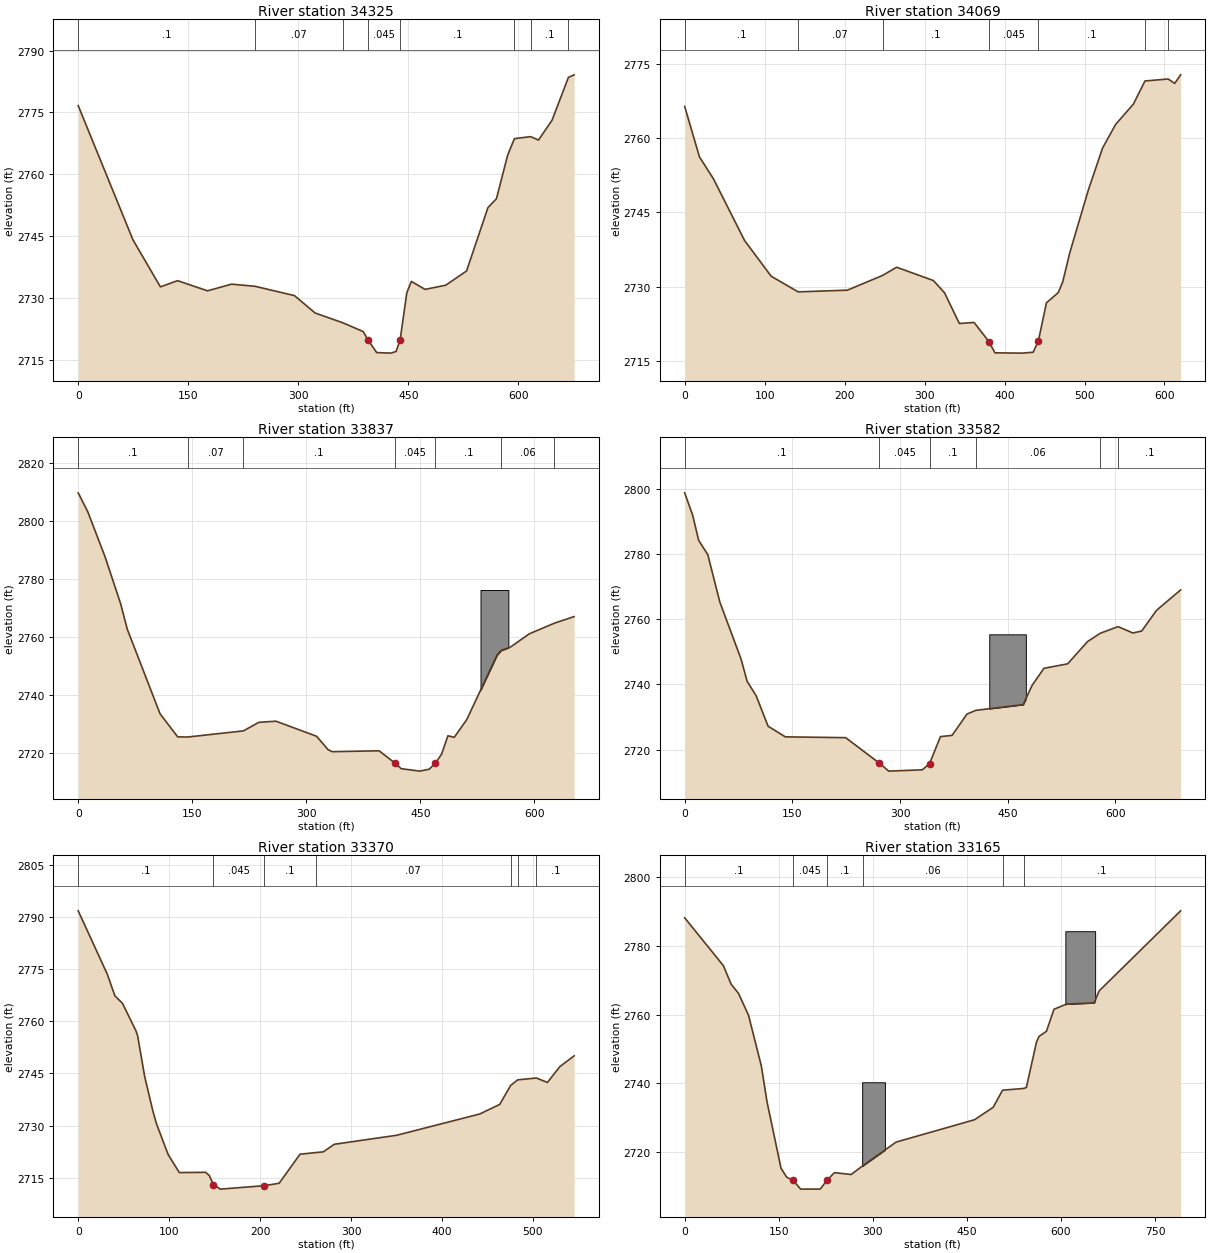
Type RM Length L Ch R = 1 ,34325   ,254.1,255.9,257.3
XS GIS Cut Line= 2
2219428.51233511512340.9028561942220005.61432314511989.114290271
#Sta/Elev= 30
       0 2776.64    74.6  2744.1     112 2732.69   135.5 2734.19   176.2 2731.73
   209.1 2733.35   241.1 2732.82   294.7 2730.57   322.8 2726.36   360.3    2724
   388.4 2721.85   395.4  2719.7   406.8 2716.75   425.9 2716.62   433.2 2717.01
  438.752719.838   447.8 2731.24     454 2734.02   472.7 2732.08   500.9 2733.09
   529.3 2736.55   558.4 2751.91     570 2754.06   585.2 2764.58   594.5 2768.63
   616.6 2769.12   627.3 2768.29   645.7 2773.07   668.1 2783.49   675.9 2784.11
#Mann= 8 ,-1,0
       0      .1       0   241.1     .07       0   360.3      .1       0
   395.4    .045       0  438.75      .1       0   594.5    .016       0
   616.6      .1       0   668.1    .016       0
Bank Sta=395.4,438.75
XS Rating Curve= 0 ,0
Exp/Cntr=0.3,0.1

Type RM Length L Ch R = 1 ,34069   ,208.9,232.3,242.9
XS GIS Cut Line= 4
2219559.36960048512519.7507445192219801.92653139512408.180314348
 2219971.7982284512310.1980867572220108.93628359 512233.59703639
#Sta/Elev= 30
       0 2766.35    18.5 2756.17    36.1 2751.71    74.9  2739.3   108.1 2732.11
   141.8 2728.94   203.4 2729.28   247.4 2732.25   265.1 2733.91   311.1 2731.22
     325 2728.74   343.5 2722.56   361.9 2722.77   380.4 2718.92     388 2716.64
     422 2716.58   435.8 2716.76   442.3 2719.03   452.4 2726.72   467.1 2728.78
   472.7 2730.91   481.8 2736.95   504.8 2749.48   522.6 2757.96     539 2762.74
   561.1 2766.81   575.6 2771.49   604.6 2771.89   612.8    2771   620.2 2772.73
#Mann= 7 ,-1,0
       0      .1       0   141.8     .07       0   247.4      .1       0
   380.4    .045       0   442.3      .1       0   575.6    .016       0
   604.6      .1       0
Bank Sta=380.4,442.3
XS Rating Curve= 0 ,0
Exp/Cntr(USF)=0,0
Exp/Cntr=0.3,0.1

Type RM Length L Ch R = 1 ,33837   ,237.8,254.9,261.4
XS GIS Cut Line= 3
2219638.76914646512725.3117665252219846.17110529512586.293086189
2220237.56541284512492.131557126
#Sta/Elev= 30
       0 2809.74    12.6 2803.19    35.4 2787.62    55.9  2771.4    64.5 2762.73
   107.6 2733.55   130.8 2725.58   143.9 2725.52   217.3 2727.64   237.6 2730.59
     260 2730.98   313.5 2725.78   328.5 2721.19     334 2720.47   395.7 2720.77
   416.3 2716.59   424.7 2714.61   449.2 2713.76   461.6 2714.42   469.8 2716.56
   477.8 2719.56   486.2 2725.96   494.5 2725.41     511 2731.54   550.7 2753.75
   556.2 2755.38   568.5 2756.55   593.2 2761.11   626.1 2764.77   652.2 2767.05
#Mann= 7 ,-1,0
       0      .1       0   143.9     .07       0   217.3      .1       0
   416.3    .045       0   469.8      .1       0   556.2     .06       0
   626.1    .016       0
#Block Obstruct= 1 ,-1
  529.03   565.7 2776.24
Bank Sta=416.3,469.8
XS Rating Curve= 0 ,0
Exp/Cntr=0.3,0.1

Type RM Length L Ch R = 1 ,33582   ,215.6,211.7,205.5
XS GIS Cut Line= 4
 2219733.6638078512835.9675249392219839.36424777 512800.70909815
2220093.40718271512793.3883359842220408.68203771512713.267389728
#Sta/Elev= 30
       0 2798.74    11.1  2791.9    19.5 2784.16    32.2 2779.78      49 2765.23
    78.5 2747.79      87 2740.94    99.6  2736.5   116.2 2727.17   140.2  2723.9
   224.3 2723.65   271.2 2715.84   284.3 2713.39   331.1 2713.79   341.2 2715.71
   356.3 2723.97   372.6 2724.36   393.2 2730.87   405.6 2732.03   471.6  2733.8
     484 2739.69   500.5 2744.92   533.5 2746.29   561.3 2753.13   578.9 2755.66
   603.7 2757.71   624.3 2755.76   636.7 2756.35   657.3  2762.7   690.9 2768.95
#Mann= 6 ,-1,0
       0      .1       0   271.2    .045       0   341.2      .1       0
   405.6     .06       0   578.9    .016       0   603.7      .1       0
#Block Obstruct= 1 ,-1
  424.31  475.27 2755.35
Bank Sta=271.2,341.2
XS Rating Curve= 0 ,0
Exp/Cntr(USF)=0,0
Exp/Cntr=0.3,0.1

Type RM Length L Ch R = 1 ,33370   ,218.5,205.1,188.8
XS GIS Cut Line= 3
2219865.45720161513049.1593977242219993.65301828 513011.72168135
2220401.22766224512952.584476254
#Sta/Elev= 30
       0 2791.72      32 2773.51    40.3 2767.33    48.7 2765.14    63.5 2757.25
    65.3 2755.88    73.1 2744.11      82 2734.34      86 2730.61    98.9 2721.73
   111.2 2716.54   140.1 2716.62   144.2 2715.69   148.6 2713.11   156.3 2711.79
   204.8 2712.78     221 2713.48   243.9 2721.81   261.2 2722.29   269.5 2722.49
   281.6 2724.67   350.3 2727.26   441.6 2733.37   463.5 2736.11   475.6 2741.59
   483.4 2743.18   503.9  2743.7     516 2742.43   529.8 2747.01   545.4 2750.08
#Mann= 7 ,-1,0
       0      .1       0   148.6    .045       0   204.8      .1       0
   261.2     .07       0   475.6     .06       0   483.4    .016       0
   503.9      .1       0
Bank Sta=148.6,204.8
XS Rating Curve= 0 ,0
Exp/Cntr=0.3,0.1

Type RM Length L Ch R = 1 ,33165   ,160.4,154.1,146.3
XS GIS Cut Line= 4
2219882.47434541513238.616932103 2220000.4598758513243.154837118
2220362.35780075513061.6386365162220630.09419664513057.100731501
#Sta/Elev= 30
       0 2788.16    61.7 2774.24      74 2768.88    85.8 2766.18   101.8 2759.82
   122.2 2745.09   131.3 2734.63   153.6 2715.33   162.5 2712.75     173 2711.78
   184.9 2709.25   216.2 2709.27   226.6 2711.76   238.7 2714.04   265.4  2713.5
   283.6    2716     337 2722.92   462.1 2729.43   491.9 2733.05   506.8 2738.02
   540.6 2738.53   544.8 2738.83   560.9    2752     565 2753.66   576.8 2755.16
   588.8 2761.56   608.8 2763.08   652.8 2763.42   660.8  2766.9   790.7 2790.19
#Mann= 6 ,-1,0
       0      .1       0     173    .045       0   226.6      .1       0
   283.6     .06       0   506.8    .016       0   540.6      .1       0
#Block Obstruct= 2 ,-1
  282.98  319.24 2740.33  606.94  654.41 2784.26
Bank Sta=173,226.6
XS Rating Curve= 0 ,0
Exp/Cntr(USF)=0,0
Exp/Cntr=0.3,0.1

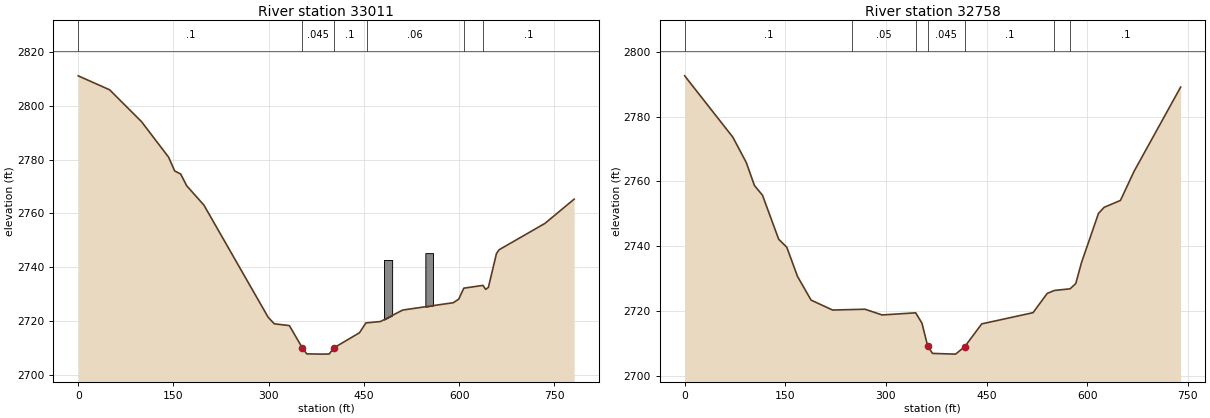
Type RM Length L Ch R = 1 ,33011   ,247.1,253.7,263.6
XS GIS Cut Line= 4
2219852.23747796513531.8452057262220108.43139568513367.978254423
2220248.91017538513274.9201722232220539.45473084513171.191936938
#Sta/Elev= 30
       0 2811.17    49.5 2805.97    99.6 2794.17   142.4 2780.92   151.9 2775.82
   161.4 2774.67   170.9 2770.29     198 2763.11   299.1 2721.45   308.8    2719
   332.6 2718.32   353.1    2710   359.9 2707.81   385.4 2707.72   395.4 2707.77
  402.33    2710     443 2715.67   453.1 2719.32   476.1 2719.84     511  2724.1
   590.8 2726.84   599.3 2728.16   607.3 2732.24   637.5 2733.27   641.7 2731.79
     646 2732.52   658.7 2745.07     663 2746.53   735.2 2756.33   781.1 2765.33
#Mann= 6 ,-1,0
       0      .1       0   353.1    .045       0  402.33      .1       0
  454.12     .06       0   607.3    .016       0   637.5      .1       0
#Block Obstruct= 2 ,-1
  481.58  494.42 2742.72  546.74  558.87 2745.26
Bank Sta=353.1,402.33
XS Rating Curve= 0 ,0
Exp/Cntr(USF)=0,0
Exp/Cntr=0.3,0.1

Type RM Length L Ch R = 1 ,32758   ,213.7,219.4,229.3
XS GIS Cut Line= 4
2219892.63600399513573.4668535352220158.15207508513598.245904546
2220497.36047495513477.9914216472220609.19590103513464.877102959
#Sta/Elev= 30
       0 2792.64    71.8 2773.67    91.9 2765.81     104 2758.73     116 2755.73
   140.1 2742.13   152.2 2739.66   168.2 2730.62   188.4 2723.31   220.5 2720.24
   268.8 2720.49   294.3 2718.72   344.3 2719.38   353.7 2716.16   362.2 2709.12
   369.4 2706.83   403.8 2706.61   417.4 2708.92   442.8 2715.96   519.2 2719.42
   540.4 2725.39   551.1 2726.29   574.4  2726.8   582.9 2728.41   591.4 2734.87
   616.8 2750.12   625.3 2752.01   649.5 2754.12   669.9 2763.15   739.2 2789.15
#Mann= 7 ,-1,0
       0      .1       0     250     .05       0   344.3      .1       0
   362.2    .045       0   417.4      .1       0   551.1    .016       0
   574.4      .1       0
Bank Sta=362.2,417.4
XS Rating Curve= 0 ,0
Exp/Cntr=0.3,0.1