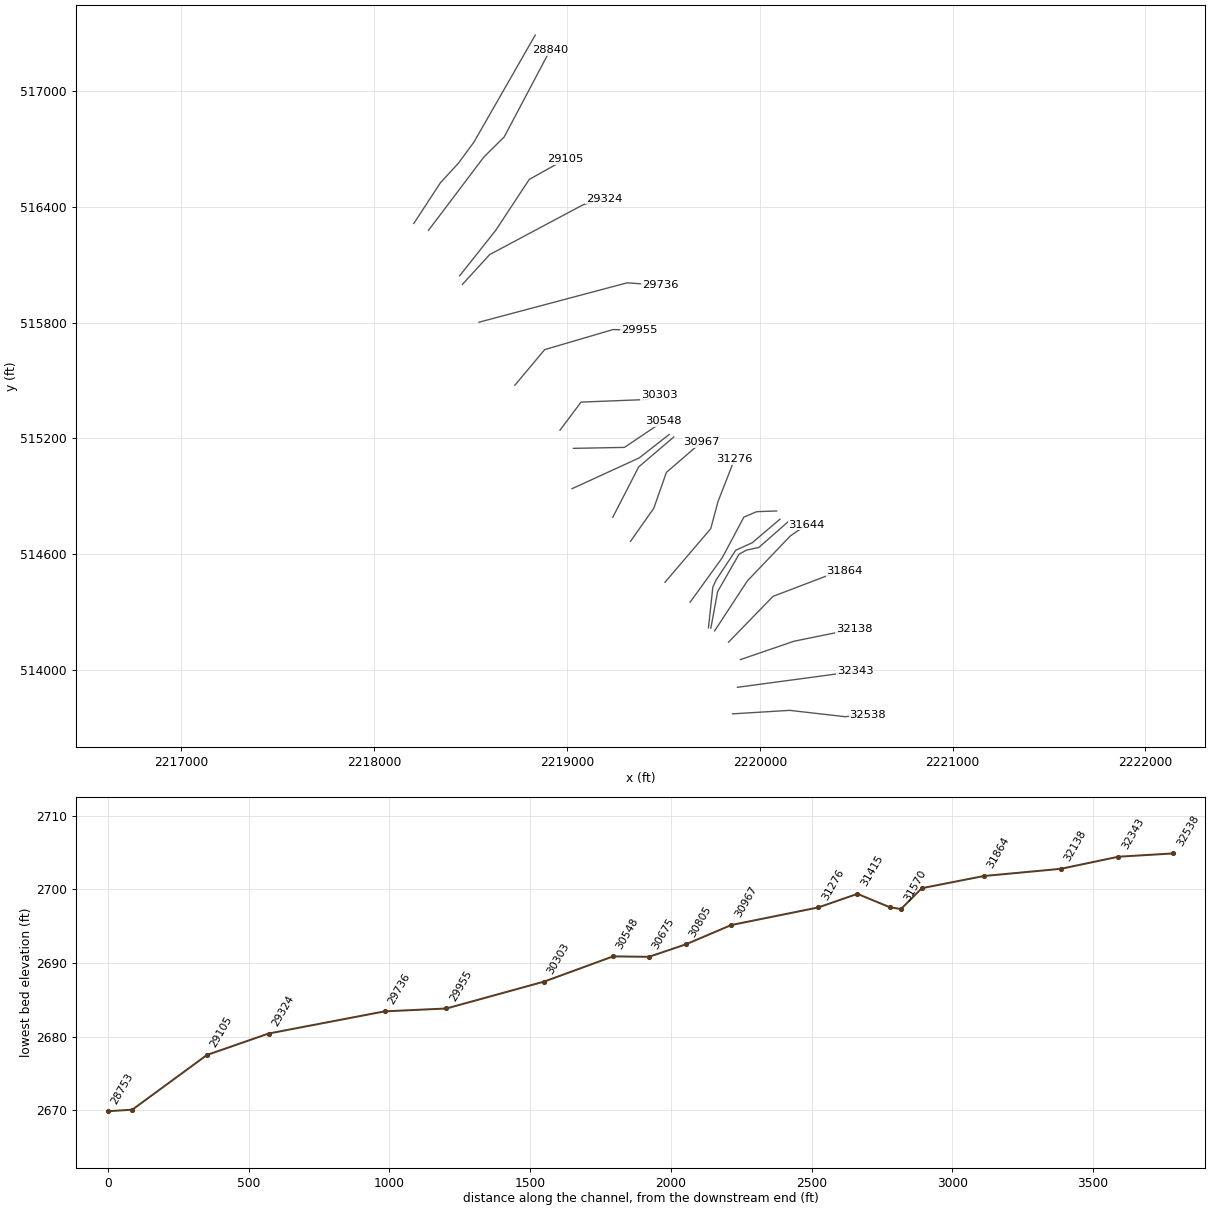
HEC-RAS study OLDFLDFK1.prj: OLDFLDFK1

--- OLDFLDFK1.g01 (geometry) --- (continued)

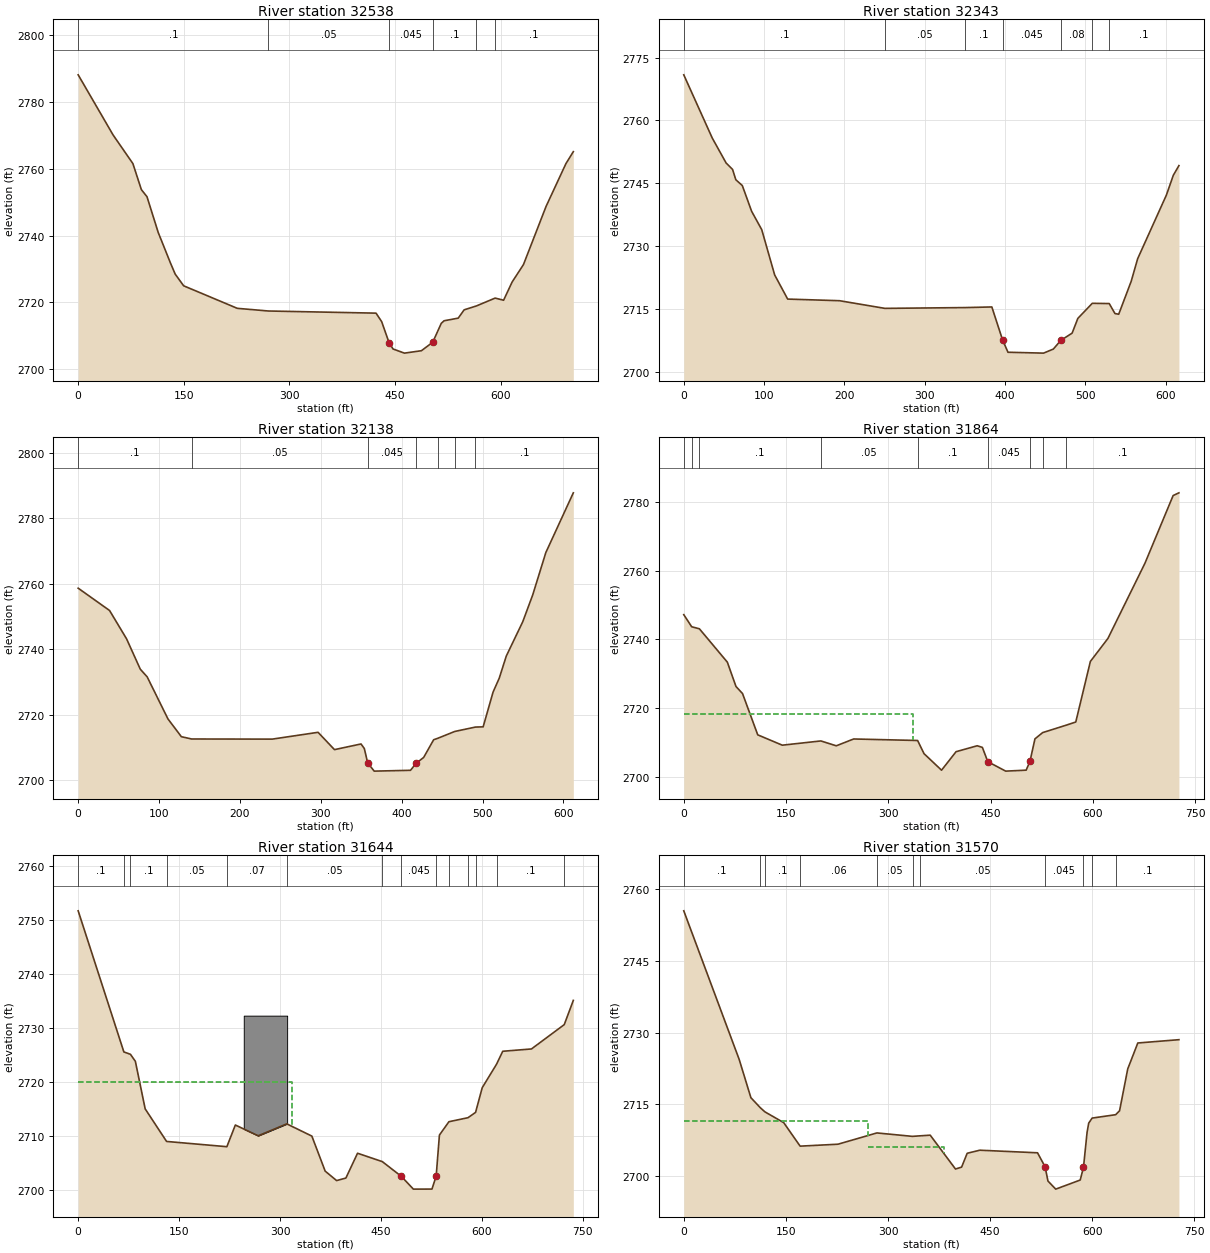
Type RM Length L Ch R = 1 ,32538   ,189.7,195.6,207.9
XS GIS Cut Line= 4
2219858.65034408513771.8207713712220154.74864632513789.972391432
2220442.90561477513757.0725800732220558.62219266 513768.41734261
#Sta/Elev= 30
       0 2788.04    49.6 2770.06    77.7 2761.51    89.7 2753.74    97.7 2751.61
   113.7 2740.89   131.1 2731.76   137.8 2728.46   149.8 2724.98   225.9 2718.25
     270 2717.45   422.9 2716.81   430.9 2714.27  441.33 2708.02   447.1 2706.09
   463.2 2704.86   487.3 2705.58   503.4 2708.11   515.5 2713.76   519.5 2714.53
   539.6 2715.32     548  2717.8   565.5 2718.97     592 2721.31     604 2720.67
   616.1 2726.11   632.2 2731.32   664.3 2748.71   692.5  2761.5     703 2765.08
#Mann= 6 ,-1,0
       0      .1       0     270     .05       0  441.33    .045       0
   503.4      .1       0   565.5    .016       0     592      .1       0
Bank Sta=441.33,503.4
XS Rating Curve= 0 ,0
Exp/Cntr(USF)=0,0
Exp/Cntr=0.3,0.1

Type RM Length L Ch R = 1 ,32343   ,202,204.3,207.8
XS GIS Cut Line= 2
2219883.95915411513909.457253724 2220495.1420504513991.808910744
#Sta/Elev= 30
       0 2770.89    35.5 2755.78    52.7 2749.84    60.8 2748.28    64.8 2745.83
    72.9 2744.44    84.5 2738.29    97.1 2733.91   113.2 2723.09   129.4 2717.32
     194 2716.93   250.5  2715.1   350.4 2715.29   383.7 2715.44   397.1 2707.53
   403.8 2704.62   448.1 2704.41   460.3 2705.38   469.5 2707.44   483.7 2709.19
   490.8 2712.71   508.8 2716.31   529.9 2716.25     537 2713.87   541.7  2713.7
   557.2 2721.54   565.3 2726.96   601.1 2742.17   609.7 2746.89   616.7 2749.21
#Mann= 7 ,-1,0
       0      .1       0   250.5     .05       0   350.4      .1       0
   397.1    .045       0   469.5     .08       0   508.8    .016       0
   529.9      .1       0
Bank Sta=397.1,469.5
XS Rating Curve= 0 ,0
Exp/Cntr(USF)=0,0
Exp/Cntr=0.3,0.1

Type RM Length L Ch R = 1 ,32138   ,268.4,273.9,279.3
XS GIS Cut Line= 3
2219899.49148922514053.1708823052220177.43817139514148.466887621
2220489.41914118514211.997557832
#Sta/Elev= 30
       0 2758.62    38.8 2751.81    59.9 2743.13    76.8 2733.89    85.3 2731.55
     111 2718.71   127.6 2713.28   140.3 2712.58   239.9 2712.54   296.6 2714.62
   316.9 2709.33   349.7 2711.06   353.8 2709.67   357.9 2705.31     366 2702.77
   410.9 2703.02   417.7 2705.12   427.2 2706.96   439.5 2712.35   445.1 2712.84
   465.6 2714.88   491.2 2716.22   500.7 2716.29     513 2726.91   520.6 2731.14
   529.3 2737.89   549.7 2748.39     562 2756.57   578.2 2769.49   612.2 2787.73
#Mann= 7 ,-1,0
       0      .1       0   140.3     .05       0   357.9    .045       0
   417.7     .05       0   445.1     .06       0   465.6    .016       0
   491.2      .1       0
Bank Sta=357.9,417.7
XS Rating Curve= 0 ,0
Exp/Cntr(USF)=0,0
Exp/Cntr=0.3,0.1

Type RM Length L Ch R = 1 ,31864   ,203.9,220,234
XS GIS Cut Line= 4
2219837.67886018514143.3249946842220068.52845103514381.034519642
2220360.08884825514492.2131925112220440.40946695514512.815897041
#Sta/Elev= 30
       0  2747.2    11.6 2743.69    22.9  2743.1    63.9 2733.42    76.6 2726.35
    86.2  2724.3   108.5 2712.32   144.5 2709.32   201.1 2710.55   223.7 2709.14
   249.2 2711.12     343 2710.68   352.4 2706.86   378.1 2702.06   399.4 2707.43
   430.4 2709.15     438 2708.68   445.9 2704.54   472.2 2701.79   502.2 2702.07
   507.8 2704.63   515.1 2711.15   526.4 2712.97   560.5  2715.1     575 2716.05
   596.4 2733.62   622.1 2740.28   676.5 2762.14   717.8 2781.77   726.3 2782.56
#Mann= 9 ,-1,0
       0      .1       0    11.6    .016       0    22.9      .1       0
   201.1     .05       0     343      .1       0   445.9    .045       0
   507.8     .06       0   526.4    .016       0   560.5      .1       0
#XS Ineff= 2 , 0
          336.68 2718.34
Permanent Ineff=
       F       F
Bank Sta=445.9,507.8
XS Rating Curve= 0 ,0
Exp/Cntr=0.3,0.1

Type RM Length L Ch R = 1 ,31644   ,128.9,74.2,71.5
BEGIN DESCRIPTION:
xs 4
END DESCRIPTION:
XS GIS Cut Line= 4
2219765.62329127514201.7872715482219935.79472934514461.582333659
2220158.15207508514694.1499656812220243.23779411514753.142730877
#Sta/Elev= 30
       0 2751.62    67.9 2725.52    77.7 2725.08      85 2723.78    99.6 2714.98
   131.4 2708.96     221 2707.99   233.6    2712   267.5 2710.01   310.1 2712.21
   347.3 2709.95   367.1 2703.47   384.1 2701.72   397.9 2702.19   415.2 2706.78
     452 2705.23   480.3  2702.5   498.2 2700.14   525.8 2700.15  532.052702.534
   536.9 2710.14     551 2712.61   579.3 2713.35   590.6 2714.33   600.5  2718.9
   621.8 2723.25     631 2725.64   673.7 2726.07   722.4 2730.57   735.9 2735.05
#Mann= 14 ,-1,0
       0      .1       0    67.9    .016       0    77.7      .1       0
   131.4     .05       0     221     .07       0   310.1     .05       0
     452      .1       0   480.3    .045       0  532.05     .07       0
     551    .016       0   579.3      .1       0   590.6     .08       0
   621.8      .1       0   722.4     .05       0
#XS Ineff= 2 , 0
          318.07  2719.9
Permanent Ineff=
       F       F
#Block Obstruct= 1 ,-1
  246.09  310.57 2732.23
Bank Sta=480.3,532.05
XS Rating Curve= 0 ,0
Exp/Cntr(USF)=0,0
Exp/Cntr=0.5,0.3

Type RM Length L Ch R = 1 ,31570   ,27.1,40.5,39.8
BEGIN DESCRIPTION:
xs 3
channel burned per srveyed cross section data
END DESCRIPTION:
XS GIS Cut Line= 6
2219746.33719496514216.5354628472219781.50595883514405.992997225
 2219892.6846317514599.9884366192219932.39130058 514621.54348544
2219994.57534748514634.4254633022220145.67283629514766.756445922
#Sta/Elev= 30
       0 2755.45    81.4  2724.4    98.6 2716.41   112.4 2714.32   119.2 2713.45
   146.8  2711.2   170.9 2706.29   226.4 2706.69   283.7 2709.05     336 2708.33
   346.7 2708.44     362 2708.58   399.1 2701.51   408.1 2701.91   416.3  2704.8
   434.8 2705.44   519.6  2704.9   530.7 2701.98  534.93    2699  546.34 2697.31
  582.31 2699.21   587.1 2701.87   592.4 2709.19   594.8  2711.1   599.8 2712.15
   634.4 2712.86   640.1 2713.68   652.1 2722.42   666.9 2727.84   727.3 2728.53
#Mann= 11 ,-1,0
       0      .1       0   112.4    .016       0   119.2      .1       0
   170.9     .06       0   283.7     .05       0     336    .016       0
   346.7     .05       0   530.7    .045       0   587.1     .07       0
   599.8    .016       0   634.4      .1       0
#XS Ineff= 4 ,-1
       0  270.42 2711.64  270.42     382 2706.07     420  520.15 2704.38
  597.53     700 2711.64
Permanent Ineff=
       F       F       F       F
Bank Sta=530.7,587.1
XS Rating Curve= 0 ,0
Exp/Cntr(USF)=0,0
Exp/Cntr=0.5,0.3

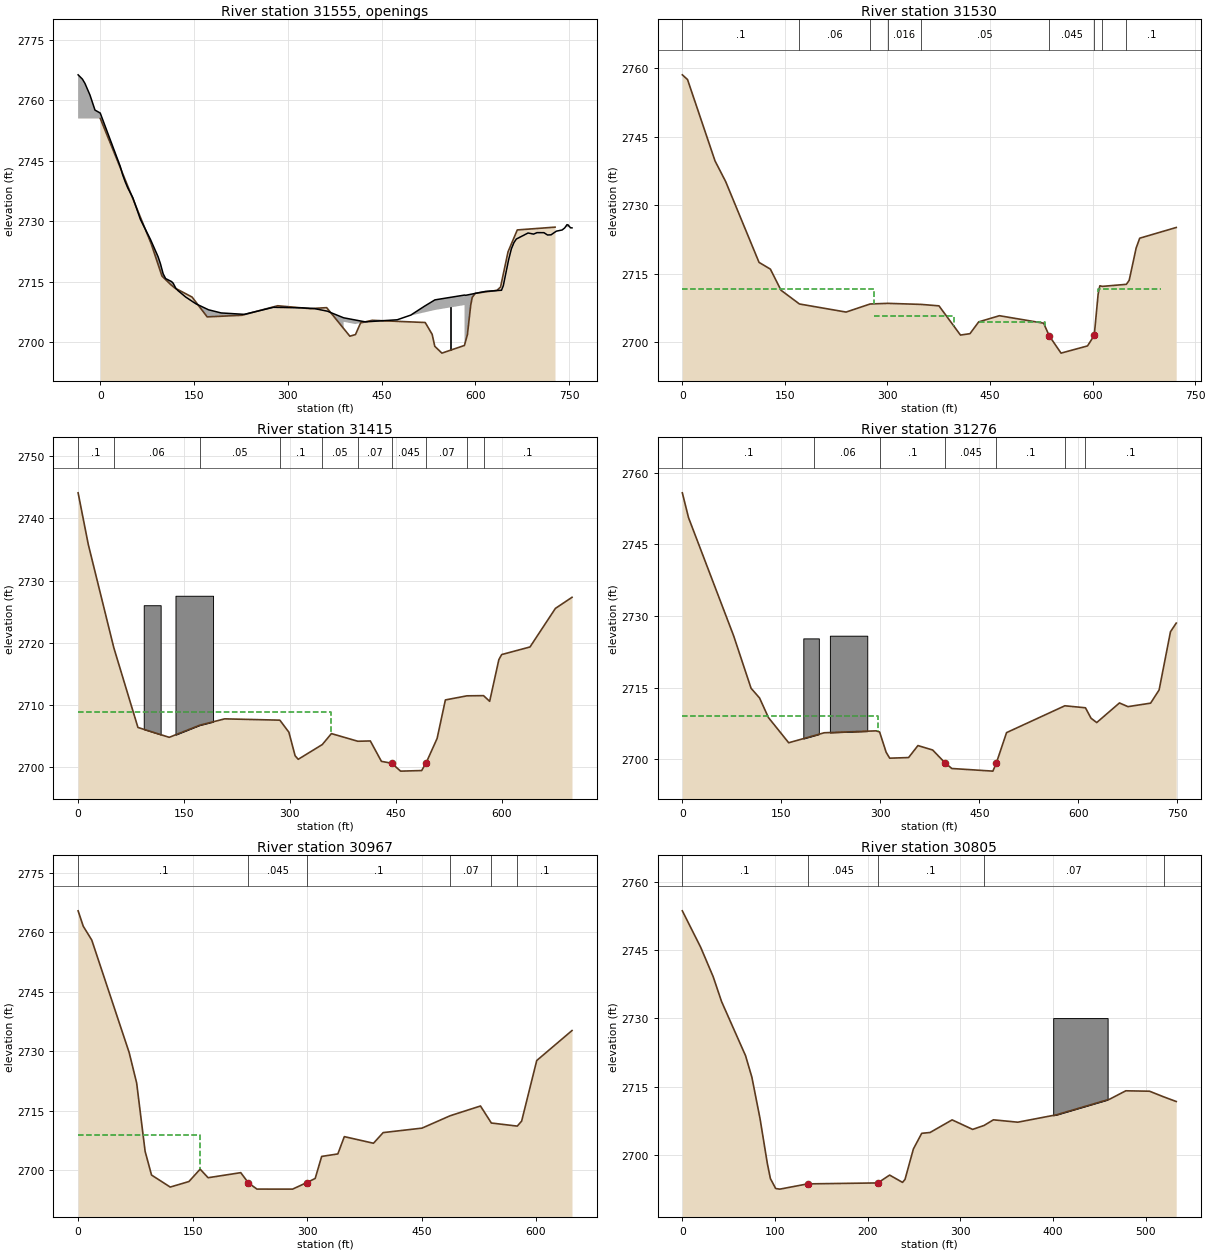
Type RM Length L Ch R = 4 ,31555   ,,,
BEGIN DESCRIPTION:
Bridge No.: 54075OLD020
JV notes: road deck updated based on surveyed data
pier coefficient and coefficient of drag updated per photos that show square nose pier
secondary opening apparent in imagery - no survey data provided for this opening, deck thickness of 1' assumed
main channel burned per surveyed cross section data
END DESCRIPTION:
Bridge Culvert--1,0,-1,-1, 0
Deck Dist Width WeirC Skew NumUp NumDn MinLoCord MaxHiCord MaxSubmerge Is_Ogee
12,14,2.6,0, 60, 60, , , 0.98, 0, 0,0,,
   -35.5 -28.649 -24.614 -16.545  -8.476   -.126  31.761  35.905   39.94  43.975
  52.044  64.148  80.286   92.39  96.117 100.459 104.494  113.94 116.598 121.069
 124.383 136.771  152.91 173.077 193.215 230.326 276.899 322.856 342.546 363.036
  386.72 389.122 423.998  424.78 474.903   496.5  518.15  535.15  582.53  584.23
 616.058 641.632 644.473 652.982 657.359  661.47 665.379 684.104 692.979 698.499
 709.539 715.227 720.886 729.374 738.621 742.659 746.349 748.179 752.008 754.391
2766.279 2765.222764.1722761.2742757.5342756.8122743.6392741.4452739.7142738.236
2735.825 2730.442725.4592721.2092719.4932716.9922715.7812715.0392714.6222713.287
2712.7852711.1872709.5332708.0532707.2712706.9192708.6662708.5312708.3442707.707
2706.2182706.0672705.0462705.0652705.578 2706.73 2708.91 2710.51  2711.7 2711.64
 2712.612712.8942714.0032720.4422723.1222724.6842725.586 2727.082726.8072727.172
2727.1592726.583 2726.632727.535 2727.832728.3272729.1442729.074 2728.362728.354
                                                                                
                                                                                
                                                                                
        2705.0672704.046                                    2708 2709.22
                                                                                
                                                                                
   -24.7 -17.849 -13.814  -5.745   2.324  10.674  42.561  46.705   50.74  54.775
  62.844  74.948  91.086  103.19 106.917 111.259 115.294  124.74 127.398 131.869
 135.183 147.571  163.71 183.877 204.015 241.126 287.699 333.656 353.346 373.836
  397.52 399.922 434.798  435.58 485.703   507.3  528.95  545.95  593.33  595.03
 626.858 652.432 655.273 663.782 668.159  672.27 676.179 694.904 703.779 709.299
 720.339 726.027 731.686 740.174 749.421 753.459 757.149 758.979 762.808 765.191
2766.279 2765.222764.1722761.2742757.5342756.8122743.6392741.4452739.7142738.236
2735.825 2730.442725.4592721.2092719.4932716.9922715.7812715.0392714.6222713.287
2712.7852711.1872709.5332708.0532707.2712706.9192708.6662708.5312708.3442707.707
2706.2182706.0672705.0462705.0652705.578 2706.73 2708.91 2710.51  2711.7 2711.64
 2712.612712.8942714.0032720.4422723.1222724.6842725.586 2727.082726.8072727.172
2727.1592726.583 2726.632727.535 2727.832728.3272729.1442729.074 2728.362728.354
                                                                                
                                                                                
                                                                                
        2705.0672704.046                                    2708 2709.22
                                                                                
                                                                                
Pier Skew, UpSta & Num, DnSta & Num=  ,560.08, 2 ,570.88, 2 , 0 , 0 , 0 ,,
       2       2
       0  2709.5
       2       2
       0  2709.5
BR Coef=-1 ,-1 , 0 ,, 0 ,,,0.8,0,1.39,0,
WSPro=,,,, 1 ,,,, 0 ,,,, 0 ,,,,-1 ,-1 ,-1 , 0 , 0 , 0 , 0 , 0
BC Mult= 1 ,0,345,0,345
BC Mult= 3 ,345,475,345,480
BC Mult= 3 ,430,730,450,730
BR U #Sta/Elev= 30
       0 2755.45    81.4  2724.4    98.6 2716.41   112.4 2714.32   119.2 2713.45
   146.8  2711.2   170.9 2706.29   226.4 2706.69   283.7 2709.05     336 2708.33
   346.7 2708.44     362 2708.58   399.1 2701.51   408.1 2701.91   416.3  2704.8
   434.8 2705.44   519.6  2704.9   530.7 2701.98  534.93    2699  546.34 2697.31
  582.31 2699.21   587.1 2701.87   592.4 2709.19   594.8  2711.1   599.8 2712.15
   634.4 2712.86   640.1 2713.68   652.1 2722.42   666.9 2727.84   727.3 2728.53
BR U #Mann= 11
       0      .1   112.4    .016   119.2      .1   170.9     .06   283.7     .05
     336    .016   346.7     .05   530.7     .04   587.1     .07   599.8    .016
   634.4      .1
BR D #Sta/Elev= 30
       0 2758.57     7.6 2757.54    47.8 2739.71    63.4 2735.17   112.2 2717.46
   128.8 2715.98   144.3 2711.36   171.3 2708.34   239.5 2706.57   274.7 2708.34
   300.4 2708.48   349.3 2708.25   375.4 2707.93   406.8 2701.53   420.7 2701.83
   433.5 2704.42   463.8 2705.77   528.5 2704.13   536.6 2701.37  553.93 2697.57
  592.66 2699.15   602.5 2701.47   608.2 2710.53   610.7 2712.33   614.5  2712.2
   649.5 2712.65   653.6 2713.53   663.8 2720.62     669 2722.76   722.4 2725.11
BR D #Mann= 9
       0      .1   171.3     .06   274.7     .05   300.4    .016   349.3     .05
   536.6     .04   602.5     .06   614.5    .016   649.5      .1
BC Design=,, 0 ,, 0 ,,,,,,
BC Use User HTab Curves=0
BC User HTab FreeFlow(D)= 0

Type RM Length L Ch R = 1 ,31530   ,46,114.1,128
BEGIN DESCRIPTION:
xs 2
channel burned per srveyed cross section data
END DESCRIPTION:
XS GIS Cut Line= 6
2219733.85795617  514217.66993912219756.54748124  514428.6825223
2219773.56462505514466.1202386752219875.66748789514620.409009186
2219961.17750104514659.4054959332220104.83169115514781.504637221
#Sta/Elev= 30
       0 2758.57     7.6 2757.54    47.8 2739.71    63.4 2735.17   112.2 2717.46
   128.8 2715.98   144.3 2711.36   171.3 2708.34   239.5 2706.57   274.7 2708.34
   300.4 2708.48   349.3 2708.25   375.4 2707.93   406.8 2701.53   420.7 2701.83
   433.5 2704.42   463.8 2705.77   528.5 2704.13   536.6 2701.37  553.93 2697.57
  592.66 2699.15   602.5 2701.47   608.2 2710.53   610.7 2712.33   614.5  2712.2
   649.5 2712.65   653.6 2713.53   663.8 2720.62     669 2722.76   722.4 2725.11
#Mann= 9 ,-1,0
       0      .1       0   171.3     .06       0   274.7     .05       0
   300.4    .016       0   349.3     .05       0   536.6    .045       0
   602.5     .06       0   614.5    .016       0   649.5      .1       0
#XS Ineff= 4 ,-1
       0     280 2711.64     280     397  2705.6     434   530.6 2704.38
   608.7     700 2711.64
Permanent Ineff=
       F       F       F       F
Bank Sta=536.6,602.5
XS Rating Curve= 0 ,0
Exp/Cntr(USF)=0,0
Exp/Cntr=0.5,0.3

Type RM Length L Ch R = 1 ,31415   ,132.2,139,149.5
BEGIN DESCRIPTION:
xs 1
END DESCRIPTION:
XS GIS Cut Line= 5
2219638.58626984514350.6220663782219805.91648438514582.183966292
2219917.63894949514792.289730158 2219984.5556532514820.369524722
2220087.64011544514823.945998575
#Sta/Elev= 30
       0 2744.09    14.4  2735.8    50.5 2719.22    84.7 2706.39     129  2704.8
     172 2706.74   207.6 2707.77   285.7 2707.56   298.5 2705.62   307.3 2701.84
   311.7 2701.27   345.8 2703.64   358.7  2705.4   396.1 2704.17   413.8 2704.22
   429.5 2700.94   443.9 2700.64   456.7 2699.37   486.5 2699.46     493 2700.74
   508.4 2704.63   520.1 2710.81   550.7 2711.47   574.1  2711.5   582.8 2710.59
   595.8 2717.28   599.8  2718.1   639.9 2719.32   675.9 2725.52   699.4  2727.3
#Mann= 10 ,-1,0
       0      .1       0    50.5     .06       0     172     .05       0
   285.7      .1       0   345.8     .05       0   396.1     .07       0
   443.9    .045       0     493     .07       0   550.7    .016       0
   574.1      .1       0
#XS Ineff= 2 , 0
          358.08 2708.92
Permanent Ineff=
       F       F
#Block Obstruct= 2 ,-1
   92.93  116.87 2726.03  137.87   191.1 2727.55
Bank Sta=443.9,493
XS Rating Curve= 0 ,0
Exp/Cntr=0.3,0.1

Type RM Length L Ch R = 1 ,31276   ,308.5,309.3,305.8
XS GIS Cut Line= 4
2219508.18453634514453.9938219982219745.54306158  514731.8769735
2219783.58658828514873.2996488182219869.59803993 515093.29047709
#Sta/Elev= 30
       0 2755.79     9.4 2750.59    77.8 2725.83   104.1 2714.88     117 2712.84
   130.4 2708.75   161.1 2703.47     215 2705.56   293.5 2705.96   298.8 2705.73
   308.7 2701.49   314.1 2700.24   342.7 2700.37   356.9 2702.88   379.2 2701.95
     398 2699.25   408.2 2698.08   470.4 2697.53   475.6 2699.22   491.1 2705.59
   579.4 2711.21   610.6 2710.79   619.1  2708.6   627.7  2707.7   662.1  2711.8
     675 2711.03   709.3 2711.76   722.2 2714.53   739.4 2726.71   748.1 2728.52
#Mann= 7 ,-1,0
       0      .1       0     200     .06       0     300      .1       0
     398    .045       0   475.6      .1       0   579.4    .016       0
   610.6      .1       0
#XS Ineff= 2 , 0
          296.56 2709.08
Permanent Ineff=
       F       F
#Block Obstruct= 2 ,-1
  183.24  206.75 2725.32   223.5  280.11 2725.88
Bank Sta=398,475.6
XS Rating Curve= 0 ,0
Exp/Cntr(USF)=0,0
Exp/Cntr=0.3,0.1

Type RM Length L Ch R = 1 ,30967   ,164.5,162,154.7
XS GIS Cut Line= 4
2219329.54536752514666.5413515692219450.29221311514837.737221691
2219515.62783504515023.8196892152219697.57513662515180.955995123
#Sta/Elev= 30
       0 2765.44     6.7 2761.56    17.9 2758.05    66.9 2729.63    76.7 2721.96
    87.8 2704.68    96.2  2698.7   120.7 2695.66   145.2 2697.06   159.9 2700.18
   170.3 2698.02   213.1  2699.3   223.1 2696.72   234.3 2695.15     281 2695.14
   299.7  2696.8   310.6 2697.83   319.1  2703.4   340.3 2704.03   348.8  2708.4
     387 2706.73   399.7 2709.42   450.6 2710.55   487.5 2713.68   527.2 2716.14
   541.4 2711.84   575.4 2711.06   581.1 2712.32   600.9 2727.63   647.1  2735.2
#Mann= 6 ,-1,0
       0      .1       0   223.1    .045       0   299.7      .1       0
   487.5     .07       0   541.4    .016       0   575.4      .1       0
#XS Ineff= 2 , 0
          159.72 2708.89
Permanent Ineff=
       F       F
Bank Sta=223.1,299.7
XS Rating Curve= 0 ,0
Exp/Cntr(USF)=0,0
Exp/Cntr=0.3,0.1

Type RM Length L Ch R = 1 ,30805   ,156.1,130.3,85.8
XS GIS Cut Line= 3
2219237.85082596514791.604730884 2219371.9471222515052.206966967
2219554.11567558515207.809272978
#Sta/Elev= 30
       0 2753.59    19.8 2745.59    33.3 2739.12    42.3 2733.69    68.2 2721.79
      75 2717.09    83.8    2708    91.7 2698.13      95 2694.82   100.7 2692.64
   105.2 2692.51  135.07 2693.66   210.8 2693.87   223.6 2695.59   237.5 2693.99
   240.2 2694.65   249.2 2701.32   258.2 2704.76   267.2 2704.94     291 2707.71
   313.1 2705.62   325.4 2706.48   335.5 2707.72   361.8  2707.2   403.9 2708.84
   460.9 2712.25   478.3 2714.09   503.9    2714   519.6 2712.73   532.7 2711.74
#Mann= 5 ,-1,0
       0      .1       0  135.07    .045       0   210.8      .1       0
   325.4     .07       0   519.6    .016       0
#Block Obstruct= 1 ,-1
     400   458.7 2730.05
Bank Sta=135.07,210.8
XS Rating Curve= 0 ,0
Exp/Cntr(USF)=0,0
Exp/Cntr=0.3,0.1

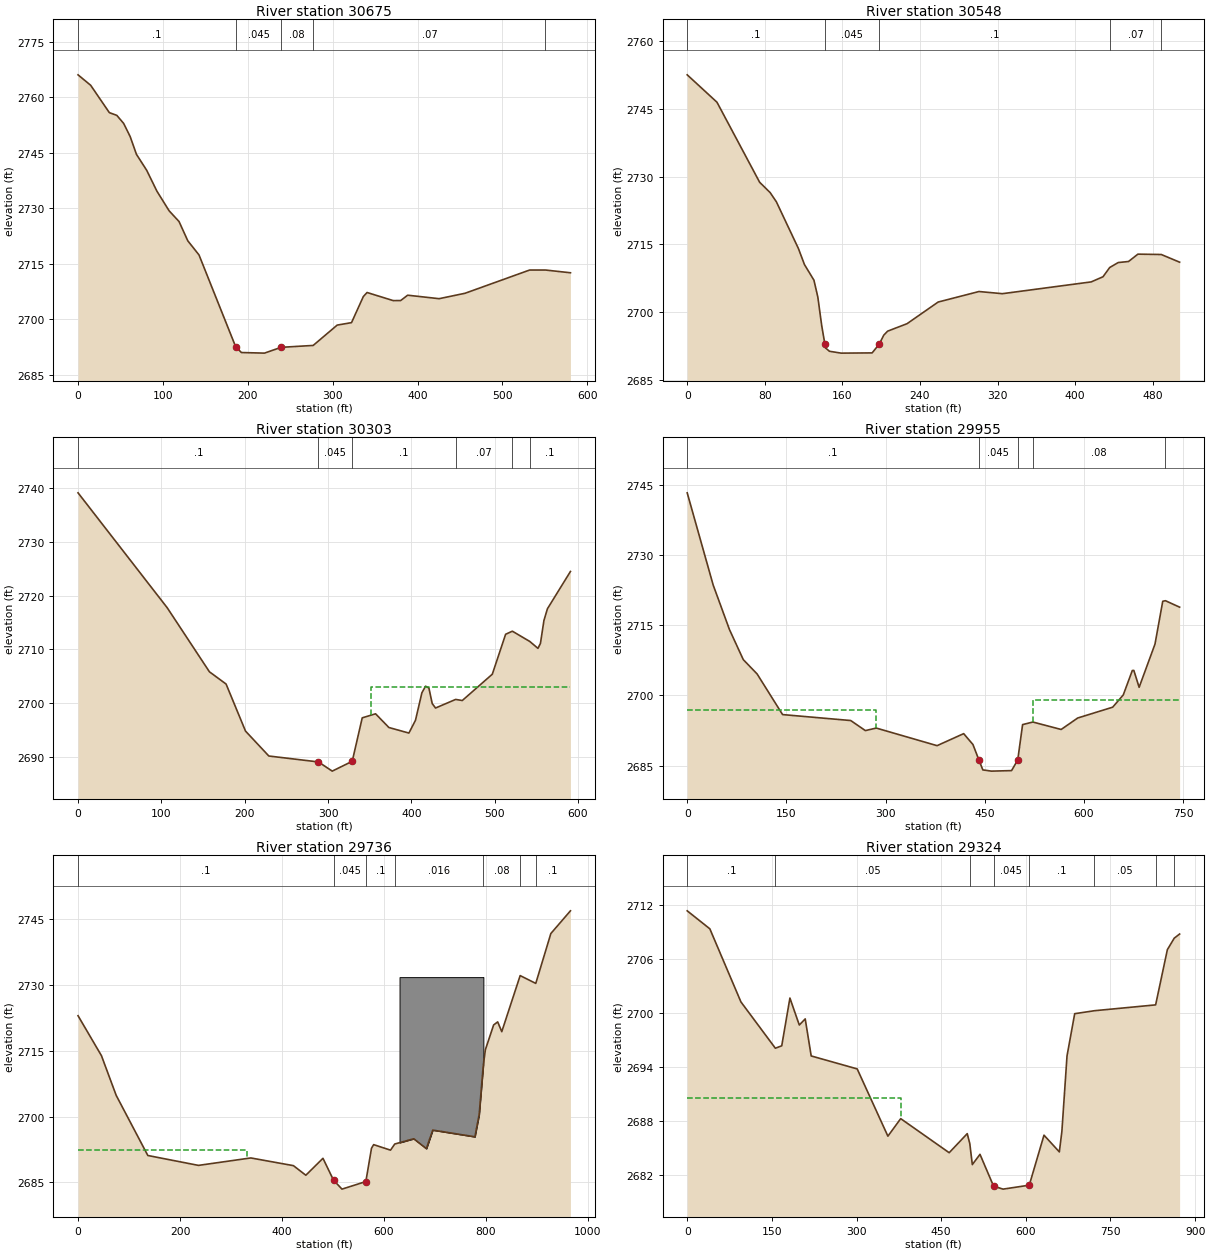
Type RM Length L Ch R = 1 ,30675   ,140.2,127.3,106.3
XS GIS Cut Line= 3
2219026.58590642514939.616680504  2219374.477241 515099.01416471
2219530.07954701515220.459866963
#Sta/Elev= 30
       0 2766.12    14.9 2763.29    36.9 2755.89    45.7 2755.15    53.7 2752.99
    61.4 2749.43    68.8 2744.62    80.9 2740.29    92.9 2734.66   107.3 2729.34
     119 2726.43   129.3 2721.22   142.5  2717.4  185.85 2692.48   192.5 2690.99
   219.6 2690.83   239.3  2692.4     277 2692.91   305.3 2698.41   322.2 2699.08
   336.1 2706.13   340.5 2707.23   371.3 2705.04   380.1 2705.05   388.3  2706.5
   425.4 2705.56   455.9 2707.02     532 2713.31   550.7 2713.31   580.1 2712.57
#Mann= 5 ,-1,0
       0      .1       0  185.85    .045       0   239.3     .08       0
     277     .07       0   550.7    .016       0
Bank Sta=185.85,239.3
XS Rating Curve= 0 ,0
Exp/Cntr(USF)=0,0
Exp/Cntr=0.3,0.1

Type RM Length L Ch R = 1 ,30548   ,243.3,244.9,242.5
XS GIS Cut Line= 3
2219033.46748586515148.7017007532219298.11810634515153.663899887
2219499.91420445515289.297342882
#Sta/Elev= 30
       0 2752.55    30.7 2746.48    74.7 2728.75    85.6 2726.44      92  2724.4
   114.7 2714.06   120.9 2710.52   130.7 2707.05   134.7 2703.32   138.7    2697
  141.97 2692.88   142.7 2692.03   146.7  2691.3   158.7 2690.89   190.7 2690.94
     198 2692.87   202.7 2694.87   206.7 2695.76   226.7 2697.41   258.8 2702.21
   300.9 2704.54     325 2704.06   416.6 2706.67   428.8 2707.81   435.7 2709.86
   444.5 2710.96   455.1 2711.19   464.8 2712.82   488.9 2712.74   507.8 2711.04
#Mann= 5 ,-1,0
       0      .1       0  141.97    .045       0     198      .1       0
   435.7     .07       0   488.9    .016       0
Bank Sta=141.97,198
XS Rating Curve= 0 ,0
Exp/Cntr(USF)=0,0
Exp/Cntr=0.3,0.1

Type RM Length L Ch R = 1 ,30303   ,329.9,347.3,351.8
XS GIS Cut Line= 4
2218963.99669798515242.9834842982219073.16507893515388.541325561
2219409.76758685515401.7738565852219478.41134154515424.103752688
#Sta/Elev= 30
       0 2739.02     107 2717.74   157.7 2705.87   177.7  2703.6     201 2694.89
     229 2690.27   288.6 2689.17   305.1 2687.47   329.1 2689.29   341.1 2697.34
   357.1 2698.09   373.1 2695.55   397.1 2694.52     405 2696.88   412.7 2701.98
   417.1  2703.2   421.1 2702.88   425.1 2699.98   429.1 2699.16   453.2 2700.75
   461.2 2700.55   497.2 2705.42   513.2 2712.82   521.3 2713.39   542.2 2711.49
     552 2710.21     555 2711.13   559.2 2715.39   563.4 2717.55     591 2724.45
#Mann= 6 ,-1,0
       0      .1       0   288.6    .045       0   329.1      .1       0
   453.2     .07       0   521.3    .016       0   542.2      .1       0
#XS Ineff= 2 , 0
                          351.89         2703.07
Permanent Ineff=
       F       F
Bank Sta=288.6,329.1
XS Rating Curve= 0 ,0
Exp/Cntr(USF)=0,0
Exp/Cntr=0.3,0.1

Type RM Length L Ch R = 1 ,29955   ,220.6,219.6,219.3
XS GIS Cut Line= 4
 2218729.9463055515476.2068435942218884.60151184 515660.63524474
2219239.39874992515764.8414265532219373.37812654515760.706260608
#Sta/Elev= 30
       0 2743.28    39.2 2723.61    63.9 2714.06    84.8 2707.64   105.7 2704.58
   144.2  2695.9   247.2 2694.63   269.4 2692.48   285.9 2693.02   377.8 2689.26
     418 2691.83     432 2689.51   441.3 2686.12     447 2684.08   459.9 2683.82
   490.4 2683.93  499.742686.203   507.1 2693.76   522.6 2694.31   565.4 2692.72
   590.4 2695.17   643.3 2697.48   659.3  2700.1     673 2705.32   675.3 2705.33
   683.3 2701.73   707.3 2710.97     719 2720.11   723.1 2720.23   744.5 2718.85
#Mann= 5 ,-1,0
       0      .1       0   441.3    .045       0  499.74      .1       0
   522.6     .08       0   723.1    .016       0
#XS Ineff= 2 , 0
          284.85  2696.8  523.27         2699.08
Permanent Ineff=
       F       F
Bank Sta=441.3,499.74
XS Rating Curve= 0 ,0
Exp/Cntr(USF)=0,0
Exp/Cntr=0.3,0.1

Type RM Length L Ch R = 1 ,29736   ,398.2,412.1,422.9
XS GIS Cut Line= 3
2218543.86383798515802.8849532472219312.17767055516007.162150928
2219482.54650748515994.756653093
#Sta/Elev= 30
       0 2723.03    45.9 2713.91    74.8 2704.85   136.9 2691.11   236.2 2688.85
   338.9 2690.55   422.5 2688.79   446.8  2686.6   480.4 2690.47   501.1 2685.48
   517.7 2683.43   564.5 2685.16   575.6 2692.76   579.8 2693.59   612.9 2692.33
   621.2 2693.73   658.4 2694.93   683.3 2692.67   695.7 2696.91   778.4 2695.38
   786.7 2700.39     795 2711.83     799 2715.28   815.1 2720.91   823.1 2721.62
   831.1 2719.38   867.2 2732.19   897.8 2730.41   927.4  2741.8   965.8 2746.98
#Mann= 7 ,-1,0
       0      .1       0   501.1    .045       0   564.5      .1       0
   621.2    .016       0     795     .08       0   867.2    .016       0
   897.8      .1       0
#XS Ineff= 2 , 0
          332.17 2692.42
Permanent Ineff=
       F       F
#Block Obstruct= 1 ,-1
  630.55  795.01 2731.84
Bank Sta=501.1,564.5
XS Rating Curve= 0 ,0
Exp/Cntr(USF)=0,0
Exp/Cntr=0.3,0.1

Type RM Length L Ch R = 1 ,29324   ,189,219,242.6
XS GIS Cut Line= 4
2218457.85238632515998.8918190382218599.27506164 516153.54702538
2219084.74354358516412.4084135352219193.08489134516443.835674717
#Sta/Elev= 30
       0 2711.37    40.1 2709.37    95.2 2701.24   156.2 2696.09   167.5 2696.36
     182 2701.67   198.6 2698.67   209.1 2699.35   219.7 2695.23   301.2 2693.79
   355.6 2686.31   378.3 2688.26   464.2 2684.47   496.2 2686.59   500.7 2685.49
   505.2 2683.15   518.8 2684.29   542.8 2680.76   559.6 2680.42   606.1 2680.86
   632.2 2686.42   659.4 2684.56   663.9 2686.85     673 2695.24   686.6 2699.93
   721.5 2700.26     830 2700.91   850.8 2707.05     863 2708.33   872.5 2708.79
#Mann= 8 ,-1,0
       0      .1       0   156.2     .05       0   500.7      .1       0
   542.8    .045       0   606.1      .1       0   721.5     .05       0
     830     .08       0     863    .016       0
#XS Ineff= 2 , 0
          378.59 2690.55
Permanent Ineff=
       F       F
Bank Sta=542.8,606.1
XS Rating Curve= 0 ,0
Exp/Cntr(USF)=0,0
Exp/Cntr=0.3,0.1

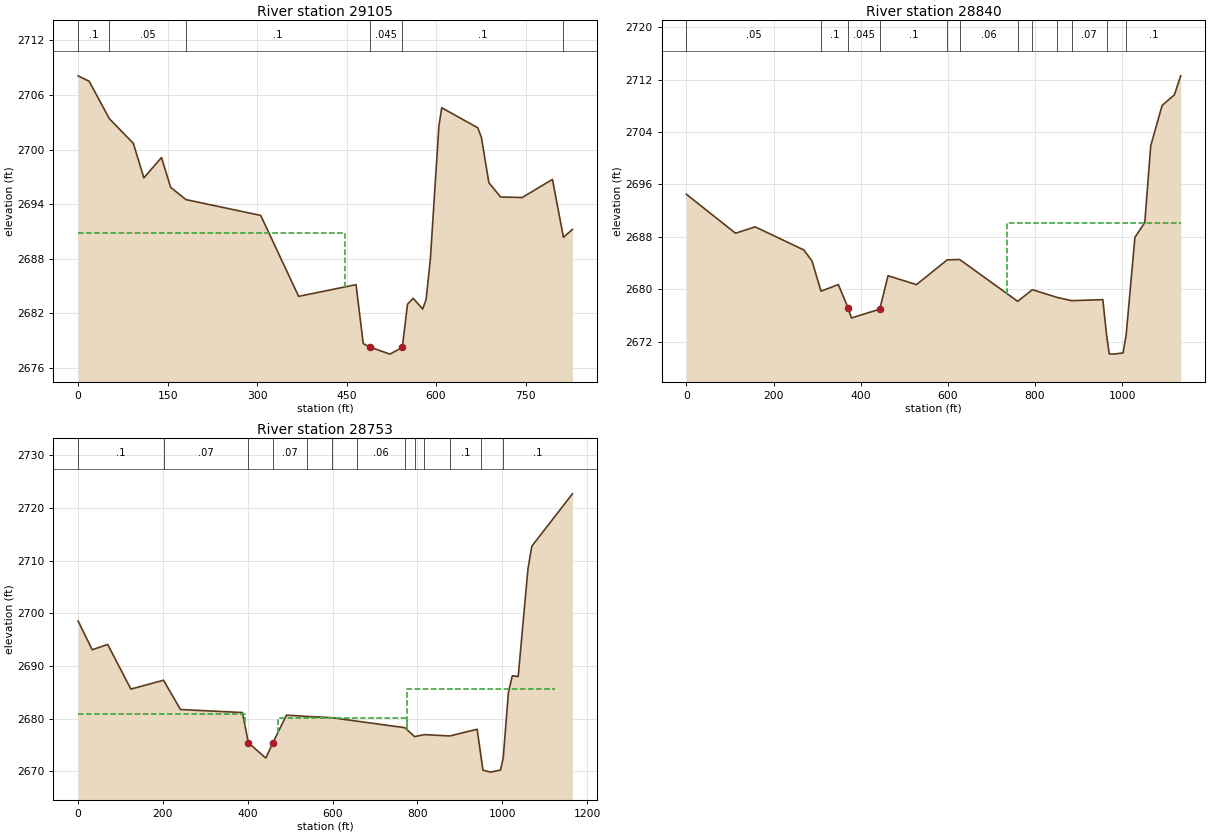
Type RM Length L Ch R = 1 ,29105   ,269.3,265.1,262.2
XS GIS Cut Line= 4
2218443.67486321 516043.664582312218630.79495776516279.482420886
2218804.62119877516543.3258224052218989.37095123516646.686989356
#Sta/Elev= 30
       0 2708.11    18.5 2707.51    52.3  2703.4    92.5 2700.69   110.2 2696.89
   139.8 2699.13   155.1 2695.85   180.8  2694.5   306.1 2692.76   369.7 2683.86
   465.9 2685.15     478 2678.66   489.9 2678.27   522.7 2677.51   543.5 2678.25
   552.2    2683   561.7 2683.65   577.6 2682.47   583.4 2683.52   590.5 2687.95
   604.8 2702.57   609.6  2704.6   669.9  2702.4   676.1 2701.34   688.6 2696.36
   708.2 2694.79   744.4 2694.73   795.2 2696.72   813.6 2690.36   828.7 2691.22
#Mann= 6 ,-1,0
       0      .1       0    52.3     .05       0   180.8      .1       0
   489.9    .045       0   543.5      .1       0   813.6    .016       0
#XS Ineff= 2 , 0
          447.32 2690.87
Permanent Ineff=
       F       F
Bank Sta=489.9,543.5
XS Rating Curve= 0 ,0
Exp/Cntr(USF)=0,0
Exp/Cntr=0.3,0.1

Type RM Length L Ch R = 1 ,28840   ,89.4,86.7,87.3
BEGIN DESCRIPTION:
xs 4
END DESCRIPTION:
XS GIS Cut Line= 4
2218281.92757044516279.2550172472218569.50999898516659.722567058
2218674.73924094516763.9607617892218912.87731688517214.006684845
#Sta/Elev= 30
       0  2694.5   112.7 2688.55   157.8 2689.52   269.1 2686.01   288.2 2684.32
   308.9  2679.7   348.7 2680.71   371.4 2677.08   378.5 2675.61   443.7 2676.95
   462.7 2682.06   527.9  2680.7   598.4 2684.48     627 2684.54   760.2 2678.15
   793.9 2679.93   850.5 2678.75     884 2678.25   955.5 2678.41   964.4 2672.86
   970.3 2670.13   979.2 2670.09    1002 2670.27    1009    2673  1029.2 2687.93
  1051.8 2690.18  1065.4 2701.89  1091.6 2708.06  1119.7 2709.68  1134.2 2712.58
#Mann= 12 ,-1,0
       0     .05       0   308.9      .1       0   371.4    .045       0
   443.7      .1       0   598.4    .016       0     627     .06       0
   760.2    .016       0   793.9     .06       0   850.5    .016       0
     884     .07       0   964.4     .04       0    1009      .1       0
#XS Ineff= 2 , 0
                          736.68         2690.05
Permanent Ineff=
       F       F
Bank Sta=371.4,443.7
XS Rating Curve= 0 ,0
Exp/Cntr(USF)=0,0
Exp/Cntr=0.5,0.3

Type RM Length L Ch R = 1 ,28753   ,51.1,48.7,46.4
BEGIN DESCRIPTION:
xs 3
channel burned per survey data
END DESCRIPTION:
XS GIS Cut Line= 5
2218206.01567513516315.132974051 2218343.7167011516525.778327288
2218437.50226473516627.751519491 2218517.8898907516737.168010395
 2218835.7977636 517292.24879544
#Sta/Elev= 30
       0 2698.56    33.2 2693.11    69.7 2694.11   124.4 2685.64   201.3 2687.32
   241.4 2681.76   387.4 2681.19   401.52675.443  442.55 2672.55   459.2 2675.43
   491.2  2680.7   539.8 2680.45     598 2680.21   656.6 2679.56   770.3 2678.32
   793.3 2676.62   816.4    2677   876.3 2676.74   940.9 2678.02   950.1  2672.8
   954.7 2670.24     973 2669.88   996.2 2670.29  1002.5 2672.66  1014.6    2685
  1023.8 2688.16  1037.7 2688.03  1060.7 2708.44  1069.8 2712.76  1165.6  2722.7
#Mann= 13 ,-1,0
       0      .1       0   201.3     .07       0   401.5    .045       0
   459.2     .07       0   539.8     .08       0     598     .07       0
   656.6     .06       0   770.3     .07       0   793.3    .016       0
   816.4     .05       0   876.3      .1       0   950.1     .04       0
  1002.5      .1       0
#XS Ineff= 3 ,-1
       0   393.5 2680.98  470.84     776 2680.23     776 1123.61 2685.68
Permanent Ineff=
       F       F       F
Bank Sta=401.5,459.2
XS Rating Curve= 0 ,0
Exp/Cntr(USF)=0,0
Exp/Cntr=0.5,0.3