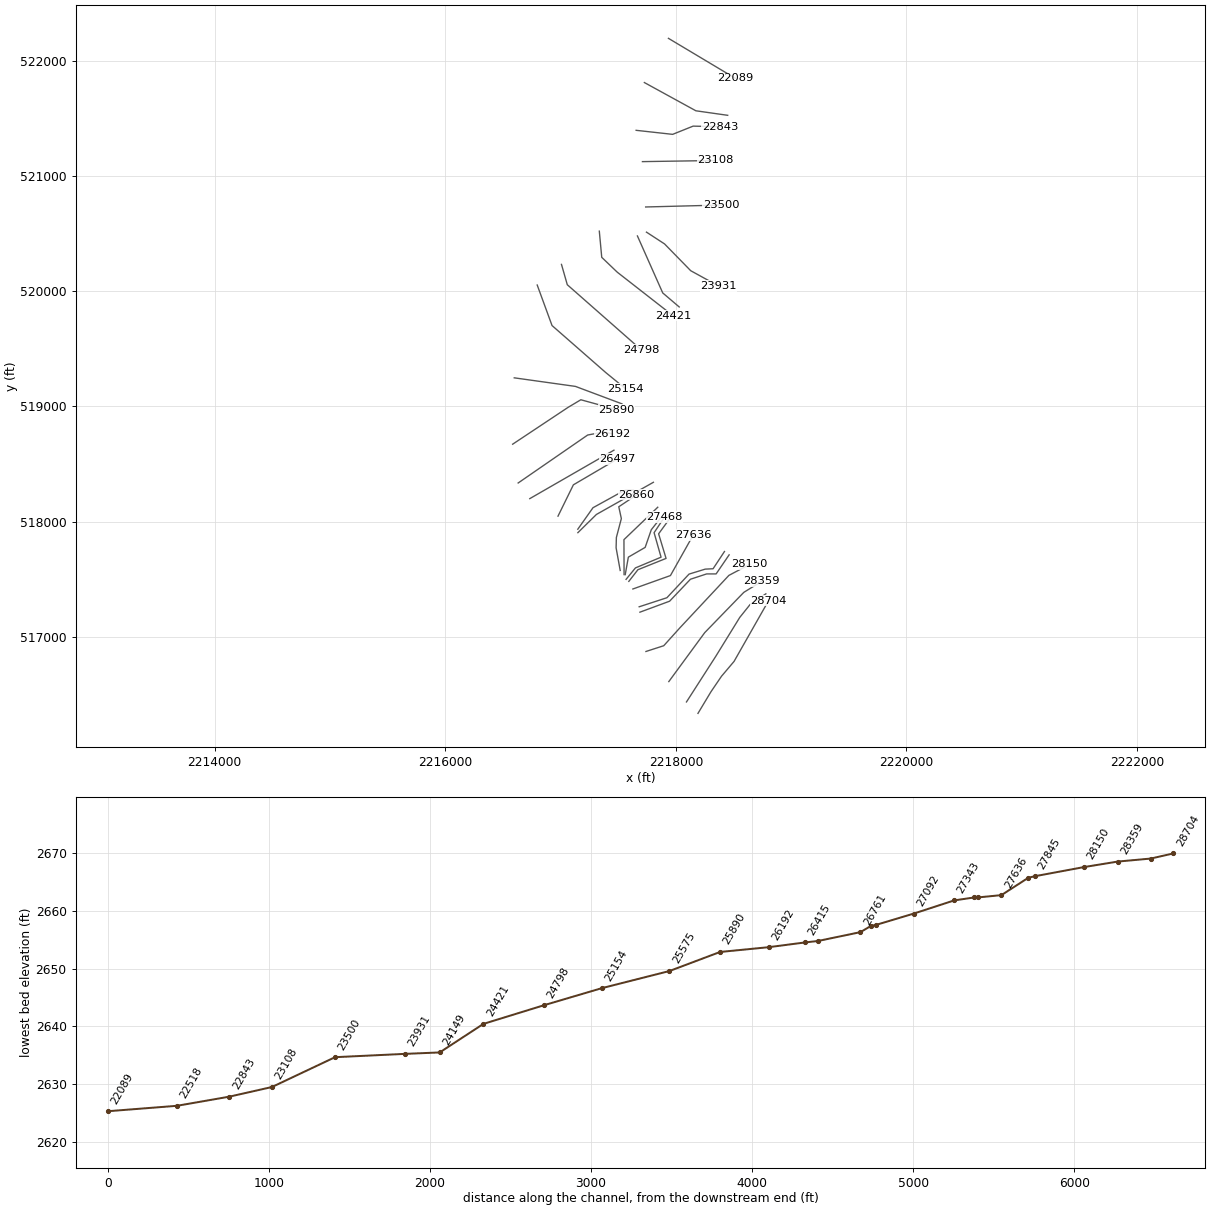
HEC-RAS study OLDFLDFK1.prj: OLDFLDFK1

--- OLDFLDFK1.g01 (geometry) --- (continued)

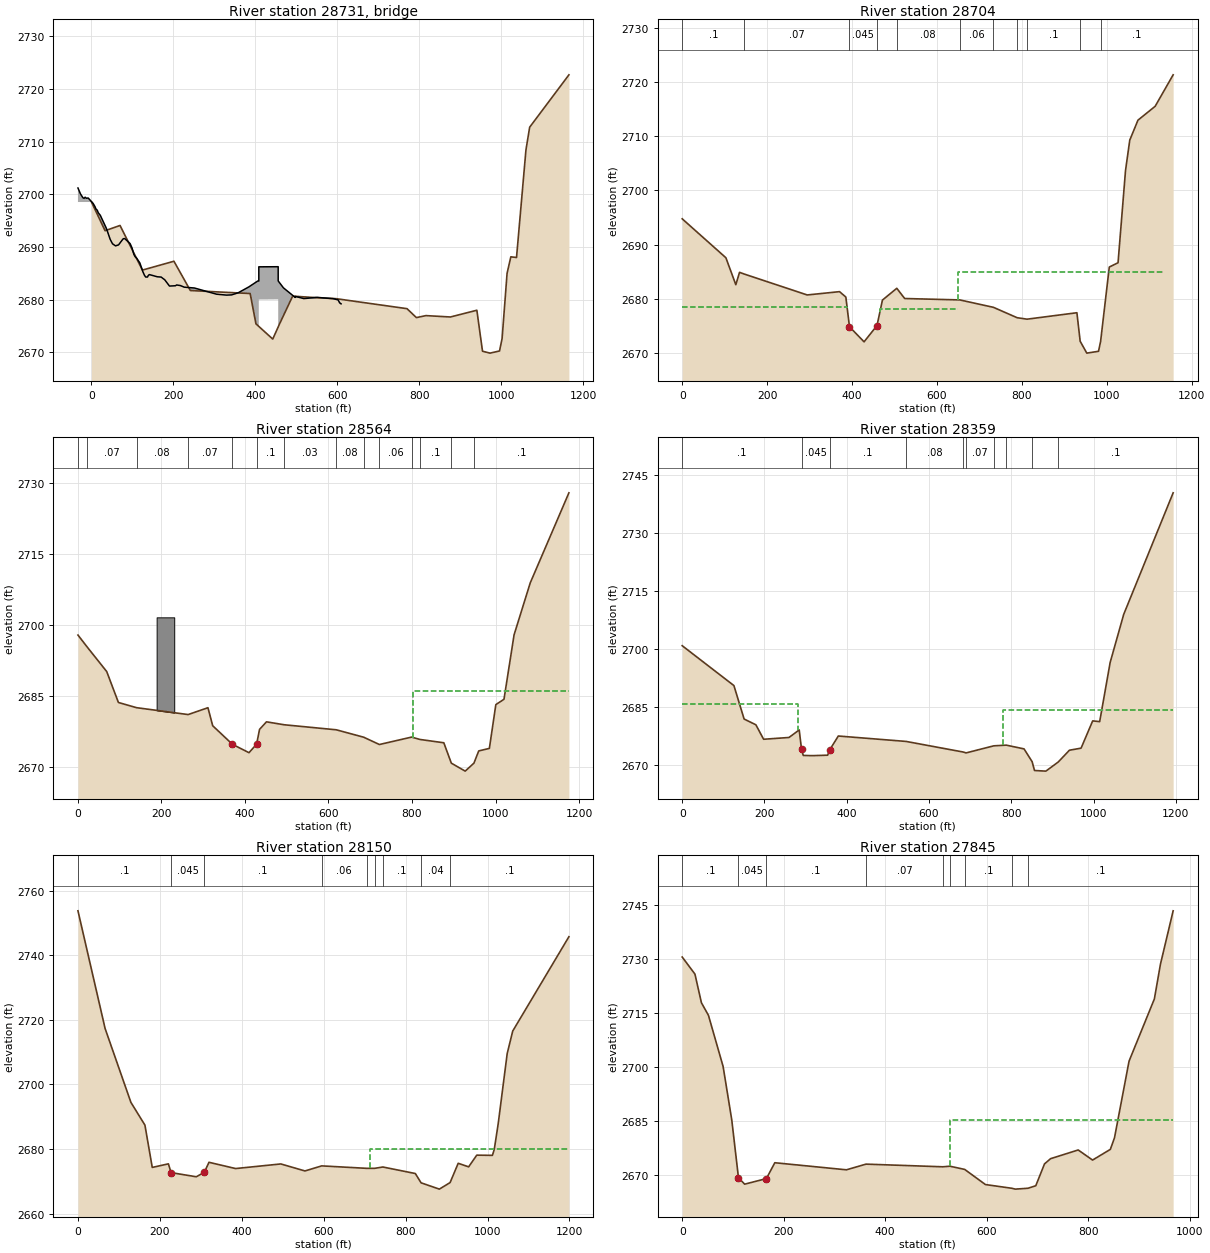
Type RM Length L Ch R = 3 ,28731   ,,,
BEGIN DESCRIPTION:
Bridge No.: 54075OLD010
JV notes: road deck updated per surveyed xs data
channel burned per survey data
END DESCRIPTION:
Bridge Culvert--1,0,-1,-1, 0
Deck Dist Width WeirC Skew NumUp NumDn MinLoCord MaxHiCord MaxSubmerge Is_Ogee
15,15,2.6,0, 60, 60, , , 0.98, 0, 0,0,,
     -33  -26.85 -21.058 -18.163 -15.539 -12.371  -8.117   3.902   8.651  10.796
  14.147  16.587  21.569  36.412  45.546  51.255  58.677  66.098    77.4  80.941
  94.129  98.878 103.462 106.358 110.628 118.049 125.471 129.525 132.421 136.868
 138.212 141.108 160.612     170 178.779 190.408 204.943  207.85 217.117 226.515
 251.235 305.316 329.722 342.355   358.3  384.19  405.93  408.51  408.51  455.84
  455.84  468.65   497.4 497.746 518.598 550.808 589.873 602.155 605.873 609.372
 2701.222700.1022699.3932699.2552699.473 2699.272699.3282698.3072697.6752697.257
2696.9962696.5192696.0352693.5532691.4982690.6372690.2372690.4262691.5832691.632
2690.6842689.8652688.6312688.205 2687.862687.0052685.325 2684.632684.3162684.327
2684.564 2684.792684.3732684.3152683.8042682.6082682.6692682.8162682.7012682.398
2682.2432681.0652680.8922680.937 2681.34 2682.45 2683.57 2683.56 2686.26 2686.28
 2683.58 2682.27 2680.452680.6422680.229 2680.462680.2182679.9792679.4282679.231
                                                                                
                                                                                
                                                                                
                                                                                
                                                         2680.05 2680.05 2680.09
 2680.09
     -38  -31.85 -26.058 -23.163 -20.539 -17.371 -13.117  -1.098   3.651   5.796
   9.147  11.587  16.569  20.275  31.412  40.546  46.255  53.677  61.098    72.4
  75.941  89.129  93.878  98.462 101.358 105.628 113.049 120.471 124.525 127.421
 131.868 133.212 136.108 155.612     165 173.779 185.408 199.943  202.85 212.117
 221.515 246.235 300.316 324.722 337.355   353.3  379.19  400.93  403.51  403.51
  450.84  450.84  463.65   492.4 492.746 513.598 552.874 584.873 595.588 598.516
 2701.222700.1022699.3932699.2552699.473 2699.272699.3282698.3072697.6752697.257
2696.9962696.5192696.0352695.3272693.5532691.4982690.6372690.2372690.4262691.583
2691.6322690.6842689.8652688.6312688.205 2687.862687.0052685.325 2684.632684.316
2684.3272684.564 2684.792684.3732684.3152683.8042682.6082682.6692682.8162682.701
2682.3982682.2432681.0652680.8922680.937 2681.34 2682.45 2683.57 2683.56 2686.26
 2686.28 2683.58 2682.27 2680.452680.6422680.2292680.4252680.2182680.0522679.828
                                                                                
                                                                                
                                                                                
                                                                                
                                                                 2680.05 2680.05
 2680.09 2680.09
BR Coef=-1 ,-1 , 0 ,, 0 ,,,0.8,0,1,0,
WSPro=,,,, 1 ,,,, 0 ,,,, 0 ,,,,-1 ,-1 ,-1 , 0 , 0 , 0 , 0 , 0
BR U #Sta/Elev= 30
       0 2698.56    33.2 2693.11    69.7 2694.11   124.4 2685.64   201.3 2687.32
   241.4 2681.76   387.4 2681.19   401.52675.443  442.55 2672.55   459.2 2675.43
   491.2  2680.7   539.8 2680.45     598 2680.21   656.6 2679.56   770.3 2678.32
   793.3 2676.62   816.4    2677   876.3 2676.74   940.9 2678.02   950.1  2672.8
   954.7 2670.24     973 2669.88   996.2 2670.29  1002.5 2672.66  1014.6    2685
  1023.8 2688.16  1037.7 2688.03  1060.7 2708.44  1069.8 2712.76  1165.6  2722.7
BR U #Mann= 13
       0      .1   201.3     .07   401.5     .04   459.2     .07   539.8     .08
     598     .07   656.6     .06   770.3     .07   793.3    .016   816.4     .05
   876.3      .1   950.1     .04  1002.5      .1
BR D #Sta/Elev= 30
       0 2694.75   102.9 2687.55   126.3 2682.56     135 2684.85   146.7 2684.52
   294.4 2680.67   370.6 2681.28   385.4 2680.28     3942674.784  428.34    2672
   458.8 2675.01   471.6 2679.72   505.4  2681.9     524 2680.01   653.7 2679.75
   733.1 2678.38   788.8 2676.46   812.3 2676.19   929.6 2677.38   937.3 2672.11
   952.9 2669.91   980.5 2670.25   985.4 2672.05  1005.9 2685.83  1026.5 2686.63
  1044.1 2703.67  1054.1  2709.3  1073.4 2712.99  1113.9 2715.56  1156.3 2721.38
BR D #Mann= 11
       0      .1   146.7     .07     394     .04   458.8     .07   505.4     .08
   653.7     .06   733.1     .07   788.8    .016   812.3      .1   937.3     .04
   985.4      .1
BC Design=,, 0 ,, 0 ,,,,,,
BC Use User HTab Curves=0
BC User HTab FreeFlow(D)= 0

Type RM Length L Ch R = 1 ,28704   ,136.6,140.5,145.8
BEGIN DESCRIPTION:
xs 2
channel burned per survey data
END DESCRIPTION:
XS GIS Cut Line= 5
2218192.13867084516335.9821744372218304.27940906516522.883404817
2218395.92130267516657.9346164482218505.04750492 516786.95675613
 2218804.2958479517314.127987995
#Sta/Elev= 30
       0 2694.75   102.9 2687.55   126.3 2682.56     135 2684.85   146.7 2684.52
   294.4 2680.67   370.6 2681.28   385.4 2680.28     3942674.784  428.34    2672
   458.8 2675.01   471.6 2679.72   505.4  2681.9     524 2680.01   653.7 2679.75
   733.1 2678.38   788.8 2676.46   812.3 2676.19   929.6 2677.38   937.3 2672.11
   952.9 2669.91   980.5 2670.25   985.4 2672.05  1005.9 2685.83  1026.5 2686.63
  1044.1 2703.67  1054.1  2709.3  1073.4 2712.99  1113.9 2715.56  1156.3 2721.38
#Mann= 11 ,-1,0
       0      .1       0   146.7     .07       0     394    .045       0
   458.8     .07       0   505.4     .08       0   653.7     .06       0
   733.1     .07       0   788.8    .016       0   812.3      .1       0
   937.3     .04       0   985.4      .1       0
#XS Ineff= 3 ,-1
       0   388.5  2678.4   465.8     650    2678     650 1131.72    2685
Permanent Ineff=
       F       F       F
Bank Sta=394,458.8
XS Rating Curve= 0 ,0
Exp/Cntr(USF)=0,0
Exp/Cntr=0.5,0.3

Type RM Length L Ch R = 1 ,28564   ,206.6,204.5,201.8
BEGIN DESCRIPTION:
xs 1
END DESCRIPTION:
XS GIS Cut Line= 5
2218092.31511147516435.1611482232218346.55123993516831.320256038
2218554.22195465517168.452722786 2218644.0869084517280.783914969
2218780.91121301 517373.44836782
#Sta/Elev= 30
       0 2697.86    21.4 2695.41    68.9 2690.12    96.9 2683.57   140.2 2682.47
   263.8 2681.01   311.3 2682.46   322.7 2678.64     3702674.701   409.6 2672.93
  427.862674.735   434.9 2677.87   451.5 2679.47   493.6 2678.85   618.6 2677.78
   684.3 2676.21   721.9 2674.66   798.9 2676.23   819.2 2675.73   876.2 2675.03
   894.2 2670.71   927.4 2669.02   948.3 2670.71   959.8  2673.3   985.3 2673.84
  1000.8 2683.12  1020.3 2684.25  1044.5 2697.92  1083.1  2708.9  1175.8 2728.01
#Mann= 14 ,-1,0
       0      .1       0    21.4     .07       0   140.2     .08       0
   263.8     .07       0     370    .045       0  427.86      .1       0
   493.6     .03       0   618.6     .08       0   684.3      .1       0
   721.9     .06       0   798.9    .016       0   819.2      .1       0
   894.2     .04       0   948.3      .1       0
#XS Ineff= 2 , 0
                          803.15         2685.94
Permanent Ineff=
       F       F
#Block Obstruct= 1 ,-1
  188.38  230.54 2701.62
Bank Sta=370,427.86
XS Rating Curve= 0 ,0
Exp/Cntr(USF)=0,0
Exp/Cntr=0.3,0.1

Type RM Length L Ch R = 1 ,28359   ,215.2,209.5,214.3
XS GIS Cut Line= 4
2217939.16081721516611.7991009352218250.84378939517036.946360372
2218589.32545221517386.0944076412218742.37053982517480.797309137
#Sta/Elev= 30
       0 2700.93   125.7 2690.62   150.5 2681.97   179.1 2680.48   197.9 2676.74
   259.6  2677.2   284.4 2679.15  290.03 2674.18   294.3 2672.56   316.5  2672.5
   353.5 2672.62   358.8 2674.04   379.5 2677.58   544.2 2676.18   683.5 2673.43
     690 2673.21   757.4 2675.04   787.7 2675.22   830.9 2674.25   850.6 2670.95
   856.4 2668.66     884  2668.5   914.1 2670.86   941.3 2673.91   969.6 2674.44
   997.8 2681.49  1014.8  2681.3  1040.3 2696.61  1073.2 2709.03  1193.4 2740.46
#Mann= 10 ,-1,0
       0      .1       0  290.03    .045       0   358.8      .1       0
   544.2     .08       0   683.5     .06       0     690     .07       0
   757.4    .016       0   787.7      .1       0   850.6     .04       0
   914.1      .1       0
#XS Ineff= 2 , 0
          282.59 2685.89  778.82         2684.42
Permanent Ineff=
       F       F
Bank Sta=290.03,358.8
XS Rating Curve= 0 ,0
Exp/Cntr(USF)=0,0
Exp/Cntr=0.3,0.1

Type RM Length L Ch R = 1 ,28150   ,325.6,304.4,251.3
XS GIS Cut Line= 5
 2217741.0812633516873.1824298022217895.25658619516923.212832593
 2218036.1585369517079.430212736 2218460.1445812517533.529097381
2218641.42964094517629.233180139
#Sta/Elev= 30
       0 2753.74    66.3 2717.28   129.3 2694.41   163.5 2687.38   181.4 2674.27
   220.8 2675.38  227.37 2672.66   288.9 2671.38   308.6 2672.76   319.9 2675.86
     385 2673.92   495.3 2675.35   554.2 2673.18   595.2 2674.75   704.8 2673.99
   724.2 2673.99   744.5  2674.4   823.7 2672.38   837.8  2669.5   882.4 2667.55
   908.6 2669.58   928.4 2675.55   953.9 2674.45   973.7 2678.07  1011.9 2678.01
  1016.4 2679.82  1026.1 2687.85    1048 2709.52  1061.5  2716.5  1198.7 2745.72
#Mann= 9 ,-1,0
       0      .1       0  227.37    .045       0   308.6      .1       0
   595.2     .06       0   704.8     .07       0   724.2    .016       0
   744.5      .1       0   837.8     .04       0   908.6      .1       0
#XS Ineff= 2 , 0
                          712.37            2680
Permanent Ineff=
       F       F
Bank Sta=227.37,308.6
XS Rating Curve= 0 ,0
Exp/Cntr(USF)=0,0
Exp/Cntr=0.3,0.1

Type RM Length L Ch R = 1 ,27845   ,42.4,41.2,42.4
XS GIS Cut Line= 6
2217688.59709019517214.2767742922217946.12714343517309.617687617
2218126.94611698517500.2995142682218267.21780555 517546.32616208
2218349.40824807 517546.326162082218462.28312247517711.802919691
#Sta/Elev= 30
       0 2730.51    25.1 2725.77    37.9 2717.79    51.7 2714.31    80.6 2700.09
    97.7  2685.2   110.9 2669.12   123.1 2667.35   165.9  2668.9   182.5 2673.31
   323.6 2671.34   362.2 2672.92   513.4 2672.18   527.6 2672.34   556.7 2671.45
   597.6 2667.24     650  2666.2   656.3 2665.97   681.3 2666.21   696.8 2666.91
     714 2672.99     726 2674.44   780.4 2676.86   808.7 2674.05   843.7 2677.02
   851.9 2680.24   880.6 2701.56   930.5 2718.86   942.5 2728.54   967.5 2743.36
#Mann= 9 ,-1,0
       0      .1       0   110.9    .045       0   165.9      .1       0
   362.2     .07       0   513.4    .016       0   527.6     .07       0
   556.7      .1       0     650     .04       0   681.3      .1       0
#XS Ineff= 2 , 0
                          527.32         2685.13
Permanent Ineff=
       F       F
Bank Sta=110.9,165.9
XS Rating Curve= 0 ,0
Exp/Cntr=0.3,0.1

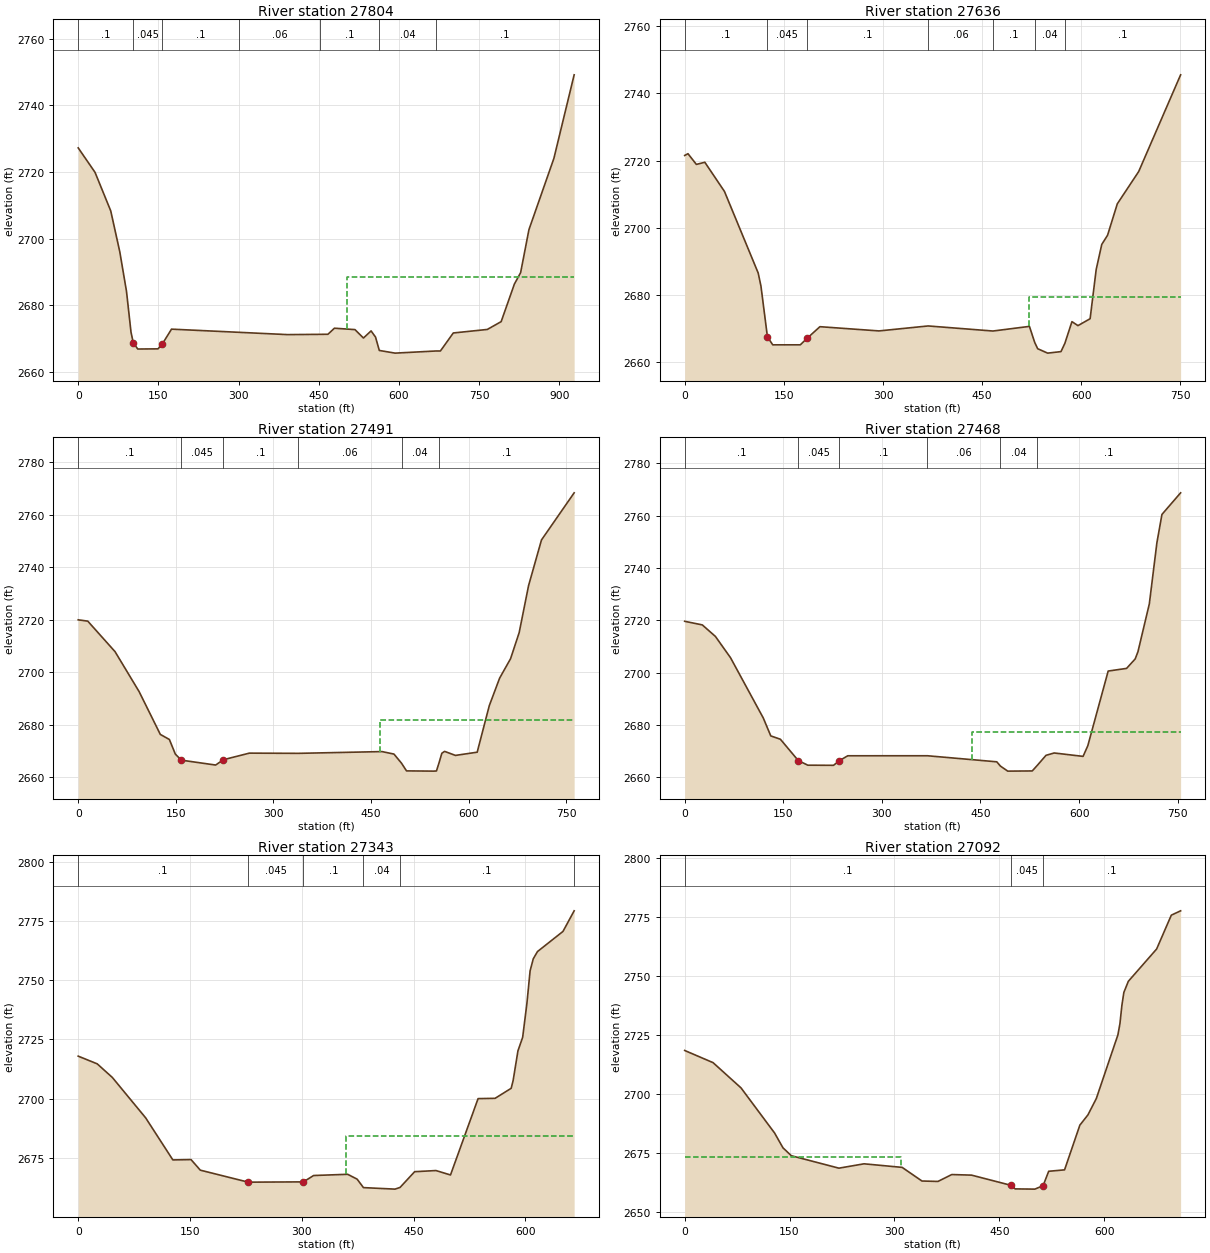
Type RM Length L Ch R = 1 ,27804   ,168.3,168.1,155.4
XS GIS Cut Line= 6
2217682.25107533517261.1259563372217922.70284137517339.723917078
2218114.52122089517544.7960903862218255.16320731517587.969319625
2218323.10730646517591.2569373262218421.81781026517740.830292864
#Sta/Elev= 30
       0 2727.24    31.5  2719.9    60.9 2708.34    77.8  2696.1    90.4  2684.2
    98.8    2672     103 2668.84   111.4 2666.94   149.3 2666.99     157 2668.35
   174.6  2672.9   391.9 2671.26   467.3 2671.36   479.5 2673.18   517.9 2672.76
   533.8 2670.24   548.1 2672.37   556.4 2670.52  563.49 2666.51     593 2665.71
   669.4 2666.35   677.8 2666.35   701.9 2671.75   765.6 2672.81   791.5 2675.15
   816.2 2686.39   827.9 2689.82   843.5 2702.73   890.2  2724.1   928.1 2749.14
#Mann= 7 ,-1,0
       0      .1       0     103    .045       0     157      .1       0
   300.7     .06       0   452.2      .1       0  563.49     .04       0
   669.4      .1       0
#XS Ineff= 2 , 0
                          503.66         2688.39
Permanent Ineff=
       F       F
Bank Sta=103,157
XS Rating Curve= 0 ,0
Exp/Cntr=0.3,0.1

Type RM Length L Ch R = 1 ,27636   ,143.9,144.7,149.9
XS GIS Cut Line= 3
2217627.48961915517415.5813455892217953.25007648517532.124957478
 2218151.2338027517884.564072952
#Sta/Elev= 30
       0 2721.53       5 2722.06    17.7 2718.87    30.5 2719.51    60.2 2710.82
   111.2 2686.54   115.4 2682.63  125.16 2667.56   133.2 2665.16   174.9 2665.16
  185.55 2667.17   204.6 2670.56   293.9  2669.3   368.3 2670.78   466.3 2669.27
   521.5 2670.65   529.5 2665.87     534    2664   549.1 2662.69   569.2 2663.14
   575.1  2665.6   585.8 2672.06   594.9 2670.88   613.3 2672.93   622.5 2687.59
   630.9 2695.04   639.7 2697.79   654.4 2707.12   686.8 2716.75   750.2 2745.54
#Mann= 7 ,-1,0
       0      .1       0  125.16    .045       0  185.55      .1       0
   368.3     .06       0   466.3      .1       0   529.5     .04       0
   575.1      .1       0
#XS Ineff= 2 , 0
                          521.01         2679.47
Permanent Ineff=
       F       F
Bank Sta=125.16,185.55
XS Rating Curve= 0 ,0
Exp/Cntr(USF)=0,0
Exp/Cntr=0.3,0.1

Type RM Length L Ch R = 1 ,27491   ,23.3,23.6,25.6
XS GIS Cut Line= 5
2217592.38612159517481.5759209962217671.01795612517582.673993961
2217915.33829911517680.9637871212217850.74786361517894.393052268
2217937.80453755518013.744943963
#Sta/Elev= 30
       0 2719.99    14.7 2719.49    56.6 2707.86    93.6 2692.62   126.2 2676.29
   140.1 2674.37   149.3 2668.77   158.6 2666.48   211.2 2664.62   223.1 2666.65
     263 2669.16   338.4 2669.08   466.9 2669.75   485.2  2668.8   496.8 2665.33
   504.5 2662.39   546.3  2662.3   550.5 2662.36   554.3 2665.32   558.8 2669.12
     563 2669.83   579.7 2668.29   613.1 2669.52   631.7 2687.27   647.6 2697.77
   664.4 2705.17   677.6  2715.1   692.1 2733.07   711.9 2750.45   762.1 2768.42
#Mann= 6 ,-1,0
       0      .1       0   158.6    .045       0   223.1      .1       0
   338.4     .06       0   496.8     .04       0   554.3      .1       0
#XS Ineff= 2 , 0
                          464.23         2681.71
Permanent Ineff=
       F       F
Bank Sta=158.6,223.1
XS Rating Curve= 0 ,0
Exp/Cntr(USF)=0,0
Exp/Cntr=0.3,0.1

Type RM Length L Ch R = 1 ,27468   ,117.5,124.6,217
XS GIS Cut Line= 5
 2217568.5274251517499.0729790042217649.69829891517598.494062926
2217871.91205877 517691.671495722217811.43194634517904.222031585
2217902.51946164518040.830609655
#Sta/Elev= 30
       0 2719.59    26.8 2718.21    46.7 2713.82    69.8 2705.64   119.6  2682.6
     131 2675.76   145.6 2674.49   172.8 2666.34   187.3 2664.56   226.5 2664.51
   235.1 2666.25   248.1 2668.16   369.3 2668.17   474.8 2665.85   480.4 2664.21
   491.5 2662.29   528.8 2662.36   536.1 2664.39   549.7 2668.33   562.2 2669.23
   606.1 2667.93   613.3 2671.99   644.3 2700.56   672.3 2701.58   685.4  2705.2
   689.6 2707.96   706.9 2726.24   718.4 2749.61   726.1 2760.46   754.5 2768.72
#Mann= 6 ,-1,0
       0      .1       0   172.8    .045       0   235.1      .1       0
   369.3     .06       0   480.4     .04       0   536.1      .1       0
#XS Ineff= 2 , 0
                          436.73         2677.34
Permanent Ineff=
       F       F
Bank Sta=172.8,235.1
XS Rating Curve= 0 ,0
Exp/Cntr(USF)=0,0
Exp/Cntr=0.3,0.1

Type RM Length L Ch R = 1 ,27343   ,161.5,250.9,133.4
XS GIS Cut Line= 5
2217561.16016962517540.1230808892217588.31994141517691.970895887
  2217733.995081517776.536548955 2217787.0800895517929.618899034
2217898.80551435518071.590433381
#Sta/Elev= 30
       0 2717.92    25.5 2714.67    45.8 2708.92    90.5 2691.87     127 2674.11
   151.4 2674.25   163.8 2669.79   228.1 2664.72   302.1 2664.84   315.9 2667.53
   361.5 2668.04   374.2    2666   382.7 2662.42     425 2661.78   431.8 2662.49
   451.4 2669.14     480 2669.62   499.5 2667.76   536.5 2699.99   559.3 2700.11
   580.9 2704.34   583.5 2707.58     590 2720.17   596.3 2725.85     602 2740.14
   606.3 2753.92   610.5 2758.98   616.2 2762.07   650.4 2770.57   665.4 2779.27
#Mann= 6 ,-1,0
       0      .1       0   228.1    .045       0   302.1      .1       0
   382.7     .04       0   431.8      .1       0   665.4      .1       0
#XS Ineff= 2 , 0
                          359.66         2684.27
Permanent Ineff=
       F       F
Bank Sta=228.1,302.1
XS Rating Curve= 0 ,0
Exp/Cntr(USF)=0,0
Exp/Cntr=0.3,0.1

Type RM Length L Ch R = 1 ,27092   ,138,232.3,224.9
XS GIS Cut Line= 3
2217551.17535133 517540.54482427 2217550.0206046517843.669238932
2217843.18412614518124.963528206
#Sta/Elev= 30
       0 2718.29    40.6 2713.13    80.6 2702.42   128.6  2683.3   140.6 2677.01
   152.6 2673.66   220.6 2668.39   256.6 2670.23   311.1 2668.72   339.4 2662.94
   362.3 2662.76   382.1 2665.68   410.4 2665.43466.98792661.095   472.6  2659.6
   500.9  2659.5512.68772660.967   520.7 2667.07   543.4 2667.67   565.3 2686.65
   576.8 2690.96   588.8  2697.9   619.7 2724.91   622.6 2729.65   625.4 2737.43
   628.2 2742.89   634.6 2747.61   675.1 2761.31   696.1 2775.66   709.4  2777.5
#Mann= 3 ,0,0
       0      .1       0466.9879    .045       0512.6877      .1       0
#XS Ineff= 2 , 0
          308.91 2673.32
Permanent Ineff=
       F       F
Bank Sta=466.9879,512.6877
XS Rating Curve= 0 ,0
Exp/Cntr(USF)=0,0
Exp/Cntr=0.3,0.1

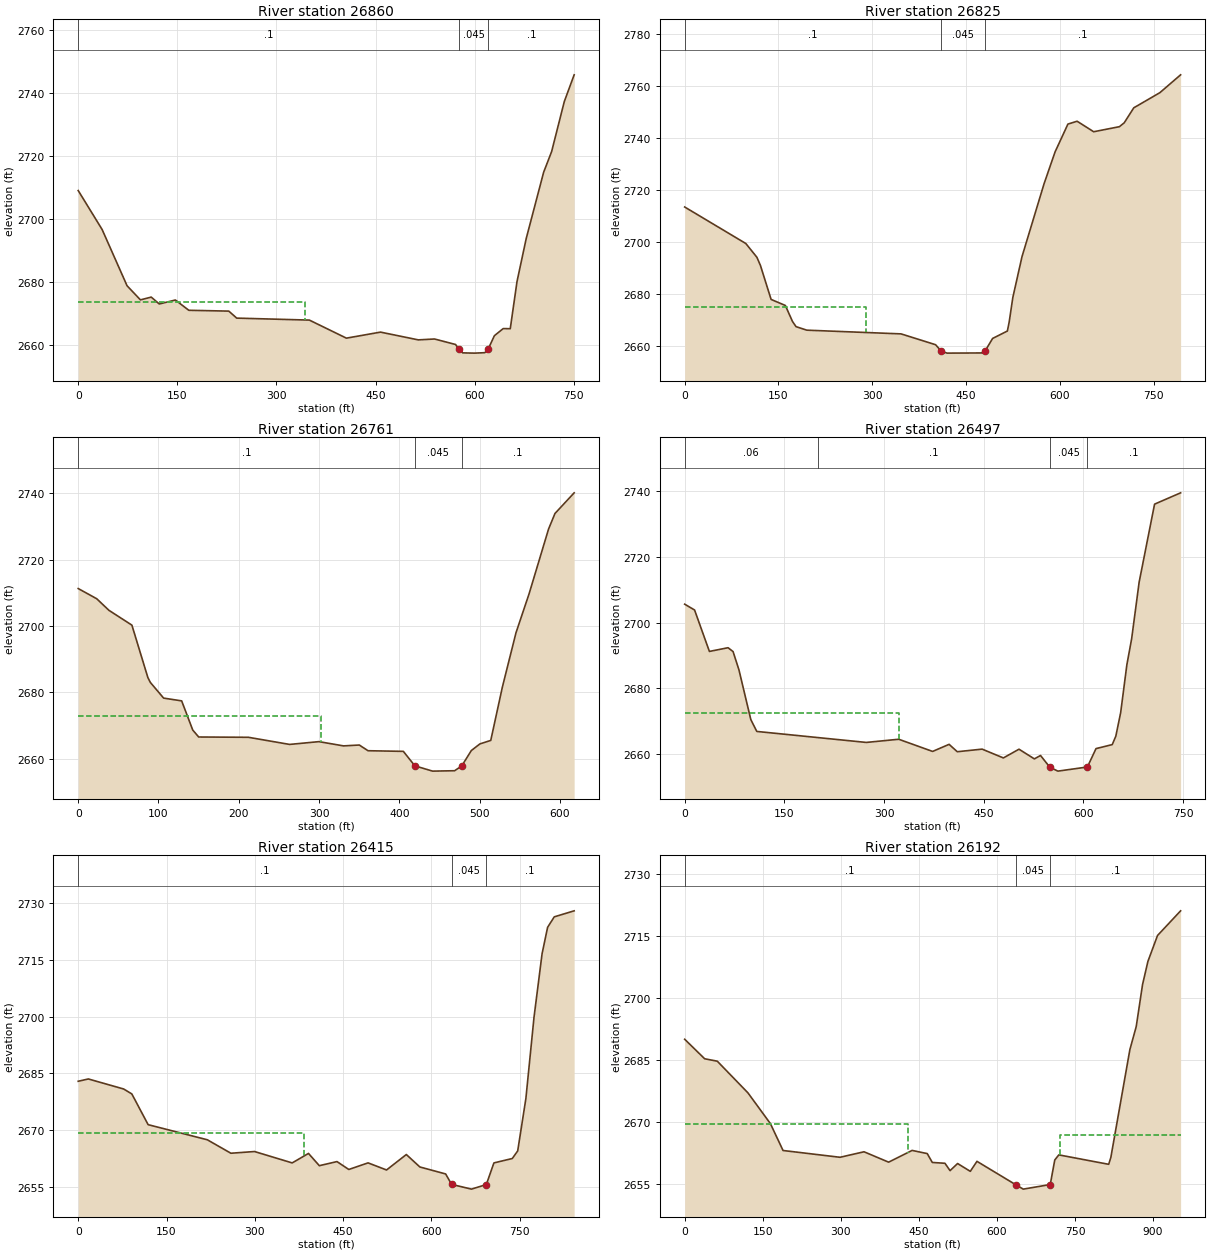
Type RM Length L Ch R = 1 ,26860   ,160.8,35.3,32
XS GIS Cut Line= 6
  2217517.498388517576.4579015582217482.03082971517772.743708932
2217484.40514398517862.8699038962217527.48531846518026.392008904
2217505.24275068518129.1329079822217660.54209329518232.810905853
#Sta/Elev= 30
       0  2709.1    36.2 2696.75    73.9 2678.93    94.2 2674.44   110.5 2675.32
   122.7 2673.14   147.1  2674.4   167.4 2671.14   227.9 2670.88   239.9 2668.66
   349.9 2668.03   405.9 2662.31   457.5 2664.22   514.8 2661.76   539.3 2662.04
   571.1  2660.3  575.81 2658.95   581.8 2657.64   599.9 2657.56   615.5  2657.7
   620.8    2659   629.9 2663.08   643.2 2665.34   653.9  2665.3   664.1 2680.23
     678 2693.85   704.4 2714.89   716.5 2721.45   735.7 2737.32   750.6 2745.79
#Mann= 3 ,0,0
       0      .1       0  575.81    .045       0   620.8      .1       0
#XS Ineff= 2 , 0
          343.44 2673.77
Permanent Ineff=
       F       F
Bank Sta=575.81,620.8
XS Rating Curve= 0 ,0
Exp/Cntr(USF)=0,0
Exp/Cntr=0.3,0.1

Type RM Length L Ch R = 1 ,26825   ,64.5,63.6,62.4
BEGIN DESCRIPTION:
effective xs A
END DESCRIPTION:
XS GIS Cut Line= 4
2217150.46511134517904.2871340632217311.16681566518062.331420272
2217386.47345562518104.9228805762217805.38252821 518341.52819245
#Sta/Elev= 30
       0 2713.46    97.8 2699.43   115.4 2694.18   121.1 2691.04   138.2 2677.96
     161 2675.64   172.4 2669.49   178.1 2667.51   195.2 2666.16     346 2664.73
   401.2 2660.57     410 2658.19   419.5 2657.34   474.8 2657.41   480.7 2658.29
   492.4 2662.98     516 2665.83   518.9 2669.32   524.7  2678.7   539.4 2694.42
   574.6 2722.35   592.2 2734.58   612.8  2745.3   627.5  2746.4     654 2742.36
   695.2 2744.31   702.8 2745.79   718.1 2751.55   759.8 2757.36     793 2764.22
#Mann= 3 ,-1,0
       0      .1       0     410    .045       0   480.7      .1       0
#XS Ineff= 2 , 0
          289.63 2674.94
Permanent Ineff=
       F       F
Bank Sta=410,480.7
XS Rating Curve= 0 ,0
Exp/Cntr(USF)=0,0
Exp/Cntr=0.3,0.1

Type RM Length L Ch R = 1 ,26761   ,262.9,263.5,265.4
BEGIN DESCRIPTION:
end detailed ae zone
END DESCRIPTION:
XS GIS Cut Line= 6
2217149.79756647517934.3237733992217281.62932381518120.878190309
2217472.46850905518226.1404469762217486.61743088518234.319892555
2217562.70454906518273.4382526432217632.35171947518273.438252643
#Sta/Elev= 30
       0 2711.34    23.1 2708.26    38.2 2704.79    66.9  2700.3    86.8 2684.49
    89.9 2683.03   106.4 2678.31   128.9 2677.47   142.7 2668.68   150.1 2666.58
   212.1 2666.49   263.4 2664.34   299.9 2665.18   330.6  2663.9   350.2 2664.16
   361.1 2662.44   405.1 2662.25  419.42 2657.89   441.5 2656.29     469 2656.41
   477.9 2657.87   489.8  2662.5   500.5  2664.5     514 2665.55   528.4 2681.55
   545.4 2697.98   561.8 2709.79     586 2729.27     594 2733.97   617.9  2740.2
#Mann= 3 ,0,0
       0      .1       0  419.42    .045       0   477.9      .1       0
#XS Ineff= 2 , 0
          302.87 2672.86
Permanent Ineff=
       F       F
Bank Sta=419.42,477.9
XS Rating Curve= 0 ,0
Exp/Cntr(USF)=0,0
Exp/Cntr=0.3,0.1

Type RM Length L Ch R = 1 ,26497   ,83,82.7,82.3
XS GIS Cut Line= 3
2216978.14928367518047.8074027192217111.38433041518319.487805304
2217493.96988364518544.275426073
#Sta/Elev= 30
       0 2705.61    14.9 2703.84    37.2 2691.22    65.3 2692.35    72.8 2691.18
    81.7 2685.59    99.5 2670.48   108.5 2666.85   273.3  2663.5   322.1 2664.47
   373.1 2660.76   397.9 2662.92   410.2 2660.67   447.6 2661.46   479.6 2658.78
   503.1 2661.44   526.2 2658.49   535.5 2659.52   549.4 2655.97   561.6 2654.76
     606 2656.02     619 2661.62   643.4 2662.84   648.8 2665.41   656.1 2672.59
   665.4 2687.13   672.6 2695.07   683.9 2712.33   707.1 2736.08   746.3 2739.53
#Mann= 4 ,-1,0
       0     .06       0     200      .1       0   549.4    .045       0
     606      .1       0
#XS Ineff= 2 , 0
           321.8 2672.54
Permanent Ineff=
       F       F
Bank Sta=549.4,606
XS Rating Curve= 0 ,0
Exp/Cntr(USF)=0,0
Exp/Cntr=0.3,0.1

Type RM Length L Ch R = 1 ,26415   ,219.5,222.8,226.9
XS GIS Cut Line= 2
2216733.22793495518199.6968520562217463.22721777 518620.23991716
#Sta/Elev= 30
       0 2682.93    17.2 2683.54    77.3 2680.89    91.1 2679.59   118.8 2671.49
   219.3 2667.51   259.4 2663.96   299.5 2664.41   363.5 2661.41   391.2 2663.91
   409.6 2660.68   439.6 2661.76   459.7 2659.68   492.4 2661.42   523.8 2659.55
   557.4 2663.62   580.4 2660.34   624.2  2658.5   634.3 2655.75   668.1  2654.5
   693.32655.714   706.2 2661.41   737.4 2662.57   746.6 2664.57   760.5 2678.38
   774.3 2699.78     788 2716.53   797.4 2723.51   808.7 2726.27   842.5 2727.86
#Mann= 3 ,-1,0
       0      .1       0   634.3    .045       0   693.3      .1       0
#XS Ineff= 2 , 0
          383.66  2669.2
Permanent Ineff=
       F       F
Bank Sta=634.3,693.3
XS Rating Curve= 0 ,0
Exp/Cntr(USF)=0,0
Exp/Cntr=0.3,0.1

Type RM Length L Ch R = 1 ,26192   ,306.1,302.3,296.8
XS GIS Cut Line= 4
2216632.60706505 518335.57864925 2217235.5402198518751.886384514
2217376.63358863518778.1976093992217451.50049619518761.745352924
#Sta/Elev= 30
       0 2689.93    38.4 2685.21    62.7 2684.62   121.6 2676.96   164.7 2669.53
     189 2663.03   298.5 2661.39   344.6 2662.72   391.9 2660.21     437 2663.05
   466.1 2662.28   475.8 2660.14   500.1 2659.94   509.9 2658.16   524.4 2659.88
   548.8 2657.99   561.6 2660.41   635.9 2654.77   650.5 2653.69   702.4  2654.8
   711.1 2660.74   718.9 2661.97   814.7 2659.69   818.8 2661.33   855.4 2687.42
   867.6 2692.99   879.8 2703.19   890.1 2708.76   908.5 2715.01   952.9 2720.98
#Mann= 3 ,0,0
       0      .1       0   635.9    .045       0   702.4      .1       0
#XS Ineff= 2 , 0
          428.57 2669.51  721.69         2666.78
Permanent Ineff=
       F       F
Bank Sta=635.9,702.4
XS Rating Curve= 0 ,0
Exp/Cntr(USF)=0,0
Exp/Cntr=0.3,0.1

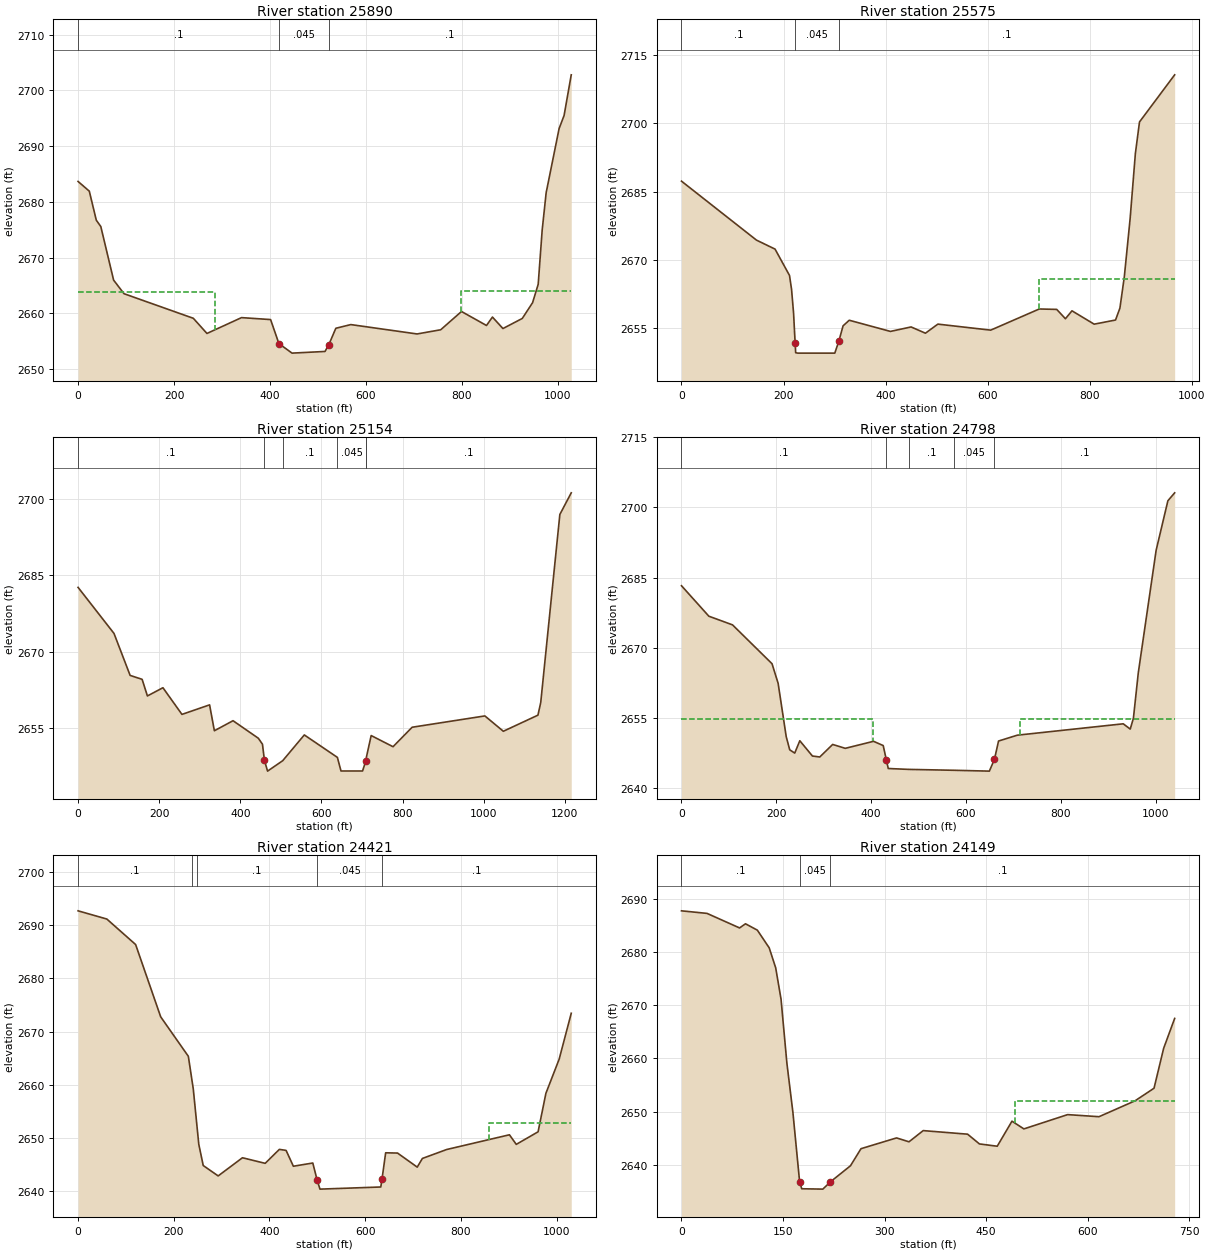
Type RM Length L Ch R = 1 ,25890   ,356.8,314.7,269.3
XS GIS Cut Line= 4
2216584.70695656518672.1399378672217066.22909982518992.314347263
2217176.28005376519057.8852442942217486.58720856518972.452958132
#Sta/Elev= 30
       0 2683.66    23.4 2681.92      38 2676.71    47.4 2675.57    74.1 2665.96
    95.8 2663.52   240.3 2659.11   268.7 2656.39   340.8 2659.23   401.4 2658.88
   418.7 2654.57   446.1 2652.86   514.8 2653.16   522.9  2654.4   537.4 2657.32
   568.7 2657.98   706.8  2656.3     756 2657.05   799.4 2660.33   851.5 2657.82
   863.9 2659.33   885.8 2657.27   926.1 2659.08   947.6 2661.91   959.3 2665.21
   967.6 2674.93   975.9 2681.64  1002.9 2693.15  1013.3  2695.5  1028.2 2702.79
#Mann= 3 ,-1,0
       0      .1       0   418.7    .045       0   522.9      .1       0
#XS Ineff= 2 , 0
          284.62 2663.87   799.1         2664.02
Permanent Ineff=
       F       F
Bank Sta=418.7,522.9
XS Rating Curve= 0 ,0
Exp/Cntr(USF)=0,0
Exp/Cntr=0.3,0.1

Type RM Length L Ch R = 1 ,25575   ,472.5,420.6,388.6
XS GIS Cut Line= 3
2216598.57277744519248.2017689452217129.25555837519173.830547865
2217532.62489304519022.567047363
#Sta/Elev= 30
       0 2687.27     147 2674.34   183.4 2672.37   211.7  2666.6   215.7  2663.6
   219.7 2658.32  222.722651.827   223.8 2649.66   227.8 2649.56   300.5 2649.56
   308.4 2652.17   316.7 2655.54   328.8 2656.77   409.6 2654.32     450  2655.3
   478.2 2653.93   502.5 2655.92   606.1  2654.6   701.3 2659.24   735.5 2659.15
   752.6  2657.1   765.4 2658.84   808.9 2655.91   850.8 2656.82   859.4 2659.44
     868 2666.28   879.5 2679.18   889.7 2693.35   897.8 2700.26   966.7 2710.59
#Mann= 3 ,-1,0
       0      .1       0  222.72    .045       0   308.4      .1       0
#XS Ineff= 2 , 0
                          700.85         2665.83
Permanent Ineff=
       F       F
Bank Sta=222.72,308.4
XS Rating Curve= 0 ,0
Exp/Cntr(USF)=0,0
Exp/Cntr=0.3,0.1

Type RM Length L Ch R = 1 ,25154   ,354.9,356.2,354.6
XS GIS Cut Line= 4
2216797.73638643520053.6799091192216926.31036186519701.992270451
2217392.70615507519293.5808190962217564.13812231519153.662081131
#Sta/Elev= 30
       0 2682.64    88.6  2673.6   128.3 2665.37   157.9  2664.6   170.9 2661.34
   209.2 2662.95   256.1 2657.72   324.2 2659.59     336 2654.51     382 2656.48
   444.4 2653.04   454.6 2651.86   459.3 2648.73   467.1 2646.59   504.5 2648.64
   557.7 2653.69  639.222649.286   648.1 2646.62   701.3 2646.62   709.6 2648.67
   710.8 2649.34   722.5 2653.57   776.4 2651.38   823.5  2655.2  1002.8 2657.42
  1048.3 2654.41  1133.6 2657.57  1140.5 2660.05  1187.6 2696.94  1215.7 2701.19
#Mann= 6 ,-1,0
       0      .1       0   459.3     .05       0   504.5      .1       0
  639.22    .045       0   709.6    .045       0   710.8      .1       0
Bank Sta=459.3,709.6
XS Rating Curve= 0 ,0
Exp/Cntr(USF)=0,0
Exp/Cntr=0.3,0.1

Type RM Length L Ch R = 1 ,24798   ,385,377.5,382.4
XS GIS Cut Line= 3
2217008.24475796520232.675051379 2217058.6659248 520056.20096746
2217701.53580193519490.223369748
#Sta/Elev= 30
       0 2683.27    57.7 2676.76   107.6 2674.91   190.9 2666.61   203.8 2662.42
   220.8 2651.05   228.2 2648.22   238.8 2647.51   249.5 2650.15   276.1 2646.89
   291.6 2646.68   318.8 2649.36   345.4 2648.53     405 2650.03   425.4 2649.12
   431.82646.144     436 2644.22     479 2644.03     575 2643.84   649.2 2643.66
   659.9 2646.15   668.6 2650.09   708.2 2651.34   931.6 2653.77   946.3 2652.64
     953 2654.95   963.3 2664.67  1000.9 2690.83  1025.7 2701.42    1040 2703.12
#Mann= 5 ,-1,0
       0      .1       0   431.8    .045       0     479      .1       0
     575    .045       0   659.9      .1       0
#XS Ineff= 2 , 0
             404 2654.86  713.92         2654.86
Permanent Ineff=
       F       F
Bank Sta=431.8,659.9
XS Rating Curve= 0 ,0
Exp/Cntr(USF)=0,0
Exp/Cntr=0.3,0.1

Type RM Length L Ch R = 1 ,24421   ,286.1,271.5,262.9
XS GIS Cut Line= 4
2217336.40597702520521.0025111612217357.41479653520294.107260408
2217491.87124142520165.2531673882217977.87526618519785.693828165
#Sta/Elev= 30
       0 2692.66    60.1 2691.12   120.3 2686.33   172.7 2672.76   230.5 2665.35
   240.8 2659.22   252.3 2648.84   261.6 2644.85   292.8  2642.9   343.6 2646.31
   391.1 2645.26   420.7 2647.88   434.8 2647.69     450 2644.72   490.6 2645.32
   499.9 2642.05   505.6 2640.42   632.7 2640.82   635.2 2642.25   642.9 2647.24
   667.7 2647.19   708.9 2644.55   719.7 2646.18   770.6 2647.86   901.6 2650.62
   915.9 2648.82   961.5 2651.18   977.8 2658.39  1005.6 2664.83  1030.8 2673.43
#Mann= 5 ,-1,0
       0      .1       0  237.87     .08       0  247.87      .1       0
   499.9    .045       0   635.2      .1       0
#XS Ineff= 2 , 0
                          857.92         2652.89
Permanent Ineff=
       F       F
Bank Sta=499.9,635.2
XS Rating Curve= 0 ,0
Exp/Cntr(USF)=0,0
Exp/Cntr=0.3,0.1

Type RM Length L Ch R = 1 ,24149   ,194.6,218.1,238.8
XS GIS Cut Line= 3
2217666.88643798520479.6221484072217886.41520781519985.021185045
2218029.24115445519863.354637908
#Sta/Elev= 30
       0  2687.7    37.7 2687.22    85.8 2684.49    94.6 2685.27   112.1 2684.07
   129.6 2680.76   139.2 2677.01   147.1 2671.13   155.8 2659.06   164.6 2649.93
  174.54 2636.89   177.7 2635.55   208.9 2635.48   220.1 2636.85   249.7 2639.86
   265.3 2643.07   317.8 2645.09   336.2 2644.36   357.2 2646.46   422.8 2645.79
   440.3 2643.96   466.6 2643.53   488.4 2648.23     506 2646.78   570.6 2649.46
     617 2649.07   670.4 2652.06   698.3 2654.41   712.5 2661.89   728.8 2667.51
#Mann= 3 ,0,0
       0      .1       0  174.54    .045       0   220.1      .1       0
#XS Ineff= 2 , 0
                          493.52         2651.93
Permanent Ineff=
       F       F
Bank Sta=174.54,220.1
XS Rating Curve= 0 ,0
Exp/Cntr(USF)=0,0
Exp/Cntr=0.3,0.1

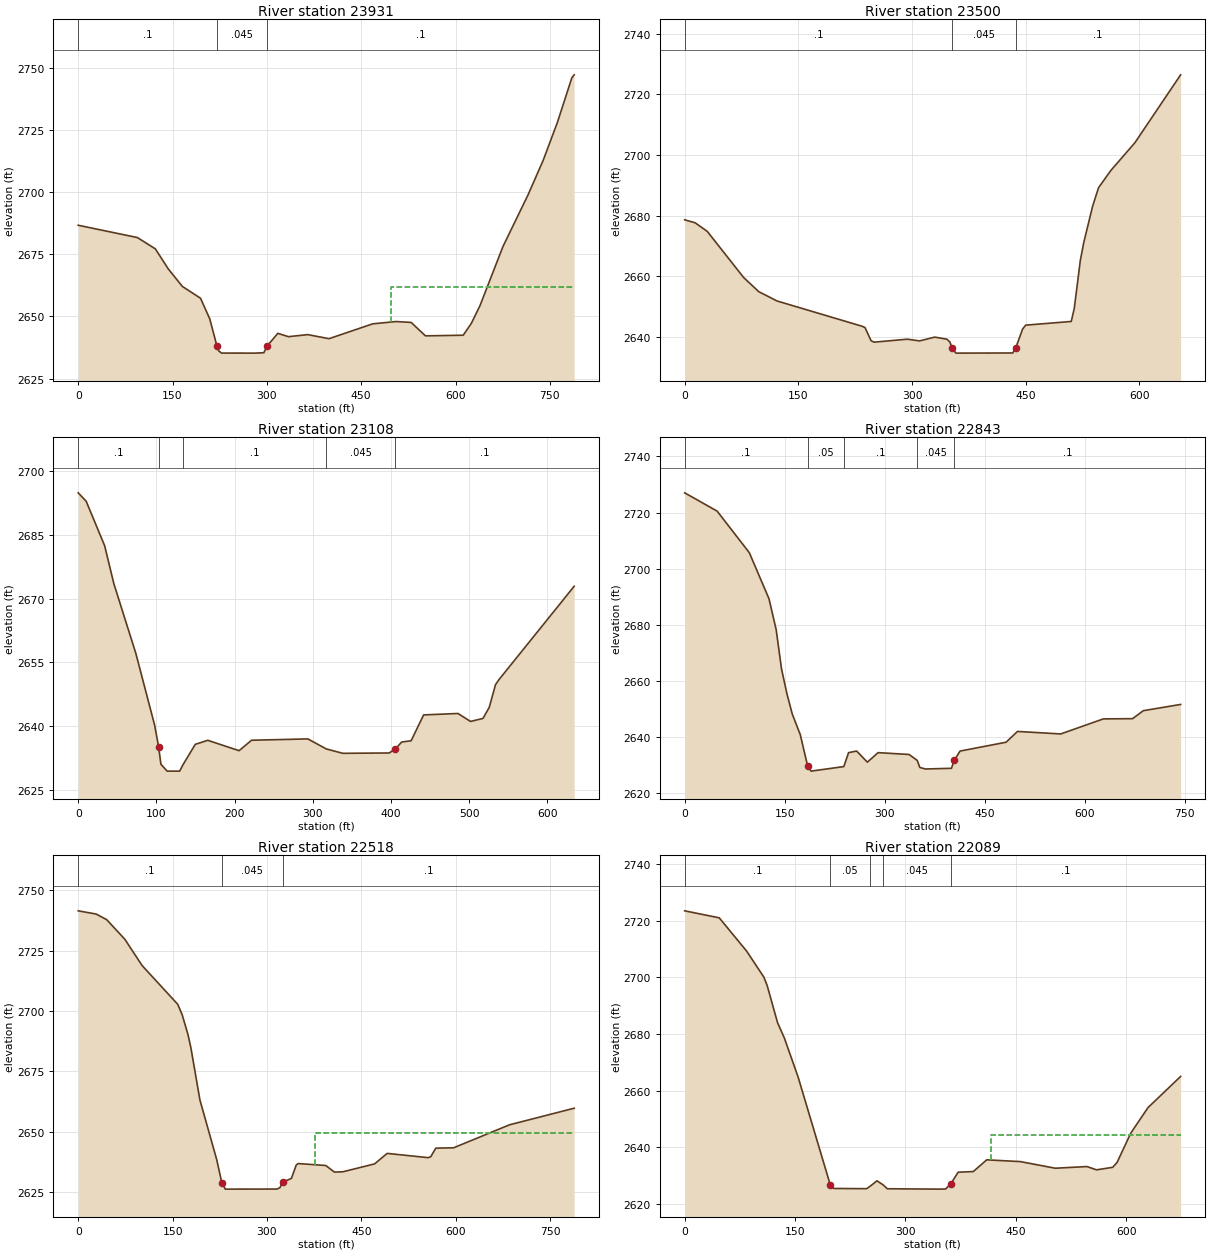
Type RM Length L Ch R = 1 ,23931   ,388,431.4,479.4
XS GIS Cut Line= 4
2217745.37766356520512.5989833562217902.24351593 520410.35606172
2218129.13876669520177.8584590962218371.44048508520044.802602173
#Sta/Elev= 30
       0 2686.78    94.1 2681.82   122.7 2677.25   143.2 2669.17   165.7  2662.1
   194.5 2657.35   209.2 2649.01  220.48 2638.16   223.4 2636.11     228 2635.25
     280 2635.23   295.1 2635.39   300.7 2638.19   317.4 2643.21   334.2 2641.86
   364.8 2642.69   398.8 2641.06   468.3 2647.04     505 2647.96   529.3 2647.61
   552.1 2642.19   612.1 2642.45   625.1 2647.26   638.8 2654.37   675.3  2678.2
   715.2 2699.03   739.2 2712.92     762 2728.33   784.8  2746.2   788.5 2747.42
#Mann= 3 ,-1,0
       0      .1       0  220.48    .045       0   300.7      .1       0
#XS Ineff= 2 , 0
                          497.58         2661.86
Permanent Ineff=
       F       F
Bank Sta=220.48,300.7
XS Rating Curve= 0 ,0
Exp/Cntr(USF)=0,0
Exp/Cntr=0.3,0.1

Type RM Length L Ch R = 1 ,23500   ,480.1,391.6,393.7
XS GIS Cut Line= 2
2217738.37472372520731.090706303 2218392.4493046520747.897761914
#Sta/Elev= 30
       0 2678.64    13.8 2677.66    29.8 2674.83    77.8  2659.6    97.8 2654.93
   121.8 2651.87     234 2643.53   237.9 2643.09   245.9 2638.76   249.9 2638.28
   293.9 2639.26   309.9 2638.69   329.9 2639.94   345.9 2639.26   349.9 2638.34
   352.9 2636.25   357.9 2634.66   432.9 2634.71   436.8 2636.43   445.9 2642.64
   449.9 2643.89     510 2645.11     514 2649.42     522 2665.27   526.5 2671.13
   538.2 2683.12     546 2689.21   562.3 2694.94     594 2704.07   654.3 2726.47
#Mann= 3 ,-1,0
       0      .1       0   352.9    .045       0   436.8      .1       0
Bank Sta=352.9,436.8
XS Rating Curve= 0 ,0
Exp/Cntr(USF)=0,0
Exp/Cntr=0.3,0.1

Type RM Length L Ch R = 1 ,23108   ,253.5,264.8,280.7
XS GIS Cut Line= 2
2217710.36296437521124.655925202 2218344.8293137521134.460040975
#Sta/Elev= 30
       0 2694.81    10.2 2692.83    33.8 2682.41    45.6 2673.49    73.8 2657.09
    97.8 2640.27     103 2635.06   105.8 2631.12   113.8  2629.5   129.8  2629.5
   133.8 2630.92   149.8 2635.79   165.8 2636.73   205.8  2634.3   221.8 2636.75
   293.8 2637.06   317.5  2634.7   338.6 2633.68   397.9 2633.76   405.9 2634.74
   413.9 2636.33   425.9 2636.62   441.9 2642.69   485.9 2643.03   501.9 2641.16
   517.9 2641.87   525.9 2644.48   533.9 2649.79   537.9 2650.88   634.5 2672.88
#Mann= 5 ,-1,0
       0      .1       0     103     .05       0   133.8      .1       0
   317.5    .045       0   405.9      .1       0
Bank Sta=103,405.9
XS Rating Curve= 0 ,0
Exp/Cntr(USF)=0,0
Exp/Cntr=0.3,0.1

Type RM Length L Ch R = 1 ,22843   ,352.7,325,261.8
XS GIS Cut Line= 4
2217655.74003363521396.3699909192217972.27291431521361.355291728
 2218150.1475862521432.7852780772218384.04577679521427.182926206
#Sta/Elev= 30
       0 2727.03    48.7 2720.51      97 2705.69   126.5 2689.29   137.3 2678.23
   145.3 2664.27   153.4 2655.42   161.4  2648.2   173.5  2640.8   184.5 2629.62
   189.6 2627.83   238.8 2629.45   245.9 2634.42     258 2634.99   274.1 2631.02
   290.2 2634.42   336.7 2633.77     349 2631.63   352.8 2629.13   361.3 2628.59
   400.3 2628.84   404.4 2631.67   413.2 2634.98   482.2 2638.13   499.4 2641.98
   564.2 2641.08   628.2 2646.45     672 2646.53   688.2 2649.38   744.1  2651.6
#Mann= 5 ,-1,0
       0      .1       0   184.5     .05       0   238.8      .1       0
     349    .045       0   404.4      .1       0
Bank Sta=184.5,404.4
XS Rating Curve= 0 ,0
Exp/Cntr(USF)=0,0
Exp/Cntr=0.3,0.1

Type RM Length L Ch R = 1 ,22518   ,431.3,429.6,425.2
XS GIS Cut Line= 3
2217727.17001998521810.9440293322218173.95758165   521565.841135
2218449.87341127521526.624671907
#Sta/Elev= 30
       0 2741.45    28.5 2740.12    45.3 2737.79    74.1 2729.69   101.5 2718.82
   158.2 2702.76   165.4 2698.32   174.5 2690.22   179.1 2684.77   193.5 2663.12
   220.1 2638.52   228.2 2628.97   233.8 2626.25   315.9 2626.28   320.5 2626.81
   325.1 2629.15   338.8 2630.67   346.7  2636.3   349.7 2636.83   393.5 2636.03
   407.2 2633.31   420.9 2633.44   471.1  2636.7   491.1 2641.04   556.3 2639.28
   560.3 2639.64   568.4 2643.21   596.7 2643.36   685.5 2652.87   788.3 2659.74
#Mann= 3 ,-1,0
       0      .1       0   228.2    .045       0   325.1      .1       0
#XS Ineff= 2 , 0
                          376.79         2649.55
Permanent Ineff=
       F       F
Bank Sta=228.2,325.1
XS Rating Curve= 0 ,0
Exp/Cntr(USF)=0,0
Exp/Cntr=0.3,0.1

Type RM Length L Ch R = 1 ,22089   ,254.2,255.3,313.8
XS GIS Cut Line= 2
2217935.85762715522194.7051324572218514.30045778521848.759904457
#Sta/Elev= 30
       0 2723.43      47 2720.96    84.3  2709.2   107.6 2700.06   112.1 2697.11
   126.2 2684.02   135.5 2678.57   154.2  2664.8   197.8 2626.89   202.6 2625.54
   247.4 2625.47   252.2 2626.37   261.4 2628.24   269.7 2626.81   275.4 2625.44
   345.3 2625.31   354.6 2625.35   361.5 2627.12   371.7 2631.28   392.2  2631.5
   410.5 2635.64   456.3 2635.01   503.7 2632.68   546.7 2633.27   559.7 2632.11
   581.7    2633   587.6 2634.71   606.3 2645.06   629.6 2654.03     674 2665.04
#Mann= 5 ,-1,0
       0      .1       0   197.8     .05       0   252.2      .1       0
   269.7    .045       0   361.5      .1       0
#XS Ineff= 2 , 0
                          416.45         2644.42
Permanent Ineff=
       F       F
Bank Sta=197.8,361.5
XS Rating Curve= 0 ,0
Exp/Cntr(USF)=0,0
Exp/Cntr=0.3,0.1