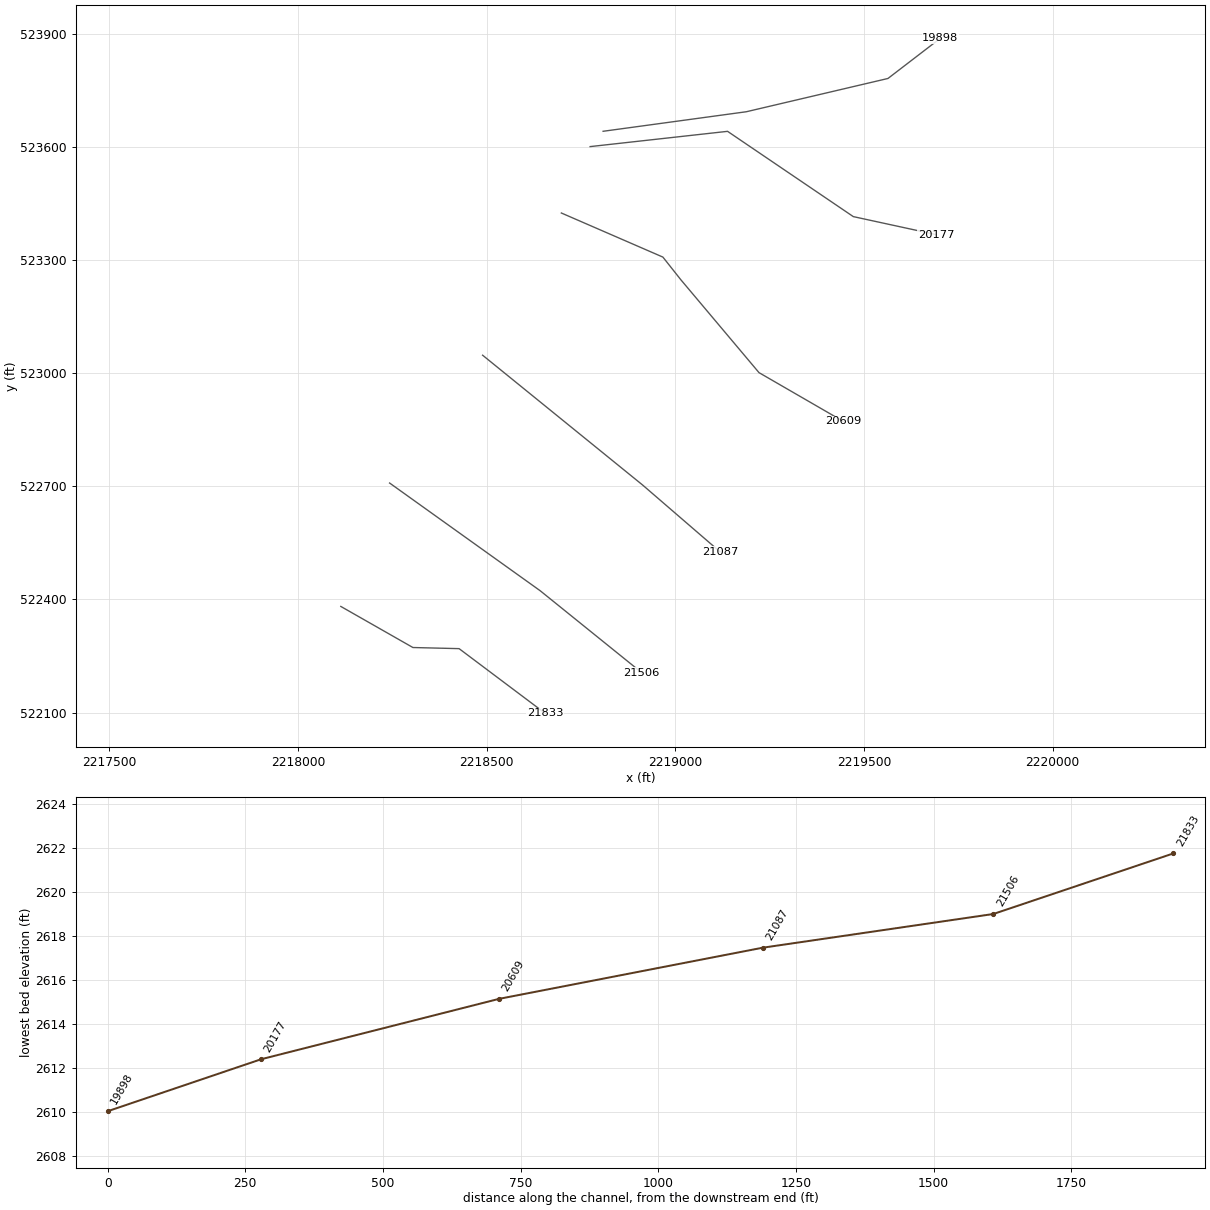
HEC-RAS study OLDFLDFK1.prj: OLDFLDFK1

--- OLDFLDFK1.g01 (geometry) --- (continued)

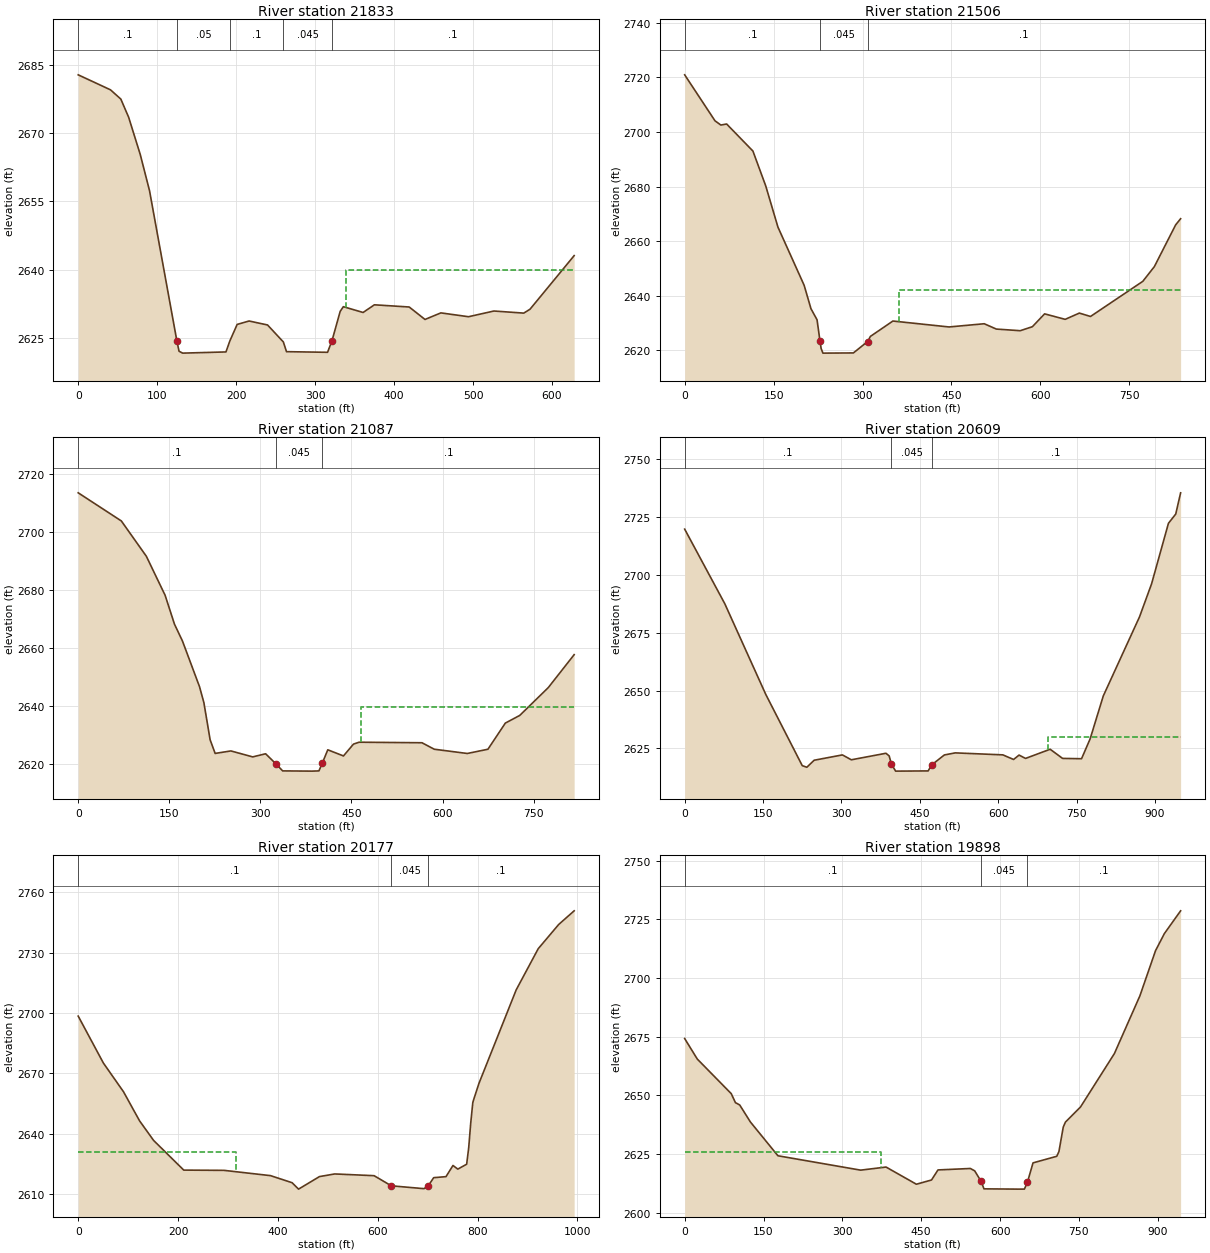
Type RM Length L Ch R = 1 ,21833   ,332.8,327.2,264.8
XS GIS Cut Line= 4
2218113.28554894522381.4432292942218304.36485322522272.468313574
2218426.77503252522269.4826994452218655.17451341 522097.80988701
#Sta/Elev= 30
       0 2682.75    40.9 2679.46      54 2677.43    63.9 2673.44    78.6 2665.27
    90.3 2657.37   124.9 2624.48   127.7 2622.16   132.3 2621.75   187.1 2622.01
   192.1 2624.44   201.3 2628.04   216.4 2628.79   239.8 2627.92   259.8  2624.2
   263.8 2622.07   315.8 2621.93  321.46  2624.5   331.8 2630.91   335.8 2631.93
   360.8 2630.66   375.1 2632.34   419.2 2631.86   439.2 2629.13   459.3 2630.57
   494.3 2629.73   526.5 2630.98   564.3 2630.52   572.2 2631.37   628.1 2643.12
#Mann= 5 ,-1,0
       0      .1       0   124.9     .05       0   192.1      .1       0
   259.8    .045       0  321.46      .1       0
#XS Ineff= 2 , 0
                           339.4            2640
Permanent Ineff=
       F       F
Bank Sta=124.9,321.46
XS Rating Curve= 0 ,0
Exp/Cntr(USF)=0,0
Exp/Cntr=0.3,0.1

Type RM Length L Ch R = 1 ,21506   ,417.6,419,409.1
XS GIS Cut Line= 3
2218242.58639206522708.7209165712218641.75396283522423.000971178
2218910.66685261522205.909836198
#Sta/Elev= 30
       0  2720.9    51.1 2704.08      61 2702.51    70.8 2702.89   115.1 2692.99
   136.7 2680.24   157.3 2665.15   201.5 2643.84     213 2635.27   223.3  2631.2
   228.2 2623.44   230.2 2620.66   233.2    2619   284.6 2619.07   308.5 2623.24
   313.3 2625.13   351.2 2630.75   445.9 2628.58   505.3 2629.76   525.6 2627.81
     566 2627.21   586.5 2628.68   607.1 2633.38   641.8 2631.37   665.7 2633.66
   684.5 2632.42   772.7 2645.28   792.2 2650.67   828.1 2665.95   836.5 2668.21
#Mann= 3 ,-1,0
       0      .1       0   228.2    .045       0   308.5      .1       0
#XS Ineff= 2 , 0
                          361.69         2642.04
Permanent Ineff=
       F       F
Bank Sta=228.2,308.5
XS Rating Curve= 0 ,0
Exp/Cntr(USF)=0,0
Exp/Cntr=0.3,0.1

Type RM Length L Ch R = 1 ,21087   ,486.8,478.6,466.6
XS GIS Cut Line= 3
2218489.08987436523047.6632047332218913.46802855  522703.1185647
2219117.95387182522526.644480781
#Sta/Elev= 30
       0 2713.51      71 2703.81   112.2 2691.62   143.1 2678.16   158.5  2668.2
   171.7 2662.36   199.8 2646.59     207 2641.07   217.2 2628.31   225.5 2623.58
   251.4 2624.44   287.4 2622.38   308.6 2623.46   325.3 2620.04   336.7 2617.55
   385.2 2617.47   396.4 2617.55   402.1 2620.29     411 2624.83   436.8 2622.71
   453.3 2626.79   462.5 2627.45   566.1 2627.26   586.3 2625.03   640.7 2623.56
   674.7 2625.02   703.4 2634.05   727.1 2636.69     774 2646.27   816.7 2657.66
#Mann= 3 ,-1,0
       0      .1       0   325.3    .045       0   402.1      .1       0
#XS Ineff= 2 , 0
                          466.48         2639.65
Permanent Ineff=
       F       F
Bank Sta=325.3,402.1
XS Rating Curve= 0 ,0
Exp/Cntr(USF)=0,0
Exp/Cntr=0.3,0.1

Type RM Length L Ch R = 1 ,20609   ,415.5,432.1,444
XS GIS Cut Line= 5
2218697.77748154523424.8037693522218966.89569141523307.852891336
2219014.31036222523247.9472841012219221.59738142523001.443801802
2219444.29086827522872.589708782
#Sta/Elev= 30
       0 2719.76    76.8 2687.51   155.3 2648.28     225 2617.53   233.8 2616.82
   247.8 2619.86   301.9 2622.16     319 2620.05   385.2 2622.87   391.4 2621.72
   395.8 2618.13   403.8 2615.15     466 2615.24   472.7 2617.83     497 2622.14
   517.9 2623.04   608.9 2622.18   629.5 2620.19     640 2622.09   652.4 2620.64
   699.5 2624.61   723.3 2620.65   759.6 2620.51     776 2629.09   801.2 2647.65
   870.5 2681.82   893.6  2696.1   925.9 2722.28   939.9 2726.31   949.2 2735.46
#Mann= 3 ,-1,0
       0      .1       0   395.8    .045       0   472.7      .1       0
#XS Ineff= 2 , 0
                          694.49          2629.9
Permanent Ineff=
       F       F
Bank Sta=395.8,472.7
XS Rating Curve= 0 ,0
Exp/Cntr(USF)=0,0
Exp/Cntr=0.3,0.1

Type RM Length L Ch R = 1 ,20177   ,231.6,278.9,321.5
XS GIS Cut Line= 4
2218774.05201693 523600.898067462219138.25818086523641.365419007
2219471.51872301523415.2243368292219690.51850786523367.615687949
#Sta/Elev= 30
       0 2698.48    50.4 2675.15    90.7 2660.86   122.9 2646.38     151 2636.64
   211.4 2621.87   291.9 2621.75   385.2 2619.12   428.4  2615.6   441.3 2612.41
   483.2 2618.65   513.8 2619.96   592.6  2619.1   627.1 2614.06   692.6 2612.64
  700.91 2614.03     712 2618.11   736.6 2618.62   750.6 2624.17   760.3 2622.37
     778  2624.8   782.1 2632.99   786.2  2645.4   790.3 2655.41   791.6 2656.61
   802.6    2665   877.2 2711.53   921.3 2732.01   962.3 2744.06   993.3 2750.87
#Mann= 3 ,-1,0
       0      .1       0   627.1    .045       0  700.91      .1       0
#XS Ineff= 2 , 0
          316.62 2630.95
Permanent Ineff=
       F       F
Bank Sta=627.1,700.91
XS Rating Curve= 0 ,0
Exp/Cntr(USF)=0,0
Exp/Cntr=0.3,0.1

Type RM Length L Ch R = 1 ,19898   ,299.4,306.5,314.3
XS GIS Cut Line= 4
2218808.42393098   523641.512503 2219187.9832702523693.334257802
2219563.34084552523781.5712997622219701.99905431  523888.0159853
#Sta/Elev= 30
       0 2674.24      24  2665.5    88.6 2650.75    96.6 2646.91   104.7 2645.93
   124.9 2638.72   177.4 2624.27   334.8 2618.14   383.1 2619.46   440.8 2612.14
   469.6 2613.94   481.9 2618.23   543.5 2618.85   551.7 2617.85   564.1 2613.31
   569.4 2610.17   633.9 2610.05   646.3 2610.06   652.1 2613.01   662.7 2621.24
   707.9 2624.05     712 2626.06   720.2 2636.48   724.3 2638.61   753.1 2645.09
   817.5 2667.83     866 2692.43   895.8 2711.72   912.5 2718.95   943.5 2728.69
#Mann= 3 ,-1,0
       0      .1       0   564.1    .045       0   652.1      .1       0
#XS Ineff= 2 , 0
          374.08 2626.03
Permanent Ineff=
       F       F
Bank Sta=564.1,652.1
XS Rating Curve= 0 ,0
Exp/Cntr(USF)=0,0
Exp/Cntr=0.3,0.1