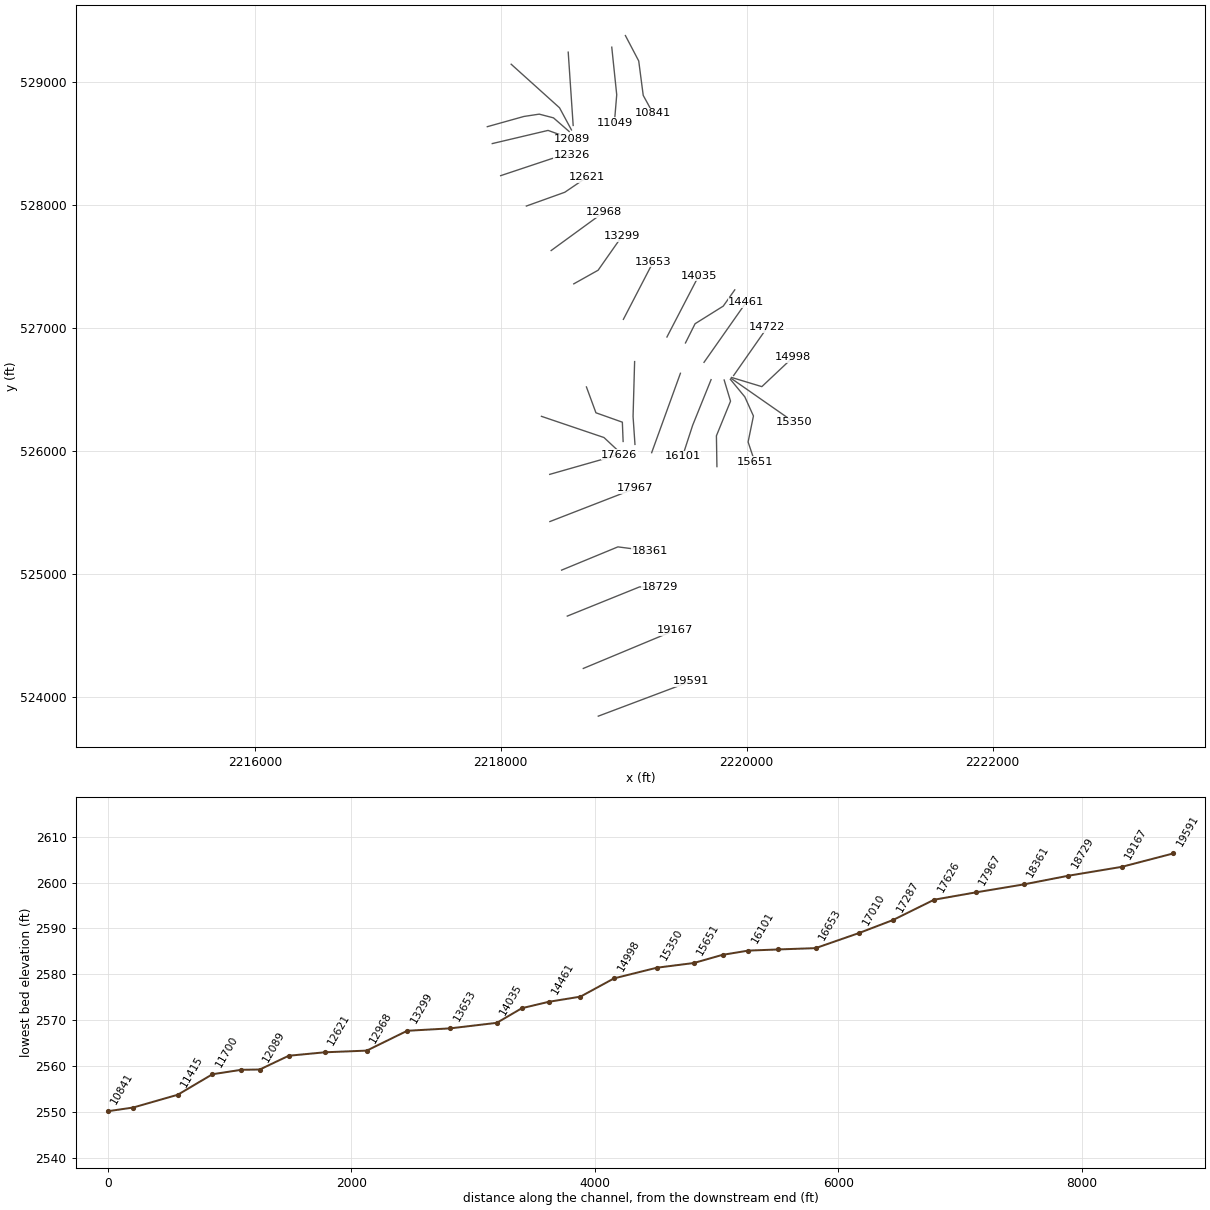
HEC-RAS study OLDFLDFK1.prj: OLDFLDFK1

--- OLDFLDFK1.g01 (geometry) --- (continued)

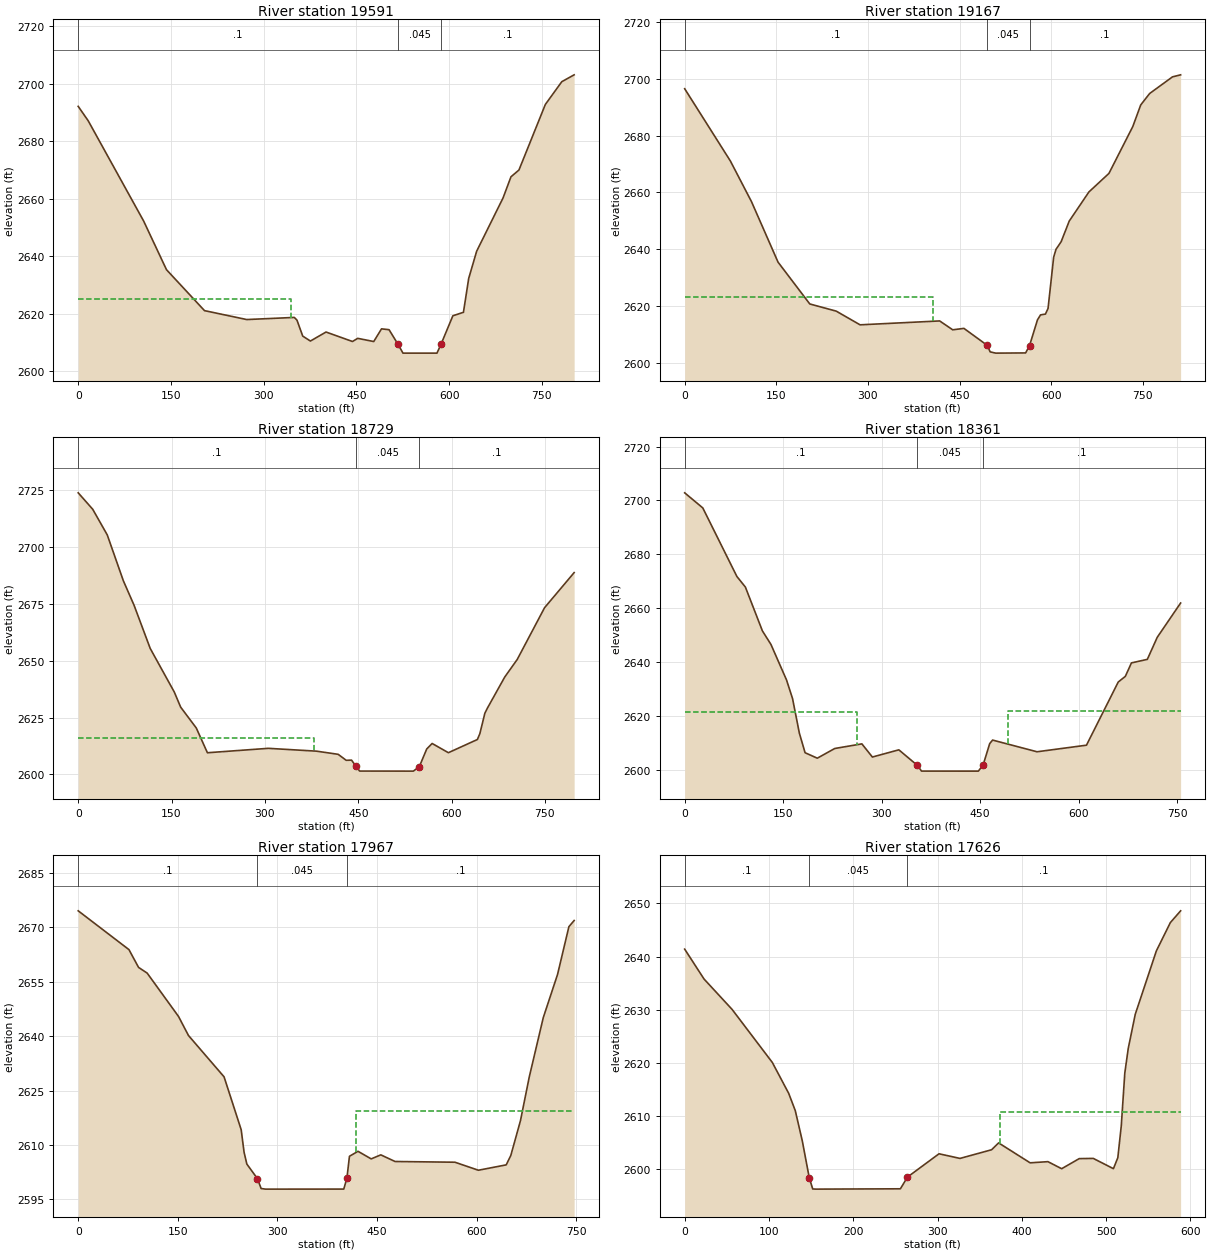
Type RM Length L Ch R = 1 ,19591   ,422.6,424.2,426
XS GIS Cut Line= 2
2218793.01746333523840.3959944012219543.73261397524123.314763859
#Sta/Elev= 30
       0 2692.11    16.2 2687.09     106 2652.19   142.8 2635.34   204.3 2621.11
   272.7 2618.01   349.6 2618.75   353.9 2617.81   363.2 2612.26   375.6 2610.54
   400.9 2613.67   443.7 2610.38   452.2 2611.48   478.1 2610.37   490.7 2614.78
   502.9 2614.48   517.2 2609.45   525.4 2606.34   580.4 2606.34   587.2 2609.56
   606.1 2619.32   623.2 2620.53   631.7  2632.3   644.6 2641.77   687.3 2660.29
   700.1 2667.63     713 2669.98   755.7 2692.77   782.3 2700.68   802.3 2703.07
#Mann= 3 ,0,0
       0      .1       0   517.2    .045       0   587.2      .1       0
#XS Ineff= 2 , 0
          344.23 2625.03
Permanent Ineff=
       F       F
Bank Sta=517.2,587.2
XS Rating Curve= 0 ,0
Exp/Cntr(USF)=0,0
Exp/Cntr=0.3,0.1

Type RM Length L Ch R = 1 ,19167   ,438.4,437.9,438
XS GIS Cut Line= 2
2218671.16631015 524228.358861432219420.48087282524540.689978207
#Sta/Elev= 30
       0 2696.55    74.8  2671.1   109.4 2656.76   152.8 2635.47   204.8 2620.73
   248.1  2618.2   287.1 2613.38   417.4 2614.75   438.8 2611.62   457.1 2612.13
   495.1 2606.18     500 2603.86   509.1 2603.41   558.1 2603.48   564.5 2606.07
   577.5 2615.13   582.5 2616.88   590.5 2617.16   594.8 2619.15     604 2637.22
   607.8 2639.97   616.2 2642.64   629.5 2649.94   661.7 2660.19   694.5 2666.73
   733.5 2683.22   746.5 2690.84   761.1 2694.87   798.5 2700.73   811.8 2701.45
#Mann= 3 ,-1,0
       0      .1       0   495.1    .045       0   564.5      .1       0
#XS Ineff= 2 , 0
           406.2 2623.07
Permanent Ineff=
       F       F
Bank Sta=495.1,564.5
XS Rating Curve= 0 ,0
Exp/Cntr(USF)=0,0
Exp/Cntr=0.3,0.1

Type RM Length L Ch R = 1 ,18729   ,366.8,367.5,367.8
XS GIS Cut Line= 3
2218540.91162916524654.1376035842219128.62952465524891.551464257
 2219291.6267798 524890.83697011
#Sta/Elev= 30
       0 2723.83    23.3 2716.61    46.7 2705.32    72.5 2685.19    89.8 2674.37
   115.7 2655.42   154.5 2636.19   164.6 2629.62   189.7 2620.46   207.6 2609.56
   305.5  2611.5   382.8 2610.26   417.7 2608.87   430.6 2606.24   439.2 2606.31
   446.5 2603.57   452.2 2601.51   538.5 2601.48  548.12 2603.44     560 2611.21
   568.7 2613.64   594.8 2609.58   641.4 2615.38   645.4 2617.98   653.4 2626.91
   657.4 2629.12   685.4 2642.86   705.4 2650.56   749.4 2673.34   796.9 2688.76
#Mann= 3 ,-1,0
       0      .1       0   446.5    .045       0  548.12      .1       0
#XS Ineff= 2 , 0
          379.04 2615.83
Permanent Ineff=
       F       F
Bank Sta=446.5,548.12
XS Rating Curve= 0 ,0
Exp/Cntr(USF)=0,0
Exp/Cntr=0.3,0.1

Type RM Length L Ch R = 1 ,18361   ,396.7,395,392.9
XS GIS Cut Line= 3
2218494.69222623525028.0945909362218952.68449164525217.173966564
2219210.39267768525183.559855341
#Sta/Elev= 30
       0 2702.82    27.6 2697.22    79.5  2671.8    92.5 2667.85   118.4  2651.6
   131.4 2646.58   155.1 2633.42   164.3  2626.5   174.7 2613.65   183.4 2606.41
     202 2604.38   228.6 2607.98   269.9 2609.69   285.9 2604.81   326.2 2607.48
   354.2 2601.76   360.8 2599.59     417 2599.58   447.3 2599.58  454.522601.817
   464.6 2609.78     469  2611.1   536.7 2606.76     612  2609.2   660.4 2632.64
   671.2 2634.73   680.5 2639.73   704.7 2641.04   719.8 2649.22   755.4 2661.94
#Mann= 3 ,-1,0
       0      .1       0   354.2    .045       0  454.52      .1       0
#XS Ineff= 2 , 0
          262.76 2621.33  493.07         2622.04
Permanent Ineff=
       F       F
Bank Sta=354.2,454.52
XS Rating Curve= 0 ,0
Exp/Cntr(USF)=0,0
Exp/Cntr=0.3,0.1

Type RM Length L Ch R = 1 ,17967   ,346.6,340.4,332.6
XS GIS Cut Line= 2
2218399.45224443525423.0603978032219095.54446434525693.373875552
#Sta/Elev= 30
       0 2674.59    76.4 2663.89    90.9 2658.98   103.8 2657.42     151 2645.47
     166 2640.21   219.6 2628.81   245.4 2614.21   249.7 2608.05   253.9 2604.75
  269.78 2600.75   275.4 2598.01   282.1 2597.84   399.8 2597.85  404.52 2600.81
   408.4  2606.9   421.3 2608.27   441.1 2606.18   455.6 2607.29   477.1 2605.46
   567.2 2605.26   602.5 2603.05   644.4 2604.53   651.3 2607.11   665.9 2616.74
   679.1 2628.76   700.2 2645.13   721.7 2657.04   738.8 2670.22   746.7 2671.92
#Mann= 3 ,0,0
       0      .1       0  269.78    .045       0  404.52      .1       0
#XS Ineff= 2 , 0
                          418.25         2619.32
Permanent Ineff=
       F       F
Bank Sta=269.78,404.52
XS Rating Curve= 0 ,0
Exp/Cntr(USF)=0,0
Exp/Cntr=0.3,0.1

Type RM Length L Ch R = 1 ,17626   ,372.9,338.9,301.1
XS GIS Cut Line= 3
2218398.05165647525806.8215009282218756.60217618525909.064422564
2218963.88919538525967.889117204
#Sta/Elev= 30
       0 2641.41      23 2635.78    56.3 2630.06     104 2620.08   123.4 2614.27
   131.2 2611.02   139.5 2605.35   147.8 2598.38   151.9 2596.28   155.7 2596.25
   255.9 2596.31   264.3 2598.52   301.7  2602.9   326.6 2602.03   364.1 2603.66
   372.4 2604.95   409.8  2601.2   430.9 2601.42   447.2 2600.09     468 2601.99
   484.7 2602.03   508.6  2600.1   513.8 2602.16   517.9 2608.14   522.1  2618.1
   526.2 2622.75   534.5 2629.15   559.5 2641.07   576.1  2646.4   588.3 2648.62
#Mann= 3 ,-1,0
       0      .1       0   147.8    .045       0   264.3      .1       0
#XS Ineff= 2 , 0
                          373.86          2610.8
Permanent Ineff=
       F       F
Bank Sta=147.8,264.3
XS Rating Curve= 0 ,0
Exp/Cntr(USF)=0,0
Exp/Cntr=0.3,0.1

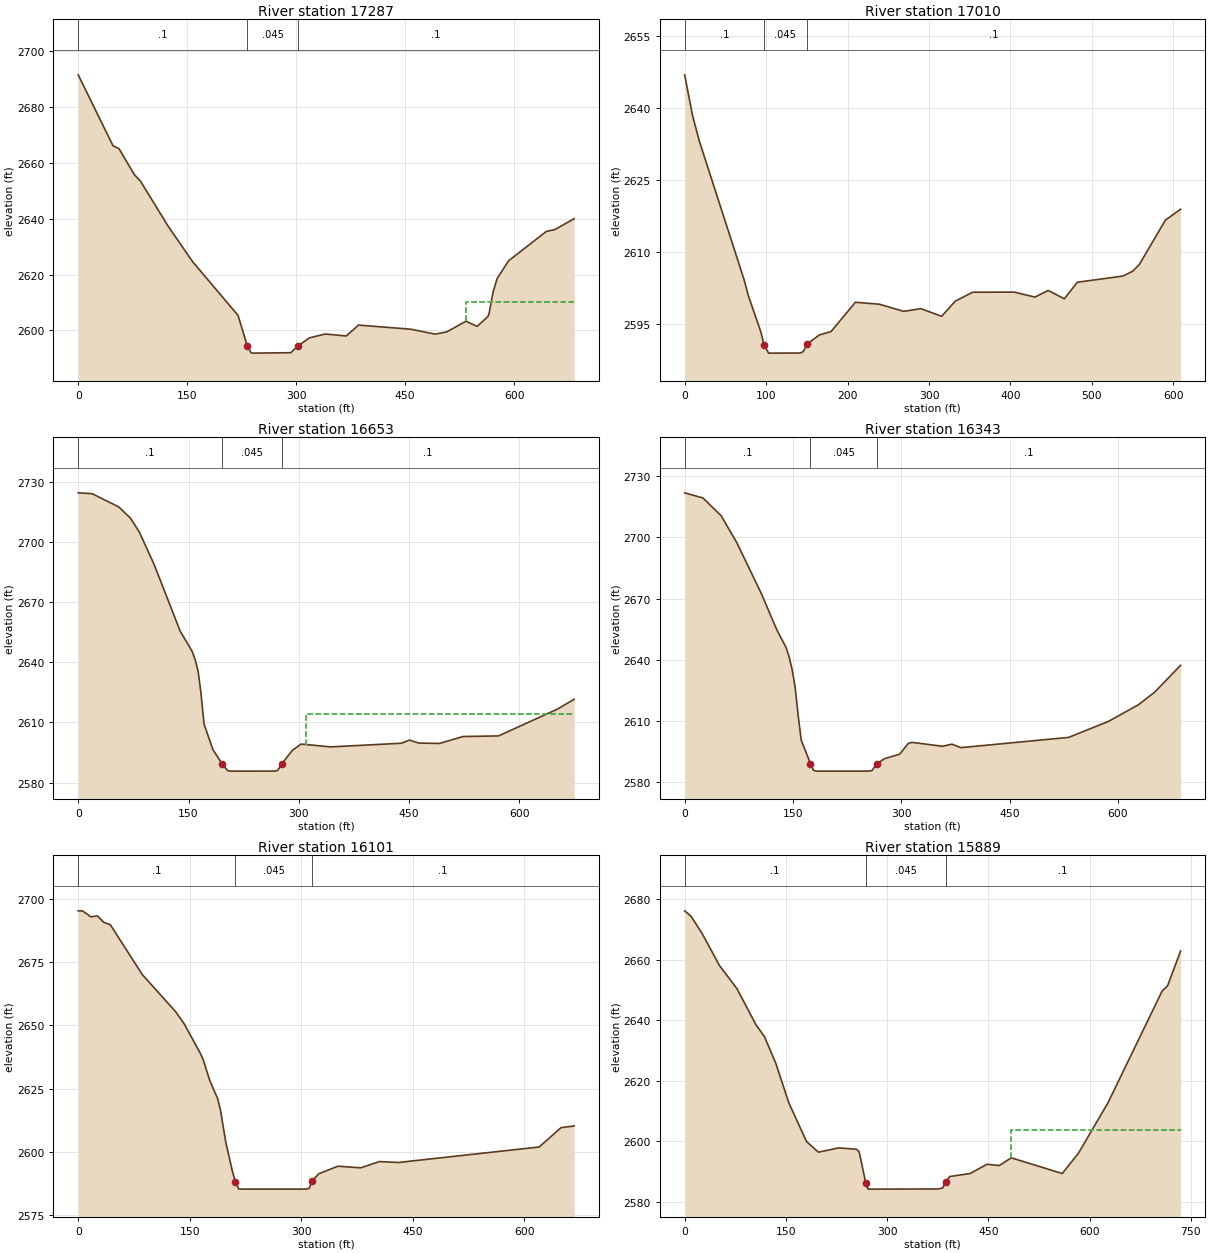
Type RM Length L Ch R = 1 ,17287   ,307.1,276.9,228.1
XS GIS Cut Line= 3
2218330.82343402526278.8196460132218839.23686626526106.547325997
 2218945.6815518526007.105580297
#Sta/Elev= 30
       0 2691.63    47.9 2666.18      56 2665.19    77.4 2655.79    85.9 2653.41
   123.9 2637.28   157.7 2624.52     220 2605.33   232.6 2594.45   237.9 2591.92
   242.1 2591.81   292.6 2591.97     302 2594.32   318.2 2597.28   339.9 2598.66
   368.9 2597.96   385.8 2601.87   457.6 2600.39   491.2 2598.63   507.1 2599.42
   533.6 2603.25     549 2601.41   563.9 2604.96   565.5 2606.15   570.9 2613.67
   576.4  2618.5   592.2 2624.91   644.3 2635.48     656 2636.11   682.5 2640.04
#Mann= 3 ,-1,0
       0      .1       0   232.6    .045       0     302      .1       0
#XS Ineff= 2 , 0
                           533.6            2610
Permanent Ineff=
       F       F
Bank Sta=232.6,302
XS Rating Curve= 0 ,0
Exp/Cntr(USF)=0,0
Exp/Cntr=0.3,0.1

Type RM Length L Ch R = 1 ,17010   ,376.8,357.4,337.5
XS GIS Cut Line= 4
2218696.63899571526517.8887373182218773.96423607526307.700467677
2218988.77064324526231.3050478632218995.07546594526074.456194501
#Sta/Elev= 30
       0 2646.89     9.5 2638.53    17.8 2633.21    73.2 2604.13    78.1 2600.98
    93.7 2593.34   97.38 2590.79     103    2589   141.4 2589.02   145.7 2589.31
   149.9 2590.83   165.3 2592.78   179.8  2593.5   209.6 2599.58     239 2599.18
   268.8 2597.69     290 2598.25   315.5 2596.66   332.4 2599.84   353.7 2601.67
   404.6 2601.69   430.1 2600.66   446.4 2602.04   466.1  2600.3   482.1 2603.75
   538.2 2605.03   550.2 2606.06   558.2 2607.44   590.2 2616.66   608.9 2618.94
#Mann= 3 ,-1,0
       0      .1       0   97.38    .045       0   149.9      .1       0
Bank Sta=97.38,149.9
XS Rating Curve= 0 ,0
Exp/Cntr(USF)=0,0
Exp/Cntr=0.3,0.1

Type RM Length L Ch R = 1 ,16653   ,330.7,309.7,293.8
XS GIS Cut Line= 3
 2219088.5415245526724.2066197142219075.93623279526277.419058046
2219091.34270043526050.523807293
#Sta/Elev= 30
       0 2724.45    18.9 2724.03      55 2717.45    71.1 2711.82    83.1 2704.89
   103.1 2688.84   138.6 2655.56   155.1 2645.31   159.1 2641.18   163.1 2635.44
   166.8 2624.93   171.1 2609.21   183.1 2596.49  195.45 2589.47   203.1 2585.95
   207.1  2585.7   267.1 2585.71   271.1    2586   277.1 2589.44   291.1 2596.02
   303.1  2599.2   343.2 2597.79   439.2 2599.59   450.5 2601.16   463.2 2599.68
   491.3  2599.5   523.4 2602.96   571.5 2603.25   651.7 2616.62   674.4 2621.55
#Mann= 3 ,0,0
       0      .1       0  195.45    .045       0   277.1      .1       0
#XS Ineff= 2 , 0
                          310.37         2614.17
Permanent Ineff=
       F       F
Bank Sta=195.45,277.1
XS Rating Curve= 0 ,0
Exp/Cntr(USF)=0,0
Exp/Cntr=0.3,0.1

Type RM Length L Ch R = 1 ,16343   ,245,242.6,240.5
XS GIS Cut Line= 2
2219461.09792388526628.9666379162219227.19973329525983.295584847
#Sta/Elev= 30
       0 2721.82    25.3 2719.31    50.5 2710.58    72.1 2697.46   106.1 2672.46
   127.4 2654.81   140.2 2646.13   144.4 2641.74   148.7 2635.34   152.9  2626.7
   157.2 2612.57   161.4 2600.52   174.2 2589.11   178.5 2585.76   182.7 2585.41
     255 2585.41   259.3  2585.7     266 2588.95   276.3 2591.45   297.6 2593.72
   309.7 2599.02   314.6 2599.51   357.1  2597.6   369.9 2598.61   382.7 2596.93
   531.6 2601.94   586.9  2609.8   628.3 2617.96   650.7 2624.09   686.7 2637.29
#Mann= 3 ,0,0
       0      .1       0   174.2    .045       0     266      .1       0
Bank Sta=174.2,266
XS Rating Curve= 0 ,0
Exp/Cntr(USF)=0,0
Exp/Cntr=0.3,0.1

Type RM Length L Ch R = 1 ,16101   ,213,211.8,211.6
XS GIS Cut Line= 3
2219710.40258212526577.1448831152219560.53966958526205.989071698
 2219477.9049795 525952.48264956
#Sta/Elev= 30
       0 2695.44     5.9 2695.39    17.2 2693.05    25.8 2693.45    34.5 2690.84
    43.1 2689.97    86.2 2670.17   130.8 2655.55   142.3 2650.78   164.6 2638.78
   168.2 2636.38   176.8 2628.28   187.6 2620.92   191.3 2616.51   198.4 2603.79
     207 2592.64   211.3 2588.08   215.7 2585.25   219.6 2585.16   306.2 2585.16
   310.6 2585.46   314.3 2588.29   323.5 2591.25   349.4 2594.25   379.7  2593.6
   405.3 2596.08   430.6 2595.72   619.9 2601.86   649.3 2609.53   666.9 2610.19
#Mann= 3 ,0,0
       0      .1       0   211.3    .045       0   314.3      .1       0
Bank Sta=211.3,314.3
XS Rating Curve= 0 ,0
Exp/Cntr(USF)=0,0
Exp/Cntr=0.3,0.1

Type RM Length L Ch R = 1 ,15889   ,221.1,237.3,250.2
XS GIS Cut Line= 4
2219816.84726766 526574.343707182219868.66902246526402.071387163
2219753.82080912526120.5532056732219758.02257302525869.847959471
#Sta/Elev= 30
       0 2676.11     9.6 2674.28    26.3 2668.45    51.3 2658.14    77.5  2650.4
   105.6 2638.51   118.2 2634.57   134.9 2625.84   154.5 2612.61   180.6 2599.93
   198.1 2596.44   228.4 2597.85   254.6  2597.4   258.6 2596.48   268.2 2586.34
   271.6 2584.24   375.3 2584.29   382.4 2584.65   386.5 2586.53   392.5 2588.39
   422.8 2589.39   447.9 2592.45     466 2592.02   483.9 2594.57   559.3 2589.39
   583.3 2596.08   627.4 2612.87   707.3 2649.64   715.3 2651.31   734.7 2662.86
#Mann= 3 ,-1,0
       0      .1       0   268.2    .045       0   386.5      .1       0
#XS Ineff= 2 , 0
                          483.15         2603.74
Permanent Ineff=
       F       F
Bank Sta=268.2,386.5
XS Rating Curve= 0 ,0
Exp/Cntr(USF)=0,0
Exp/Cntr=0.3,0.1

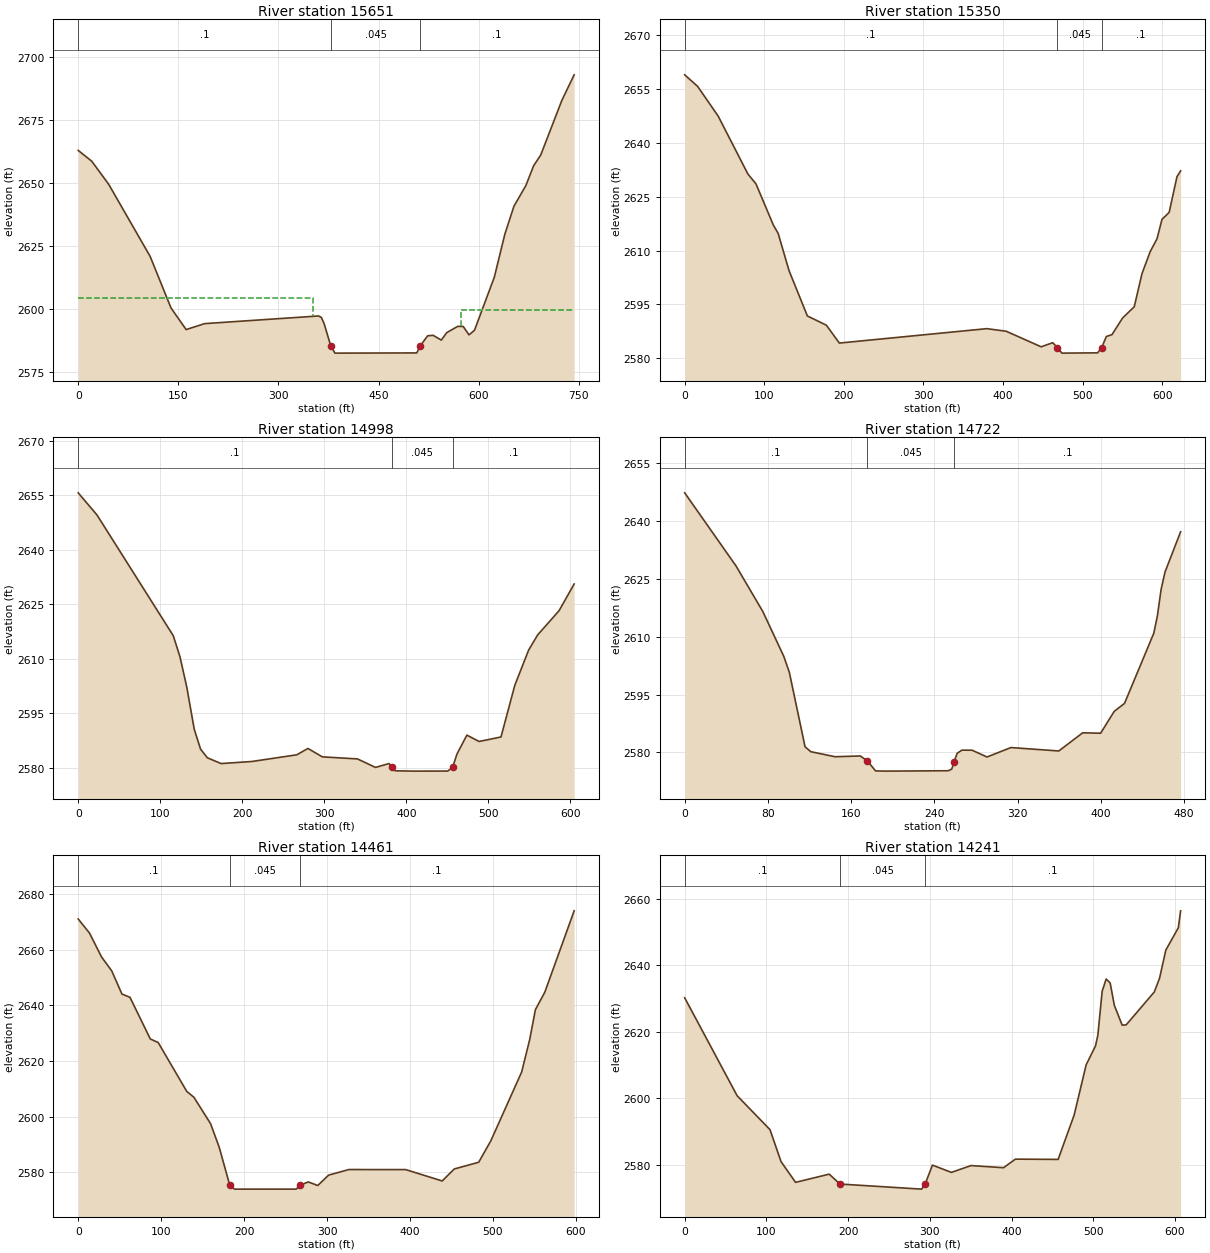
Type RM Length L Ch R = 1 ,15651   ,219.1,301,370.7
XS GIS Cut Line= 5
2219867.26843449 526579.946059052219984.91782377526437.086086354
2220054.94722215526281.6208219492220011.52899516526070.132038839
2220066.15192589525907.663834596
#Sta/Elev= 30
       0 2662.87    20.3 2658.57    45.5 2649.49   107.8 2620.79     139 2600.37
   161.7 2591.79   189.4 2594.15   360.1 2597.19   364.2 2596.61   368.3  2594.2
   378.3 2585.36   384.6 2582.45   507.1 2582.53  512.45 2585.35   523.4 2589.31
   531.6 2589.52   543.9 2587.62     552 2590.56   568.4 2593.06   576.7 2593.03
   585.4 2589.69   593.6 2591.51   623.3 2612.55   639.1 2629.65   652.7 2640.71
   670.6 2648.94   682.2 2656.77   692.8 2661.01   724.5 2682.71   742.9 2692.84
#Mann= 3 ,0,0
       0      .1       0   378.3    .045       0  512.45      .1       0
#XS Ineff= 2 , 0
           351.1 2604.27  572.85         2599.75
Permanent Ineff=
       F       F
Bank Sta=378.3,512.45
XS Rating Curve= 0 ,0
Exp/Cntr(USF)=0,0
Exp/Cntr=0.3,0.1

Type RM Length L Ch R = 1 ,15350   ,284.8,352.8,412.6
XS GIS Cut Line= 2
2219872.77801406526588.419755689  2220384.013405526231.765557637
#Sta/Elev= 30
       0 2658.89    16.3 2655.67    42.1  2647.4    79.5 2631.27    89.6 2628.56
   111.4  2617.1   117.5 2614.75   131.2 2604.38   154.2 2591.79   178.1 2589.21
   194.4 2584.24   379.7 2588.25   404.1 2587.53     448  2583.2   462.6 2584.34
   468.4 2582.98   474.1 2581.44     519 2581.52     524 2582.93     530 2586.08
     537 2586.58   550.4 2591.22     565 2594.34   574.8 2603.59   585.1 2609.71
   593.7 2613.29   599.9 2618.67   608.9  2620.6   618.7 2630.52   623.3 2632.17
#Mann= 3 ,-1,0
       0      .1       0   468.4    .045       0     524      .1       0
Bank Sta=468.4,524
XS Rating Curve= 0 ,0
Exp/Cntr(USF)=0,0
Exp/Cntr=0.3,0.1

Type RM Length L Ch R = 1 ,14998   ,263.5,275.5,284.7
XS GIS Cut Line= 3
2219877.43407409526594.938239727 2220123.2740435526520.441279298
2220376.56370896 526758.83155267
#Sta/Elev= 30
       0 2655.63    22.9 2649.54   115.9 2616.35   124.1 2610.54   132.4 2602.19
   141.5 2590.61   149.2 2585.15   157.5 2582.78   174.2 2581.19   211.8 2581.76
   266.5  2583.6   280.1 2585.34   297.7 2583.03   340.5 2582.47   362.5 2580.13
     379 2581.19   382.5 2580.24   386.4  2579.2   409.7 2579.11   450.6 2579.13
   456.4 2580.11   461.8 2583.79   473.9 2589.01   488.8 2587.26   515.5  2588.5
   532.3 2602.68   549.2 2612.39   560.2 2616.56   586.3 2623.22   604.7 2630.57
#Mann= 3 ,-1,0
       0      .1       0   382.5    .045       0   456.4      .1       0
Bank Sta=382.5,456.4
XS Rating Curve= 0 ,0
Exp/Cntr(USF)=0,0
Exp/Cntr=0.3,0.1

Type RM Length L Ch R = 1 ,14722   ,262.5,261.2,261.9
XS GIS Cut Line= 2
2219893.87960588526610.7589943372220166.99425956527001.523037301
#Sta/Elev= 30
       0 2647.38    49.3 2628.42    75.2 2616.52    95.3 2604.91   100.6 2600.78
   115.7 2581.46   121.2 2580.18   144.5 2578.87   168.9 2579.06   175.7 2577.76
   183.5 2575.18     193 2575.13   253.3 2575.23   256.7 2575.64     259 2577.56
   261.9 2579.76   266.5 2580.58   276.3 2580.56   290.6  2578.8   313.6 2581.25
   359.6 2580.36   382.6 2585.08   399.8 2584.97   412.9 2590.65   422.8 2592.72
   450.9 2610.92   454.4 2615.46   457.9 2622.23   461.7 2626.82   476.7 2637.27
#Mann= 3 ,-1,0
       0      .1       0   175.7    .045       0     259      .1       0
Bank Sta=175.7,259
XS Rating Curve= 0 ,0
Exp/Cntr(USF)=0,0
Exp/Cntr=0.3,0.1

Type RM Length L Ch R = 1 ,14461   ,246.4,220.1,197.7
XS GIS Cut Line= 2
2219652.97186099526718.0890091822219996.56824082527207.453550152
#Sta/Elev= 30
       0 2670.96    13.6 2665.91    28.2  2657.3    40.4 2652.35    52.7 2644.03
    62.4 2642.86    86.9  2627.9    96.4 2626.63   130.9 2609.06   139.5 2606.97
   159.6 2597.48     170 2589.03   182.5 2575.64   188.3    2574   262.8    2574
   267.7 2575.38   277.3 2576.59   288.8  2575.3   301.9 2579.03   326.4 2581.03
   394.8 2581.01   438.8 2576.93   453.4 2581.24   482.8 2583.64   497.4 2591.31
   534.6 2616.03   544.3 2627.66   551.2 2638.43   562.5 2644.66   597.9 2673.89
#Mann= 3 ,0,0
       0      .1       0   182.5    .045       0   267.7      .1       0
Bank Sta=182.5,267.7
XS Rating Curve= 0 ,0
Exp/Cntr(USF)=0,0
Exp/Cntr=0.3,0.1

Type RM Length L Ch R = 1 ,14241   ,172.1,206,235.5
XS GIS Cut Line= 4
2219502.20118884526875.7575129812219580.28892175527032.005698482
2219809.24517314527175.1975250042219903.07875538527307.442203224
#Sta/Elev= 30
       0 2630.22    64.2 2600.73   104.4 2590.52   117.9 2580.91   135.7 2574.65
   176.9 2577.12     190 2574.14     290 2572.61   294.4 2574.23   303.2 2579.84
   326.4 2577.65   350.4  2579.7   390.2 2579.06   404.7 2581.64     457 2581.56
   476.6  2594.9   491.3 2610.03   502.8 2615.76   505.6 2618.93   510.9 2632.19
   515.8 2635.88   520.7 2634.67   525.8 2627.94   535.4 2621.98   540.3 2622.07
   574.7 2631.97   581.1 2636.09   588.8 2644.58   604.1  2651.3   606.9  2656.4
#Mann= 3 ,-1,0
       0      .1       0     190    .045       0   294.4      .1       0
Bank Sta=190,294.4
XS Rating Curve= 0 ,0
Exp/Cntr(USF)=0,0
Exp/Cntr=0.3,0.1

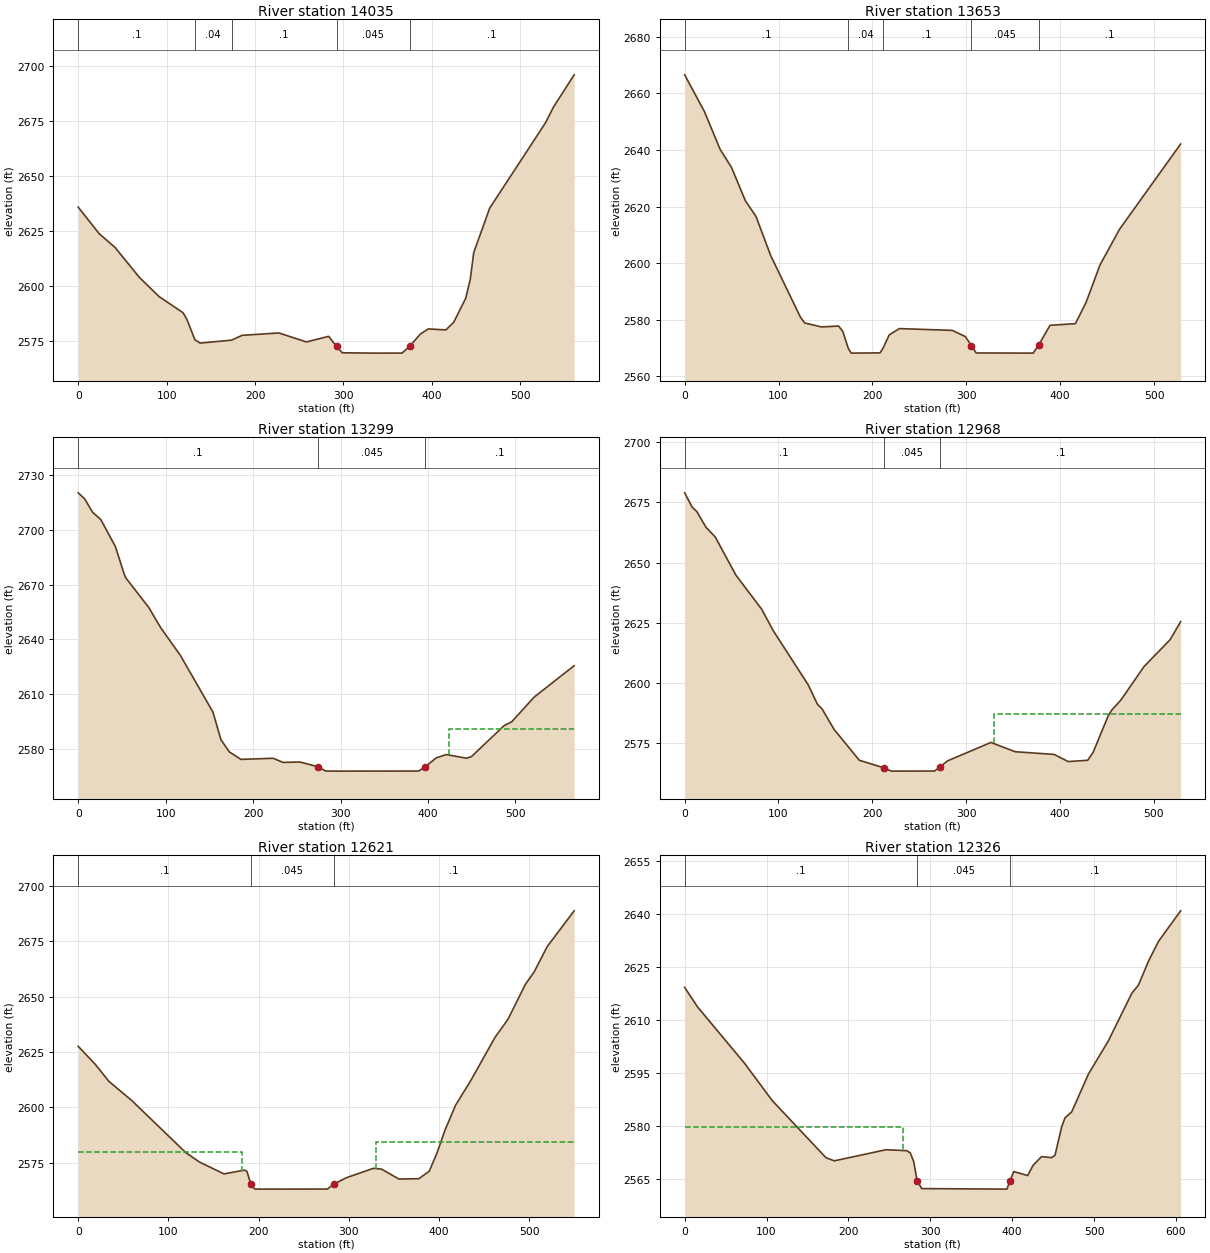
Type RM Length L Ch R = 1 ,14035   ,381.8,381.9,382.8
XS GIS Cut Line= 2
2219351.40424129 526924.037349022219609.81272132527421.946371506
#Sta/Elev= 30
       0 2635.71    23.8 2623.64    41.8 2617.37    68.9 2603.95    91.4 2595.12
   118.5  2587.8     123 2584.72     132 2575.48   137.9 2573.98   173.5 2575.32
   185.4  2577.5   226.9 2578.58   258.2 2574.51   283.3 2577.05   292.2 2572.44
   298.7 2569.58   334.8 2569.42   366.3 2569.44   375.1 2572.59   387.1  2578.1
     396 2580.41   415.9 2579.96   424.9 2583.52   438.4 2594.41   443.5 2602.99
   447.4 2615.08   465.5 2635.29   528.6 2674.03   537.6 2681.16     561 2695.81
#Mann= 5 ,-1,0
       0      .1       0     132     .04       0   173.5      .1       0
   292.2    .045       0   375.1      .1       0
Bank Sta=292.2,375.1
XS Rating Curve= 0 ,0
Exp/Cntr(USF)=0,0
Exp/Cntr=0.3,0.1

Type RM Length L Ch R = 1 ,13653   ,362.1,353.5,346.2
XS GIS Cut Line= 2
2218997.19554428527067.7376744972219240.47767426527536.654526053
#Sta/Elev= 30
       0 2666.54    21.1 2653.52    37.7 2640.26    49.9 2633.81    64.7 2622.02
      76  2616.5    91.7 2602.64   123.3 2580.93   127.9 2578.87   145.8 2577.47
   163.9 2577.79   168.4 2575.95   174.3 2569.88   177.4 2568.22     208 2568.31
     211 2569.77   217.9 2574.66   228.8 2576.89   285.1 2576.25     299 2574.07
   305.4  2570.9   310.5 2568.28   371.2 2568.22   377.1 2571.09   389.2 2578.05
   416.2 2578.63   427.6 2586.15   442.4 2599.35   463.2 2611.96   528.3 2642.09
#Mann= 5 ,-1,0
       0      .1       0   174.3     .04       0     211      .1       0
   305.4    .045       0   377.1      .1       0
Bank Sta=305.4,377.1
XS Rating Curve= 0 ,0
Exp/Cntr(USF)=0,0
Exp/Cntr=0.3,0.1

Type RM Length L Ch R = 1 ,13299   ,348.9,331.9,313
XS GIS Cut Line= 3
2218593.82620961527356.3988546212218791.72928944527467.325421656
2218987.11131092527745.902368414
#Sta/Elev= 30
       0 2720.28     7.3 2717.02    16.4 2709.65    25.8 2705.63    42.5 2690.83
    53.1 2674.96    55.2 2673.17    80.6 2657.48    94.4 2646.29   116.9 2631.09
     154 2600.14   163.2 2584.95   172.7  2578.3   186.1 2574.12   222.8 2574.74
   234.3 2572.47   253.6  2572.7   274.5 2570.05   282.9 2567.76   297.3 2567.69
   389.3 2567.73   396.2 2569.85   409.4 2574.97   420.9 2576.77   443.9 2574.79
   449.6 2575.62     487 2592.63   495.6 2594.69   521.4 2608.29   567.1  2625.5
#Mann= 3 ,-1,0
       0      .1       0   274.5    .045       0   396.2      .1       0
#XS Ineff= 2 , 0
                          423.89         2590.75
Permanent Ineff=
       F       F
Bank Sta=274.5,396.2
XS Rating Curve= 0 ,0
Exp/Cntr(USF)=0,0
Exp/Cntr=0.3,0.1

Type RM Length L Ch R = 1 ,12968   ,363.2,346.2,331.5
XS GIS Cut Line= 2
2218409.78895067527627.4126263542218837.10833959527938.763331555
#Sta/Elev= 30
       0 2678.95     7.9 2673.06    12.9  2671.2    22.7 2664.66    32.6 2660.61
    54.5 2644.83    82.1 2630.61    94.6 2621.59   131.8 2599.14   141.5 2591.17
   146.5  2589.2   159.2 2580.74   186.2 2567.87     212 2564.79   220.4 2563.37
   266.4 2563.41   272.1 2565.09   280.1 2567.61   326.5 2575.28   352.3 2571.43
   393.9  2570.3   408.8 2567.34   429.6 2567.87   435.3 2571.06   451.3 2586.16
   455.3 2588.74   464.9 2592.82   489.7  2606.8   517.7 2618.05   528.7 2625.45
#Mann= 3 ,0,0
       0      .1       0     212    .045       0   272.1      .1       0
#XS Ineff= 2 , 0
                          329.24         2587.29
Permanent Ineff=
       F       F
Bank Sta=212,272.1
XS Rating Curve= 0 ,0
Exp/Cntr(USF)=0,0
Exp/Cntr=0.3,0.1

Type RM Length L Ch R = 1 ,12621   ,297.9,295,293.8
XS GIS Cut Line= 3
2218208.10428333527989.184498389 2218520.7155177528101.371594594
2218700.97118913528223.642924167
#Sta/Elev= 30
       0 2627.53    18.8 2619.46    34.1 2611.68    59.5    2603   119.4 2579.46
   134.5 2575.24   161.6 2569.88   184.6  2571.6   187.1 2570.99   191.3 2565.47
   195.6 2563.08   200.2    2563   276.3 2563.04  283.38 2565.24   297.2 2568.13
   327.3  2572.4   336.3 2572.05   355.6 2567.56   377.7 2567.71   389.2 2571.08
   397.8  2579.3   406.5 2589.47   418.5 2600.98   435.3 2612.07     462  2631.5
   476.5 2639.74   495.8 2655.54   505.5 2661.13     520  2672.6   549.9 2688.77
#Mann= 3 ,0,0
       0      .1       0   191.3    .045       0  283.38      .1       0
#XS Ineff= 2 , 0
          181.52  2579.7  329.92         2584.45
Permanent Ineff=
       F       F
Bank Sta=191.3,283.38
XS Rating Curve= 0 ,0
Exp/Cntr(USF)=0,0
Exp/Cntr=0.3,0.1

Type RM Length L Ch R = 1 ,12326   ,254.1,237.5,232.9
XS GIS Cut Line= 3
2217998.85644097528236.2482158752218418.61265486 528376.16695384
2218578.69985956528407.680183111
#Sta/Elev= 30
       0 2619.31    15.6 2613.82    73.1 2597.85   106.8 2587.33   172.5 2571.15
   182.7 2570.25   245.9  2573.4   271.2 2573.12   275.5  2572.5   279.7 2570.02
   283.9 2564.59   289.5  2562.4   393.5 2562.25   397.1 2564.53   401.9 2567.22
   418.8 2566.09   425.5    2569   435.7 2571.43   448.1 2571.16   452.2 2571.81
   460.4  2579.9   464.4 2582.41   472.6 2584.09     493 2594.78   517.4  2604.2
     546 2617.66   554.1 2619.96   566.4 2626.75   578.6 2632.33   605.6 2640.97
#Mann= 3 ,-1,0
       0      .1       0   283.9    .045       0   397.1      .1       0
#XS Ineff= 2 , 0
          266.99 2579.85
Permanent Ineff=
       F       F
Bank Sta=283.9,397.1
XS Rating Curve= 0 ,0
Exp/Cntr(USF)=0,0
Exp/Cntr=0.3,0.1

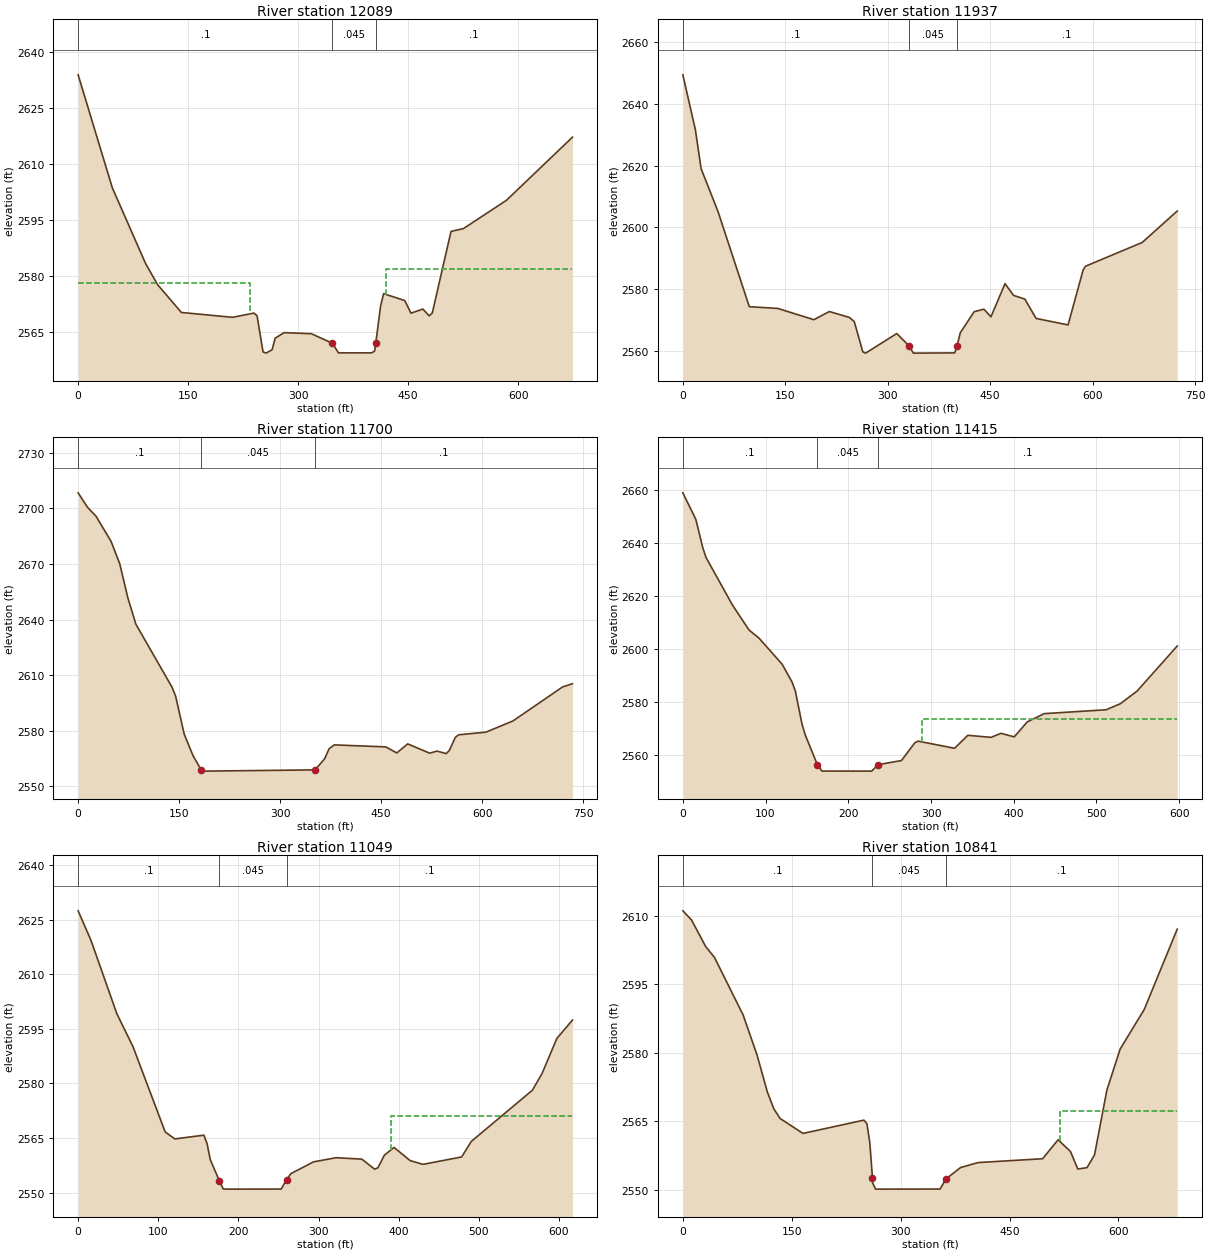
Type RM Length L Ch R = 1 ,12089   ,158.1,152,148.5
XS GIS Cut Line= 3
2217930.78786574528497.1777542412218384.57836725528604.322733764
2218579.96038873528533.733100196
#Sta/Elev= 30
       0    2634    46.6 2603.66    91.8 2583.39   108.3 2577.65   140.8 2570.17
   210.6 2568.87   239.8 2570.01     244 2569.26   252.1 2559.58   256.2 2559.25
   264.5 2560.17   268.6 2563.26   280.9 2564.75   317.9 2564.47   346.7 2561.91
   354.9 2559.32   400.1 2559.32   404.2 2559.79  405.85 2562.01   412.4 2571.92
   416.5 2575.22   445.3 2573.38   453.8 2569.98   470.1 2571.08   478.6 2569.27
   482.9 2570.05   508.4 2591.94   525.4 2592.71     584  2600.3     674 2617.26
#Mann= 3 ,0,0
       0      .1       0   346.7    .045       0  405.85      .1       0
#XS Ineff= 2 , 0
          233.86 2578.04  420.39         2581.88
Permanent Ineff=
       F       F
Bank Sta=346.7,405.85
XS Rating Curve= 0 ,0
Exp/Cntr(USF)=0,0
Exp/Cntr=0.3,0.1

Type RM Length L Ch R = 1 ,11937   ,319.1,236.4,177
XS GIS Cut Line= 5
2217890.45093228528634.575433864 2218187.9358166 528717.77035914
2218312.72820451528736.6782967032218428.69688823528706.425596603
2218556.01033449528595.499029568
#Sta/Elev= 30
       0 2649.45    18.4  2631.6    26.7 2619.05    51.6 2605.04    97.3 2574.25
   138.9 2573.69   191.8 2570.04   214.5 2572.68   243.7 2570.78     251 2569.43
   263.5  2559.6   267.6 2559.19   313.2 2565.54  330.97  2561.6   337.5 2559.19
   398.1 2559.27  401.32 2561.36   406.2 2565.79   426.5 2572.62   440.8 2573.45
   451.1 2570.96   471.7 2581.72   484.2 2577.91   500.7 2576.73   517.2 2570.44
     564 2568.34   586.1 2586.17   589.5 2587.37   672.6 2595.08   723.8 2605.27
#Mann= 3 ,0,0
       0      .1       0  330.97    .045       0  401.32      .1       0
Bank Sta=330.97,401.32
XS Rating Curve= 0 ,0
Exp/Cntr(USF)=0,0
Exp/Cntr=0.3,0.1

Type RM Length L Ch R = 1 ,11700   ,363.9,285.4,230
XS GIS Cut Line= 3
2218084.57242459529142.5686897172218477.85752589528788.359992708
2218574.91827205528608.104321276
#Sta/Elev= 30
       0 2708.35      14 2700.51    26.4 2695.82    48.9 2682.17    61.8 2670.05
    73.8 2651.75    85.7 2637.52   139.5 2603.45   144.8  2598.6   157.5 2578.18
   170.6 2566.57   182.5 2558.99   187.4 2558.22   351.9 2558.89   366.1 2564.96
   372.7 2570.31   380.2 2572.38   456.7  2571.3   473.2 2568.04   489.3 2572.92
   521.8 2567.92   532.9 2569.02   546.5 2567.68   551.1 2569.34   559.9 2576.34
   564.7  2577.8   605.6 2579.25   645.6 2585.29   719.2 2603.62     734 2605.39
#Mann= 3 ,0,0
       0      .1       0   182.5    .045       0   351.9      .1       0
Bank Sta=182.5,351.9
XS Rating Curve= 0 ,0
Exp/Cntr(USF)=0,0
Exp/Cntr=0.3,0.1

Type RM Length L Ch R = 1 ,11415   ,363,365.5,367.3
XS GIS Cut Line= 2
2218548.44715946529240.8899650432218588.78409293528644.659667231
#Sta/Elev= 30
       0 2658.76    15.7 2648.75    23.8 2638.41    27.8  2634.5    59.8 2616.51
    79.9 2607.03    91.9 2603.98     120 2594.12     132 2587.37     136 2583.99
     144 2571.56     148 2567.37  162.72 2556.11   168.1 2553.78   228.2 2553.75
     236 2556.18   264.3 2557.75   280.4 2564.43   284.4 2565.06   328.5 2562.37
   344.5 2567.27   372.6 2566.49   384.6 2568.03   400.6 2566.66   416.3 2572.31
   436.7 2575.44   511.7  2576.9   528.9 2579.19     549 2583.92   597.6 2600.95
#Mann= 3 ,-1,0
       0      .1       0  162.72    .045       0     236      .1       0
#XS Ineff= 2 , 0
                          289.69         2573.47
Permanent Ineff=
       F       F
Bank Sta=162.72,236
XS Rating Curve= 0 ,0
Exp/Cntr(USF)=0,0
Exp/Cntr=0.3,0.1

Type RM Length L Ch R = 1 ,11049   ,207.4,208.9,210.3
XS GIS Cut Line= 3
2218902.65585647529281.2268985112218942.99278994528894.244443059
2218924.08485237528667.349192306
#Sta/Elev= 30
       0  2627.4    16.1 2619.26    48.3 2599.15    68.4 2590.13   108.6 2566.68
   120.7 2564.76   156.9 2565.79   160.9 2563.45   164.9 2559.05   176.2 2553.28
     181 2551.03     185 2550.97   253.4 2550.99     260 2553.56   265.5 2555.23
   293.6 2558.45   321.8  2559.6     354 2559.21     370 2556.44   374.1 2556.85
   382.1 2560.29   394.2 2562.42   414.2 2558.81   430.3 2557.77   478.5 2559.81
   490.5 2564.06   566.8 2578.14   578.8 2582.71   597.3 2592.35   616.8 2597.41
#Mann= 3 ,-1,0
       0      .1       0   176.2    .045       0     260      .1       0
#XS Ineff= 2 , 0
                          390.42         2571.16
Permanent Ineff=
       F       F
Bank Sta=176.2,260
XS Rating Curve= 0 ,0
Exp/Cntr(USF)=0,0
Exp/Cntr=0.3,0.1

Type RM Length L Ch R = 1 ,10841   ,317.6,386.8,443.8
XS GIS Cut Line= 4
2219013.58242351529375.766586324 2219121.9879322529169.039802305
2219158.54327815528889.2023263762219237.95661592528744.241471728
#Sta/Elev= 30
       0 2611.04      12 2609.04    31.4 2603.24    43.6 2600.84    83.1 2588.23
   102.3 2579.45   116.4 2571.41   125.3 2567.73   133.9 2565.62   165.5 2562.35
   249.4 2565.25   253.5 2564.49   257.5 2560.36  261.17  2552.6   261.5 2551.47
   265.6 2550.16   354.3 2550.18   362.4 2552.38   382.5 2554.88   406.7 2555.97
   495.5 2556.81   516.9 2560.96   533.9 2558.39     544 2554.56   556.7 2554.86
     567 2557.64   584.1 2571.85   602.3 2580.78   635.6  2589.5   680.9 2607.02
#Mann= 3 ,0,0
       0      .1       0  261.17    .045       0   362.4      .1       0
#XS Ineff= 2 , 0
                          518.99         2567.15
Permanent Ineff=
       F       F
Bank Sta=261.17,362.4
XS Rating Curve= 0 ,0
Exp/Cntr(USF)=0,0
Exp/Cntr=0.3,0.1