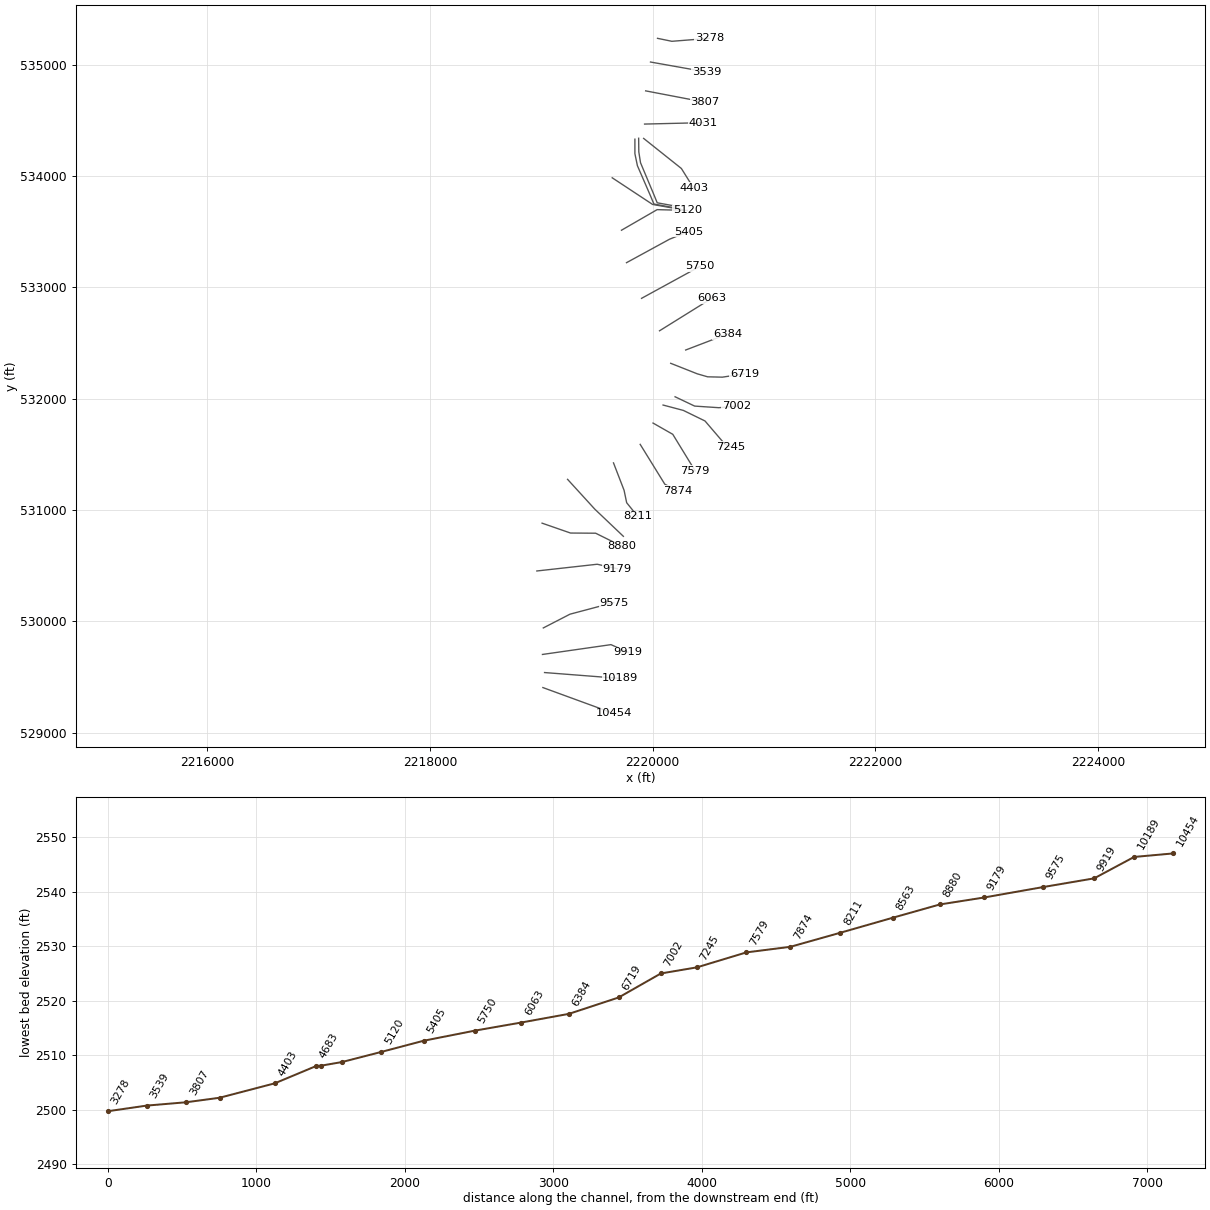
HEC-RAS study OLDFLDFK1.prj: OLDFLDFK1

--- OLDFLDFK1.g01 (geometry) --- (continued)

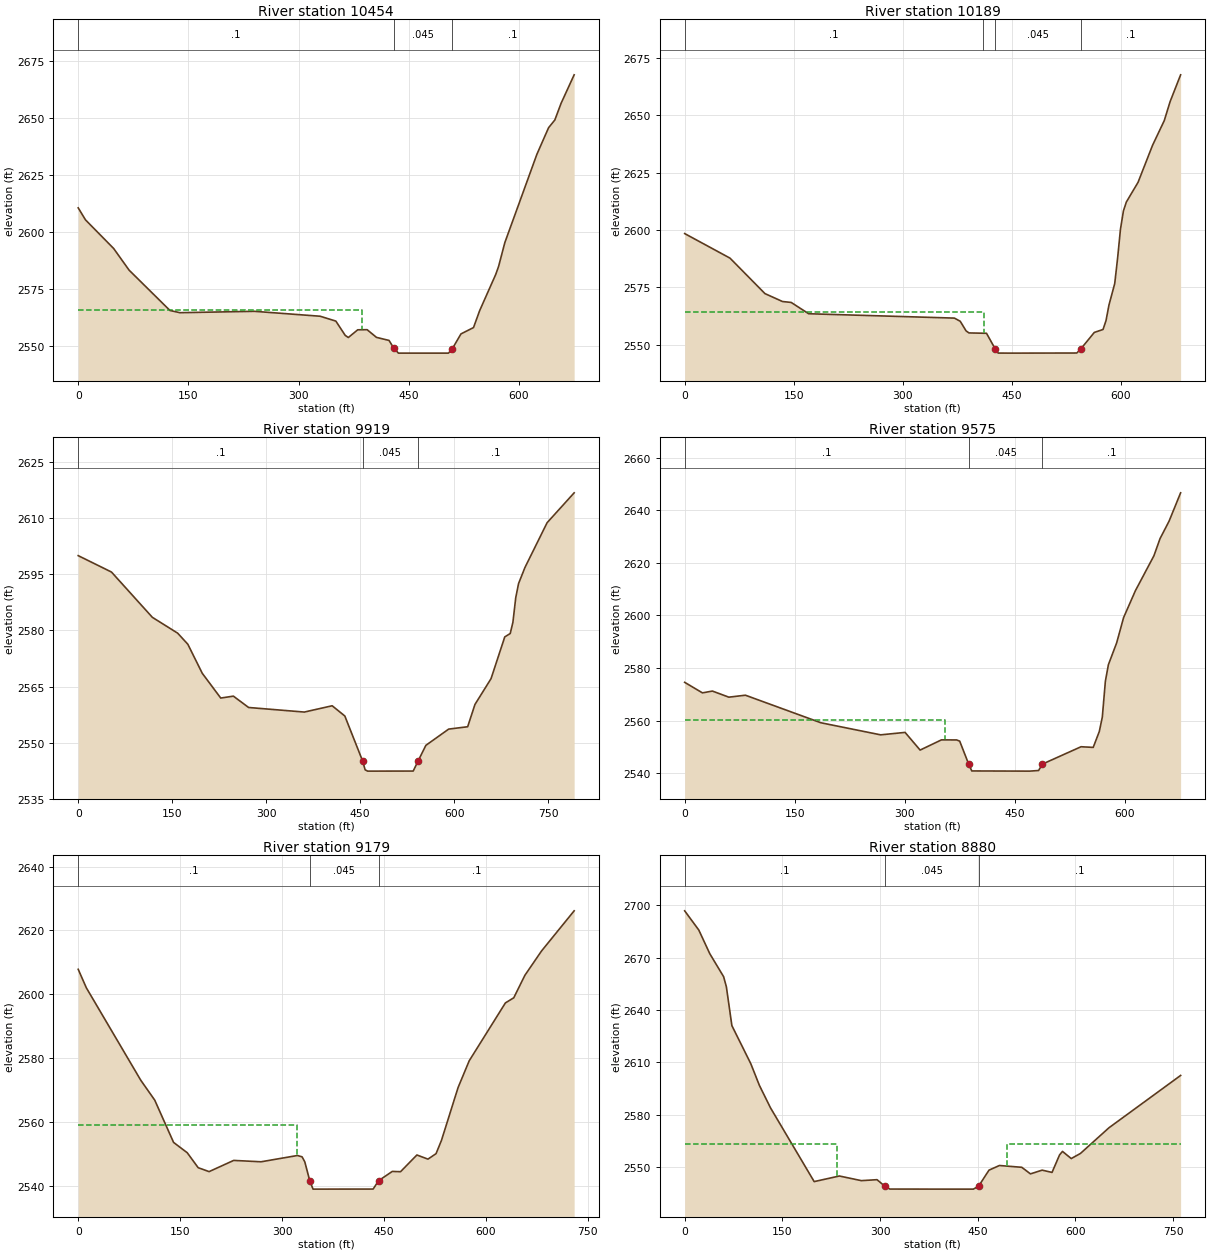
Type RM Length L Ch R = 1 ,10454   ,248.9,264.7,284.6
XS GIS Cut Line= 2
2219014.84295268529404.7587572542219648.88912561529172.821389818
#Sta/Elev= 30
       0 2610.73     9.9 2605.46    48.3 2592.88    69.3 2583.39   124.9  2565.7
   138.5 2564.74   239.9 2565.34   329.4 2563.18   350.7 2561.05   363.5 2554.77
   367.7 2553.85   380.5 2557.23   393.3 2557.28     406 2553.91   423.1 2552.57
   429.6 2549.17   435.9    2547     504    2547     509 2548.78     521 2555.42
   538.1 2558.21   546.4 2565.58   568.3 2581.47   572.2 2584.98   580.7 2595.44
   624.4 2634.24   640.3 2645.88   648.8 2649.26   657.3 2656.57   675.1 2669.08
#Mann= 3 ,-1,0
       0      .1       0   429.6    .045       0     509      .1       0
#XS Ineff= 2 , 0
          385.69 2565.85
Permanent Ineff=
       F       F
Bank Sta=429.6,509
XS Rating Curve= 0 ,0
Exp/Cntr(USF)=0,0
Exp/Cntr=0.3,0.1

Type RM Length L Ch R = 1 ,10189   ,257.2,269.5,286.7
XS GIS Cut Line= 2
2219029.96930273529539.6353785352219710.65505499529486.693153359
#Sta/Elev= 30
       0 2598.44    62.4 2587.74   110.5 2572.29   134.6 2568.84   146.6 2568.44
   170.7 2563.51   371.3 2561.61   379.3 2560.24   387.4 2556.03   391.4 2555.15
   415.5 2554.99   427.5 2548.19   431.5 2546.37     451 2546.35   539.8  2546.4
  545.19 2548.15   563.9 2555.37   575.9 2556.65     580 2560.52     584 2567.22
     592 2576.67     596 2587.85   599.9 2600.36     604 2608.34     608 2612.19
   624.1 2620.77   644.1 2636.93   660.2 2647.67   668.2  2655.9   682.7 2667.61
#Mann= 4 ,-1,0
       0      .1       0     410     .05       0   427.5    .045       0
  545.19      .1       0
#XS Ineff= 2 , 0
          412.51 2564.27
Permanent Ineff=
       F       F
Bank Sta=427.5,545.19
XS Rating Curve= 0 ,0
Exp/Cntr(USF)=0,0
Exp/Cntr=0.3,0.1

Type RM Length L Ch R = 1 ,9919    ,338,344.2,351.9
XS GIS Cut Line= 3
2219011.06136516529702.2436415752219626.19960054529790.480683534
2219781.24468855529721.151579138
#Sta/Elev= 30
       0 2599.95    53.1 2595.57   118.3 2583.48   158.7 2579.25   174.9  2576.3
   197.9 2568.55   227.4 2561.93   247.6 2562.44   271.9 2559.41   360.8 2558.19
   405.2 2559.87   425.4 2557.14   453.7 2545.17   457.8 2542.77   461.8 2542.42
   534.5 2542.44   542.6 2545.22   554.7  2549.3   591.1 2553.64   621.4 2554.27
     633 2560.21   658.7 2567.11   680.6 2578.26   689.3 2579.15   693.6 2582.17
   698.1 2588.71   702.6 2592.49   712.8 2596.79   748.1 2608.73   791.3 2616.72
#Mann= 3 ,-1,0
       0      .1       0   453.7    .045       0   542.6      .1       0
Bank Sta=453.7,542.6
XS Rating Curve= 0 ,0
Exp/Cntr(USF)=0,0
Exp/Cntr=0.3,0.1

Type RM Length L Ch R = 1 ,9575    ,404.7,396.2,385.2
XS GIS Cut Line= 3
2219018.62454019529940.4836548662219258.12508265530064.015513609
2219651.41018396 530168.63943479
#Sta/Elev= 30
       0 2574.57    24.2 2570.57    37.8 2571.25    60.3 2568.93    82.8 2569.68
   185.8  2559.2   267.3 2554.61   300.6 2555.54   321.1 2548.82   350.2  2552.7
   370.9 2552.67   375.1 2552.22   387.5 2543.37   391.6 2540.89   470.3 2540.82
   482.7 2541.05   487.9 2543.49   540.6 2550.09   557.2 2549.84   565.5 2555.88
   569.6 2561.34   573.8 2575.03   577.9 2581.27   589.2  2589.6   598.6 2599.16
   614.7 2609.38     640 2622.69   648.3 2629.17   660.7 2635.86   676.4  2646.6
#Mann= 3 ,-1,0
       0      .1       0   387.5    .045       0   487.9      .1       0
#XS Ineff= 2 , 0
          355.72  2560.2
Permanent Ineff=
       F       F
Bank Sta=387.5,487.9
XS Rating Curve= 0 ,0
Exp/Cntr(USF)=0,0
Exp/Cntr=0.3,0.1

Type RM Length L Ch R = 1 ,9179    ,305,298.6,293
XS GIS Cut Line= 3
2218960.64019833530452.258498231 2219502.6677418530512.763898432
2219682.92341323530472.426964965
#Sta/Elev= 30
       0 2607.81      12    2602    92.1 2573.04   112.7 2566.79   140.4 2553.55
   160.5 2550.32   176.6 2545.63   192.7  2544.4   228.9 2547.91   269.2 2547.48
   322.7 2549.45   329.6 2549.03   333.6 2547.44   340.8 2541.59   345.7 2538.91
   434.2 2538.93   442.1 2541.54   462.4 2544.46   474.5 2544.37   498.6 2549.61
   514.9 2548.31   526.8 2550.03   534.8 2554.21   559.2 2570.73   575.6 2579.13
   628.9 2597.28   641.2 2598.88   657.6 2605.94   682.2 2613.59   730.1 2626.14
#Mann= 3 ,-1,0
       0      .1       0   340.8    .045       0   442.1      .1       0
#XS Ineff= 2 , 0
           322.7 2558.89
Permanent Ineff=
       F       F
Bank Sta=340.8,442.1
XS Rating Curve= 0 ,0
Exp/Cntr(USF)=0,0
Exp/Cntr=0.3,0.1

Type RM Length L Ch R = 1 ,8880    ,361.7,317.3,235
XS GIS Cut Line= 4
2219007.70932345530881.8549016022219262.92757533530793.150996987
  2219488.577859530791.5947881342219726.67781349530673.322915313
#Sta/Elev= 30
       0 2696.68    21.7  2685.7    38.6 2672.16    59.8 2659.05      64 2653.34
    72.5 2631.07   101.5 2609.36   114.8 2596.89   131.8 2584.09   198.9 2541.93
   237.6 2545.13   271.4 2542.47   295.4 2543.03   307.2 2539.36   315.1 2537.67
   395.4 2537.63   443.4 2537.63   451.4 2539.29   467.4 2548.48   483.4 2551.13
   517.7 2550.11   531.1 2546.34     549 2548.48   564.2 2547.18   575.8 2557.19
   580.3 2559.19   593.7 2555.09   607.8 2558.01   651.7 2572.71   761.7  2602.6
#Mann= 3 ,-1,0
       0      .1       0   307.2    .045       0   451.4      .1       0
#XS Ineff= 2 , 0
           233.3 2563.42  494.87         2563.42
Permanent Ineff=
       F       F
Bank Sta=307.2,451.4
XS Rating Curve= 0 ,0
Exp/Cntr(USF)=0,0
Exp/Cntr=0.3,0.1

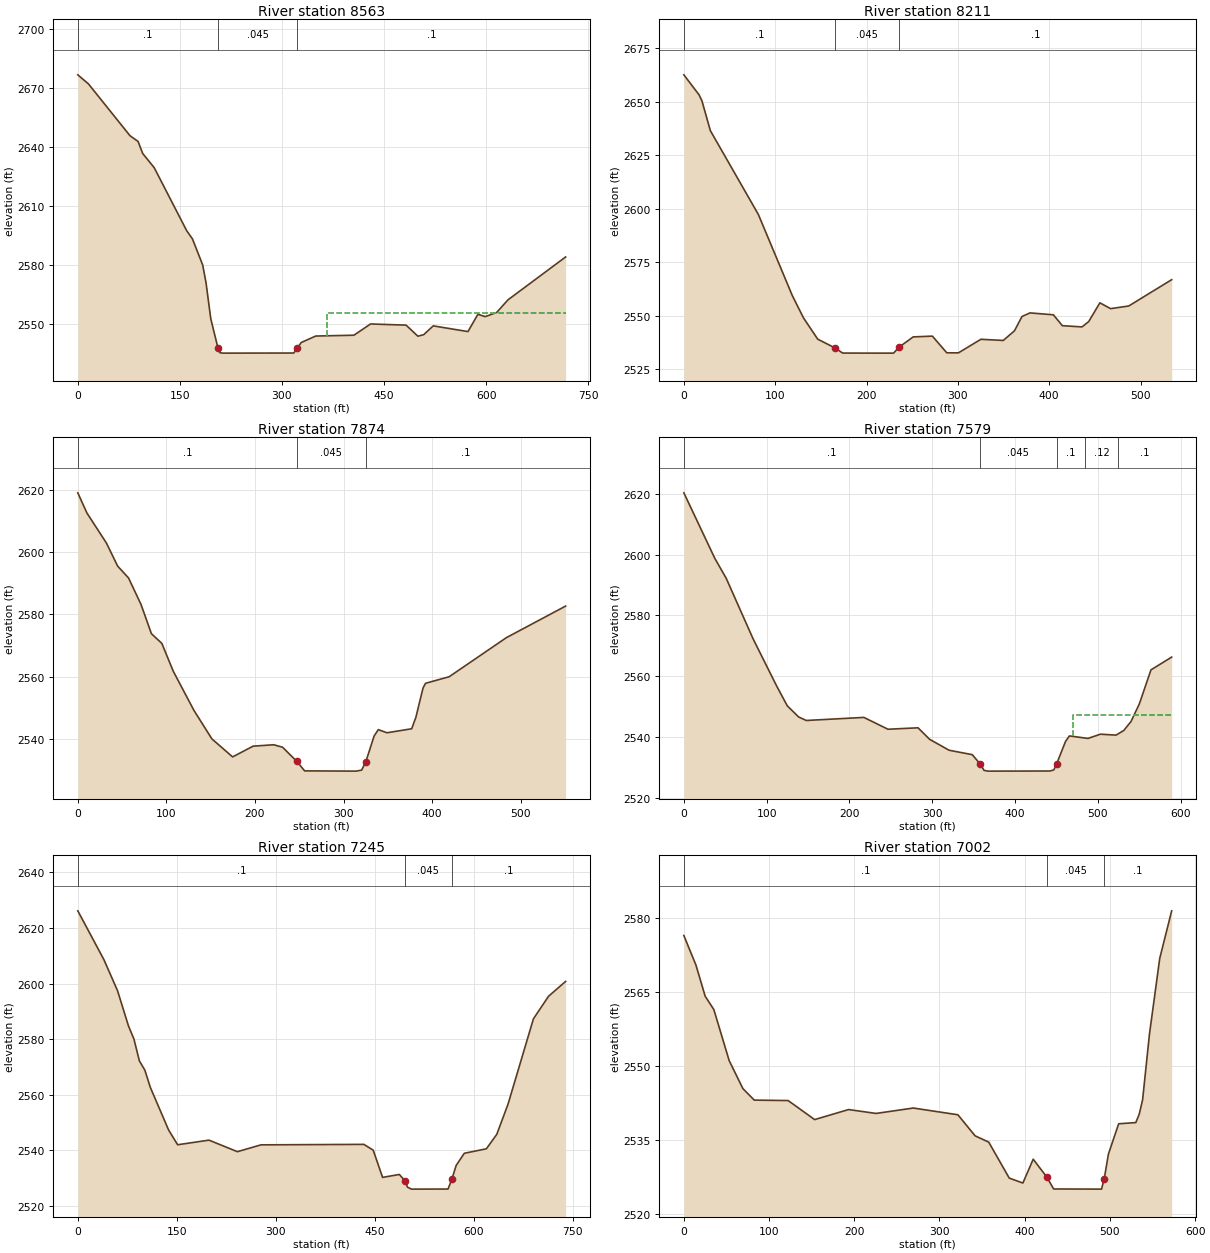
Type RM Length L Ch R = 1 ,8563    ,373.5,352.5,323
XS GIS Cut Line= 3
2219236.47202483531275.5757413872219480.79681473531007.907818688
2219737.57127546530763.583028782
#Sta/Elev= 30
       0 2676.91    15.6 2672.31    76.7  2645.9    88.6 2642.97    95.3 2636.88
   112.3 2629.61     160 2597.53   168.5 2593.34   183.5 2580.08   188.4 2571.06
   195.4 2552.68  205.97 2537.77     209 2535.38   213.2 2535.19   317.4 2535.24
   322.8 2537.76   328.2 2540.58   349.6 2543.89   405.7 2544.31   430.2 2550.04
   482.4 2549.44   499.7 2543.81   508.2 2544.57   522.3 2549.07   573.3 2546.16
   587.9 2554.96   598.7 2553.78   615.5  2555.9   632.1 2562.32   716.8 2584.16
#Mann= 3 ,0,0
       0      .1       0  205.97    .045       0   322.8      .1       0
#XS Ineff= 2 , 0
                          366.42         2555.58
Permanent Ineff=
       F       F
Bank Sta=205.97,322.8
XS Rating Curve= 0 ,0
Exp/Cntr(USF)=0,0
Exp/Cntr=0.3,0.1

Type RM Length L Ch R = 1 ,8211    ,327.1,336.6,347.2
XS GIS Cut Line= 4
2219648.86737085531423.4155824132219743.79611088531177.534583654
2219767.13924367531065.487546245 2219865.1804014530944.103255719
#Sta/Elev= 30
       0 2662.52    16.7 2653.15    19.8 2650.38      29 2636.45    81.6 2597.23
   118.7 2559.38   131.1 2548.83   146.6 2538.96   165.3 2534.91   173.9 2532.47
   207.7 2532.44   229.6 2532.44   235.6 2535.21   251.1 2540.03   272.1 2540.39
   287.9 2532.58   300.7 2532.57   325.2 2538.91   349.7 2538.36     362 2542.88
   370.2 2549.55     379 2551.24   404.6 2550.35   414.4 2545.27   435.9 2544.69
   443.3  2547.2   455.5 2555.96   467.2 2553.23   487.1 2554.47   534.1 2566.77
#Mann= 3 ,-1,0
       0      .1       0   165.3    .045       0   235.6      .1       0
Bank Sta=165.3,235.6
XS Rating Curve= 0 ,0
Exp/Cntr(USF)=0,0
Exp/Cntr=0.3,0.1

Type RM Length L Ch R = 1 ,7874    ,296.3,295.5,295.2
XS GIS Cut Line= 3
 2219888.5235342531589.9299296732220109.50519131531232.001893506
2220224.66464642531171.309748242
#Sta/Elev= 30
       0 2618.94    10.3 2612.48    32.3 2602.87      45 2595.48    57.3 2591.68
    71.4 2583.19    83.1 2573.86    94.9 2570.74   107.8 2561.83   131.1 2549.32
   151.4 2540.18   174.8 2534.41   197.9 2537.85   221.2  2538.3   231.2 2537.51
   247.3 2532.98   256.1 2529.94   314.2 2529.86   320.5 2530.18   325.2 2532.87
   334.6 2541.12   339.3 2543.14   349.1 2542.14     377 2543.42   381.7 2547.05
   389.8 2556.47   392.7 2557.98   419.3 2560.07   483.9 2572.58   550.8 2582.69
#Mann= 3 ,-1,0
       0      .1       0   247.3    .045       0   325.2      .1       0
Bank Sta=247.3,325.2
XS Rating Curve= 0 ,0
Exp/Cntr(USF)=0,0
Exp/Cntr=0.3,0.1

Type RM Length L Ch R = 1 ,7579    ,324,333.5,341.7
XS GIS Cut Line= 3
2220003.68298931 531781.343618582220181.09079854531680.190043141
2220381.84174057531351.829975179
#Sta/Elev= 30
       0 2620.32    37.4 2598.78    51.2  2592.2    83.4 2572.46   111.9 2556.91
   124.9 2550.31   138.7 2546.63   147.9 2545.49   217.4  2546.5   246.5 2542.61
   282.8 2543.08   296.8  2539.3   320.3 2535.71   348.3 2534.25   357.8  2531.2
   362.5  2529.1   367.2 2528.84   442.2 2528.88   446.9 2529.26   450.1 2531.16
   460.9 2538.59   465.6 2540.41     488 2539.59   503.1 2540.98   521.9 2540.68
   531.2 2542.18   539.9 2545.11     550 2550.89   564.1 2562.13   589.1 2566.32
#Mann= 5 ,-1,0
       0      .1       0   357.8    .045       0   450.1      .1       0
  484.22     .12       0  524.22      .1       0
#XS Ineff= 2 , 0
                          469.52         2547.29
Permanent Ineff=
       F       F
Bank Sta=357.8,450.1
XS Rating Curve= 0 ,0
Exp/Cntr(USF)=0,0
Exp/Cntr=0.3,0.1

Type RM Length L Ch R = 1 ,7245    ,199.6,242.6,292.6
XS GIS Cut Line= 5
2220093.94310278531943.1893392822220276.01953857531894.946864842
2220470.54564518531800.0181248152220646.39724556531594.598556232
2220703.97697312 531566.58679688
#Sta/Elev= 30
       0 2626.13    39.6 2608.56    60.2 2597.43    76.8 2584.75    85.1 2580.03
    93.3 2572.19   101.6 2568.87   109.9 2562.68   137.6 2547.35   151.3 2542.04
   198.8  2543.7   241.9 2539.55   277.5    2542   433.5 2542.18   447.7 2540.09
   461.9 2530.31   487.3 2531.36   495.9 2529.05   499.6  2526.8   505.7 2526.09
   561.1 2526.12   566.8 2529.56   573.4 2534.59   585.7 2538.97   619.2 2540.59
     635  2545.8     652 2556.61   690.5  2587.3   713.5 2595.44   739.3 2600.75
#Mann= 3 ,-1,0
       0      .1       0   495.9    .045       0   566.8      .1       0
Bank Sta=495.9,566.8
XS Rating Curve= 0 ,0
Exp/Cntr(USF)=0,0
Exp/Cntr=0.3,0.1

Type RM Length L Ch R = 1 ,7002    ,293.5,283.5,283.8
XS GIS Cut Line= 4
2220201.63665603532017.5683743782220377.53225704531933.759293896
2220594.81505829531919.2737738132220754.15577921 531932.72461389
#Sta/Elev= 30
       0 2576.54    14.2 2570.53      25 2564.21    35.2 2561.48    53.2  2551.1
    69.3 2545.41    82.6 2543.07   122.4 2542.98   153.5 2539.11   193.3 2541.15
   225.6 2540.36   269.3 2541.46   321.6 2540.09   341.8 2535.81   357.8 2534.53
   381.9 2527.21   397.9 2526.21     410 2531.05     426 2527.42     434    2525
   490.2 2524.97   493.4 2527.13   498.3 2532.11   510.3 2538.26   530.4  2538.5
   534.4 2540.18   538.4 2543.15   546.4 2556.44   558.5 2571.89   572.5 2581.56
#Mann= 3 ,-1,0
       0      .1       0     426    .045       0   493.4      .1       0
Bank Sta=426,493.4
XS Rating Curve= 0 ,0
Exp/Cntr(USF)=0,0
Exp/Cntr=0.3,0.1

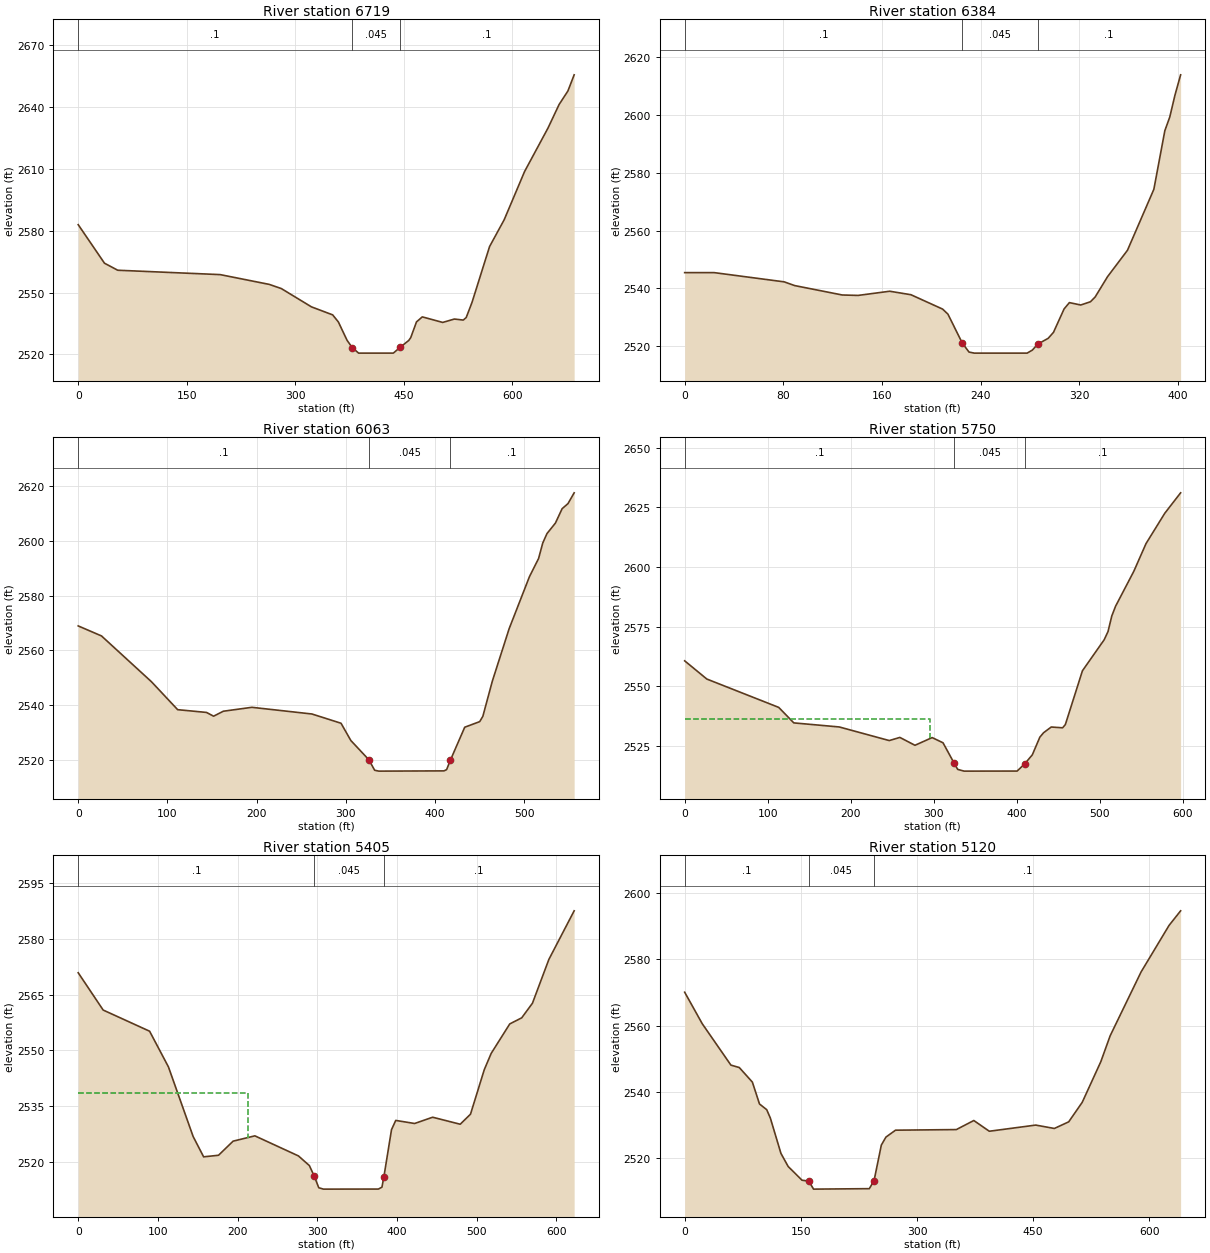
Type RM Length L Ch R = 1 ,6719    ,317.1,335,352.8
XS GIS Cut Line= 5
2220162.41629231532318.2356728312220402.07245565532223.306932804
2220493.88877797532196.8513823052220626.16653047532193.738964599
2220823.80505479532223.306932804
#Sta/Elev= 30
       0 2582.94    36.3 2564.24    54.6 2560.82   196.3 2558.69   264.1 2553.94
   280.8 2551.91   322.4 2543.03   351.7 2539.15   359.6 2535.71   371.6 2526.81
   378.7 2523.28   387.6 2520.57   435.6 2520.58   445.1 2523.43   456.9 2526.73
   459.6 2528.08   467.6 2535.74   475.6 2538.17   503.8 2535.48     520 2537.12
   532.2 2536.62   536.3 2537.85   544.3 2545.18   568.6 2572.32   588.8 2585.34
     617 2608.76   649.4 2629.89   664.7 2641.29   676.9 2647.87   685.5  2655.7
#Mann= 3 ,-1,0
       0      .1       0   378.7    .045       0   445.1      .1       0
Bank Sta=378.7,445.1
XS Rating Curve= 0 ,0
Exp/Cntr(USF)=0,0
Exp/Cntr=0.3,0.1

Type RM Length L Ch R = 1 ,6384    ,312.2,320.6,329.9
XS GIS Cut Line= 2
2220296.82721658532437.6484567962220672.41605874532581.468977623
#Sta/Elev= 30
       0 2545.44    23.9 2545.45    80.7 2542.25    89.2 2540.96   127.8  2537.7
   140.6 2537.55   166.3    2539   183.5 2537.79   209.2 2532.81   213.5 2531.06
   225.2 2520.99   230.6 2517.93   234.9 2517.56   277.7 2517.56     282 2518.62
   286.3 2520.67   294.8 2522.69   299.1 2524.76   307.7 2532.87     312 2535.06
   321.2 2534.23   329.1 2535.36   332.9 2537.01   342.9 2544.02   359.1 2553.19
   380.5 2574.31   389.4 2594.61   393.4 2599.34   397.6 2606.91   402.2 2613.97
#Mann= 3 ,-1,0
       0      .1       0   225.2    .045       0   286.3      .1       0
Bank Sta=225.2,286.3
XS Rating Curve= 0 ,0
Exp/Cntr(USF)=0,0
Exp/Cntr=0.3,0.1

Type RM Length L Ch R = 1 ,6063    ,315.9,313,309.2
XS GIS Cut Line= 2
2220062.06021319532610.2331840472220534.06990946532904.349778712
#Sta/Elev= 30
       0 2568.92    26.1 2565.27    82.1 2548.58   111.5 2538.38   143.9 2537.37
   151.8    2536   162.7 2537.81   194.7 2539.24   262.1  2536.8   294.7 2533.43
   305.7 2527.14     326 2520.08   332.4 2516.29   337.1 2515.97   410.2 2516.06
   413.1 2516.52   417.2 2519.86   433.4 2531.98   450.2 2534.02   453.7 2535.94
   464.4 2548.82   483.2  2567.9     506  2586.9   516.2 2593.49   520.9 2599.15
   525.6 2602.57   535.1 2606.42   542.6 2611.66   549.2 2613.52   556.1 2617.45
#Mann= 3 ,-1,0
       0      .1       0     326    .045       0   417.2      .1       0
Bank Sta=326,417.2
XS Rating Curve= 0 ,0
Exp/Cntr(USF)=0,0
Exp/Cntr=0.3,0.1

Type RM Length L Ch R = 1 ,5750    ,345.8,345.7,345.7
XS GIS Cut Line= 2
2219900.77046773532901.9778706912220424.96214048533188.978741291
#Sta/Elev= 30
       0 2560.71    26.7 2553.08   113.3  2541.2   131.5  2534.7   186.3 2532.99
   246.5 2527.29   259.3 2528.61   277.5 2525.31   298.2 2528.54   311.3 2526.36
  324.91 2517.68     329  2515.2   336.8 2514.48   400.6 2514.51   409.7 2517.51
   418.9 2521.31     428 2528.73   432.5 2530.58   441.7 2532.97   455.4 2532.64
   458.7 2533.99   479.3 2556.55   505.5 2569.55   510.1 2572.98   514.7 2579.55
   519.2 2583.59   541.2 2598.24   555.9 2609.85   578.5 2622.57   597.6 2631.14
#Mann= 3 ,0,0
       0      .1       0  324.91    .045       0   409.7      .1       0
#XS Ineff= 2 , 0
          295.77 2536.41
Permanent Ineff=
       F       F
Bank Sta=324.91,409.7
XS Rating Curve= 0 ,0
Exp/Cntr(USF)=0,0
Exp/Cntr=0.3,0.1

Type RM Length L Ch R = 1 ,5405    ,283.5,284.9,286.7
XS GIS Cut Line= 3
 2219765.5717105533222.185453592  2220152.192718533433.285267505
2220320.59818753533502.070600129
#Sta/Elev= 30
       0 2570.94    31.3 2560.89    89.6 2555.18   113.2 2545.58   144.2 2526.82
   157.4 2521.32   176.1 2521.75   194.4 2525.55   221.7 2526.98   276.4 2521.57
   290.1 2518.97  296.39 2516.03   301.9 2512.99   307.8 2512.62   376.7 2512.64
   381.2 2513.15  383.65 2515.98   393.2 2528.65   398.5 2531.14   422.2 2530.31
   444.8    2532   479.4 2530.11   492.3 2532.81   509.6 2544.81   518.3 2549.21
   541.6 2557.15   556.6 2558.79   570.1 2562.74   590.7 2574.54   622.4 2587.63
#Mann= 3 ,0,0
       0      .1       0  296.39    .045       0  383.65      .1       0
#XS Ineff= 2 , 0
          212.96 2538.44
Permanent Ineff=
       F       F
Bank Sta=296.39,383.65
XS Rating Curve= 0 ,0
Exp/Cntr(USF)=0,0
Exp/Cntr=0.3,0.1

Type RM Length L Ch R = 1 ,5120    ,304.3,263.8,208
XS GIS Cut Line= 3
2219720.50545809533513.9301402362220040.71304099533698.938965913
2220311.11055544533691.823241848
#Sta/Elev= 30
       0 2570.07    22.7 2560.54    59.7 2548.04    70.5 2547.31    87.4 2542.91
    96.6  2536.3   105.9 2534.58   110.6 2532.05   124.3 2521.36   133.6 2517.42
   151.5 2513.26   160.2    2513   166.4 2510.57   238.4 2510.71   244.5 2513.13
   253.9 2523.88   259.8 2526.28   272.2 2528.38   350.7 2528.56   373.3  2531.3
   393.3 2528.06   453.3 2529.92   477.3  2528.9   495.8  2530.9   513.3 2536.81
   537.3 2549.09   549.3 2556.89   589.3 2576.21   625.4 2590.26   640.3 2594.66
#Mann= 3 ,-1,0
       0      .1       0   160.2    .045       0   244.5      .1       0
Bank Sta=160.2,244.5
XS Rating Curve= 0 ,0
Exp/Cntr(USF)=0,0
Exp/Cntr=0.3,0.1

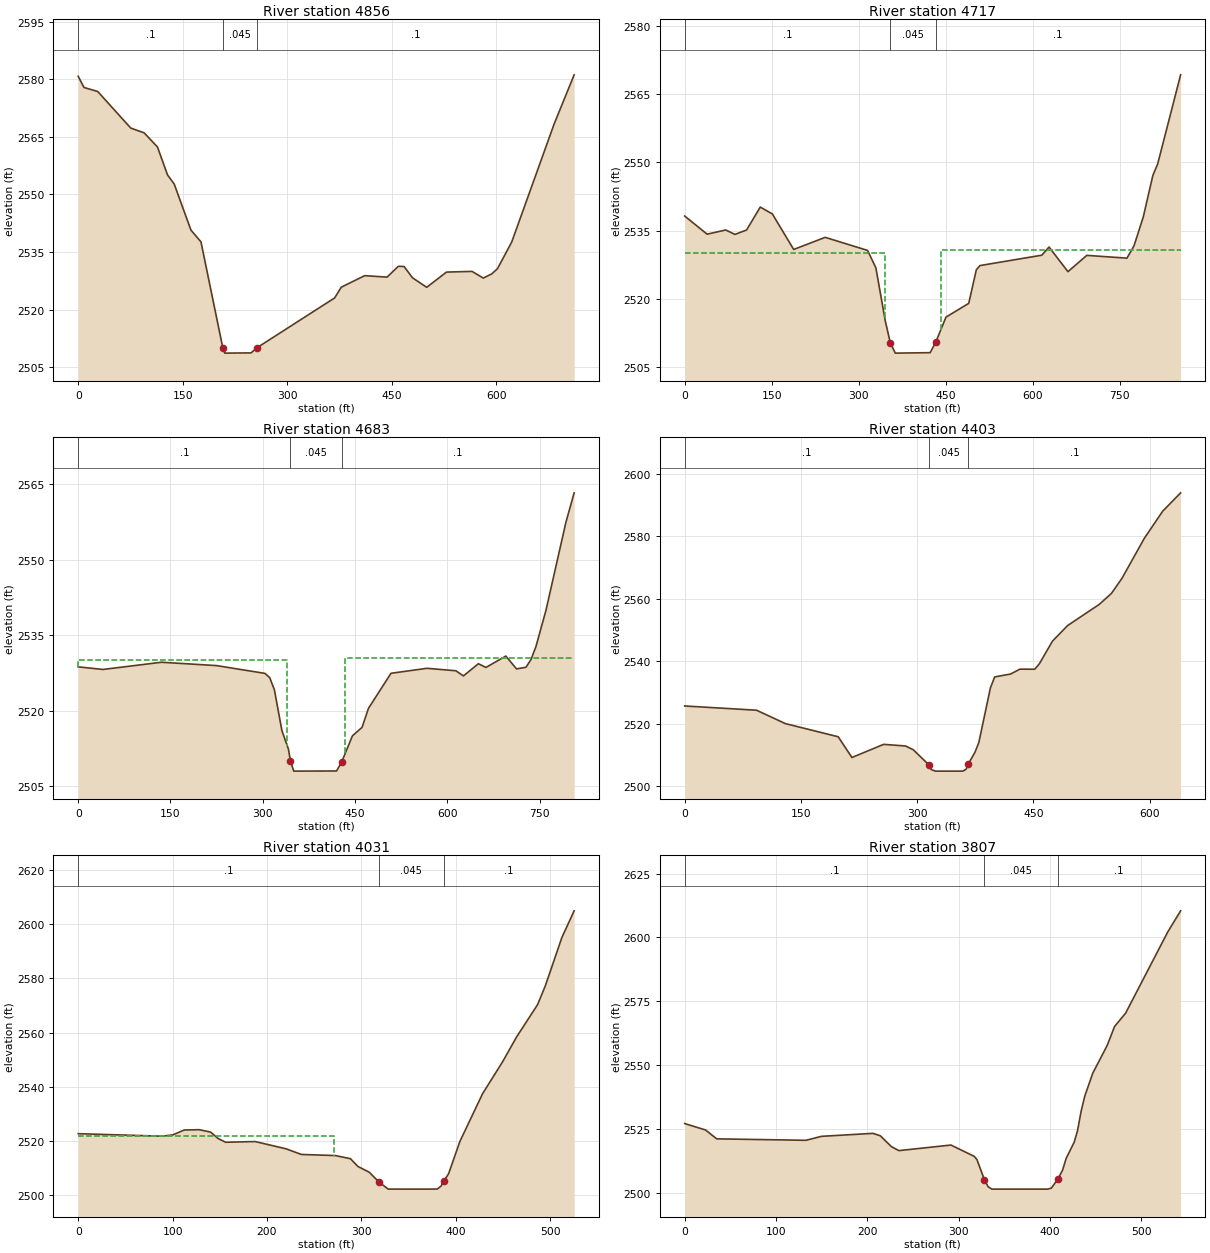
Type RM Length L Ch R = 1 ,4856    ,164.1,138.7,109
BEGIN DESCRIPTION:
xs 4
END DESCRIPTION:
XS GIS Cut Line= 3
2219637.25104068533985.0779920172219999.93610828533745.601727286
2220272.38374279 533697.01234024
#Sta/Elev= 30
       0 2580.75     8.3 2577.85      28  2576.8    75.4 2567.28    94.6 2566.04
   113.7 2562.37   128.1  2555.1   137.7 2552.73   161.7 2540.74   176.1 2537.67
  207.48 2510.05   210.3 2508.72     248 2508.78   256.1 2510.08   367.8 2523.08
   377.4 2525.88   410.9 2528.88     443  2528.5   459.1  2531.3   467.4 2531.27
   479.6 2528.31   499.9 2525.85   528.3 2529.81   564.9 2529.99   581.1 2528.25
   593.3 2529.35   601.4 2530.69   621.8 2537.61   682.7 2568.35   711.4 2581.14
#Mann= 3 ,0,0
       0      .1       0  207.48    .045       0   256.1      .1       0
Bank Sta=207.48,256.1
XS Rating Curve= 0 ,0
Exp/Cntr(USF)=0,0
Exp/Cntr=0.5,0.3

Type RM Length L Ch R = 1 ,4717    ,35,34.4,33.4
BEGIN DESCRIPTION:
xs 3
END DESCRIPTION:
XS GIS Cut Line= 6
2219841.04006001534331.8850645142219841.04006001534201.630383526
2219863.44946749 534093.785110022219974.09591693533838.878099914
2220011.91179206533749.2404699872220247.21057061533705.822242991
#Sta/Elev= 30
       0  2538.2    38.7 2534.21    70.7 2535.13    86.7 2534.16   106.7 2535.13
   130.3 2540.17   151.1 2538.66   187.9 2530.85   242.2 2533.51   315.2 2530.64
   329.6  2526.8   345.7 2515.17   354.4 2510.35     363 2508.06   423.1 2508.16
   432.8 2510.48   450.4 2515.98   489.6    2519   502.7 2526.39     509 2527.31
   615.6 2529.59     628 2531.39   660.6 2525.97   693.1 2529.55   762.3 2528.94
   774.5 2531.66   790.4 2537.98     807 2547.14   815.2 2549.62   854.8 2569.24
#Mann= 3 ,-1,0
       0      .1       0   354.4    .045       0   432.8      .1       0
#XS Ineff= 2 , 0
             345 2530.06     441         2530.76
Permanent Ineff=
       F       F
Bank Sta=354.4,432.8
XS Rating Curve= 0 ,0
Exp/Cntr(USF)=0,0
Exp/Cntr=0.5,0.3

Type RM Length L Ch R = 1 ,4683    ,259.4,280,305.6
BEGIN DESCRIPTION:
xs 2
END DESCRIPTION:
XS GIS Cut Line= 6
2219874.65417123534340.288592319 2219876.0547592534218.437439137
2219891.46122684534120.3962814042220013.31238002533829.073984141
2220041.32413938533760.4451737282220233.20469094533725.430474538
#Sta/Elev= 30
       0  2528.7    40.2 2528.18   135.3 2529.61   224.6 2528.95   303.6  2527.4
   311.3 2526.55   318.9 2524.14   331.1 2516.04   341.7 2512.36     345 2510.03
   350.3    2508   419.9 2508.03   428.4 2509.86   445.7    2515   461.4 2516.69
   471.7 2520.44   508.4 2527.42     567 2528.41   613.9 2527.92   626.1  2526.9
   650.5 2529.32   662.7 2528.58     695 2530.84   712.5 2528.29   727.8 2528.62
   735.9 2530.14     744 2532.72   760.3 2539.93   792.8 2557.43   806.1 2563.24
#Mann= 3 ,-1,0
       0      .1       0     345    .045       0   428.4      .1       0
#XS Ineff= 2 , 0
             340    2530     434          2530.5
Permanent Ineff=
       F       F
Bank Sta=345,428.4
XS Rating Curve= 0 ,0
Exp/Cntr(USF)=0,0
Exp/Cntr=0.5,0.3

Type RM Length L Ch R = 1 ,4403    ,345,371.9,406.3
BEGIN DESCRIPTION:
xs 1
END DESCRIPTION:
XS GIS Cut Line= 3
2219919.47298619534338.8880043522220258.41527436534068.574526603
2220367.66113583533893.501030651
#Sta/Elev= 30
       0 2525.65    92.8 2524.29   129.8 2520.02   198.1  2515.8   215.8 2509.17
   256.7 2513.37     285 2512.85   294.9 2511.66   314.8 2506.89   318.1 2505.32
   323.5 2504.81     359 2504.81   363.2 2505.44     366 2507.13   374.6 2510.87
   379.5 2513.92   394.5 2531.45     400 2534.94   420.4 2535.86   432.6 2537.43
   451.7  2537.4   457.6 2539.13   474.6  2546.4   494.1 2551.37   535.1 2558.17
   550.7 2561.67   564.1 2566.42   593.1 2579.28   616.7 2587.92   639.9 2593.82
#Mann= 3 ,-1,0
       0      .1       0   314.8    .045       0     366      .1       0
Bank Sta=314.8,366
XS Rating Curve= 0 ,0
Exp/Cntr(USF)=0,0
Exp/Cntr=0.3,0.1

Type RM Length L Ch R = 1 ,4031    ,233.1,224,210.9
XS GIS Cut Line= 2
  2219927.876514534467.7420973722220453.09700185534480.347389081
#Sta/Elev= 30
       0 2522.64      89 2521.71   100.3  2522.2   112.3    2524   128.3 2524.11
   140.3 2523.22   148.3 2520.84   156.3 2519.47   187.4 2519.74   220.4 2517.03
   236.4 2514.97   272.4 2514.56   288.4  2513.4   296.4 2510.52   308.4 2508.39
   318.2  2504.9   328.4 2502.17   368.4 2502.16   380.4 2502.19   384.4 2503.29
  387.492505.184   392.4 2507.86   404.4 2519.81   428.4 2537.42   449.8 2549.31
   464.4 2558.36   486.7 2570.33   494.9 2577.29   512.4 2595.11   525.4 2604.96
#Mann= 3 ,-1,0
       0      .1       0   318.2    .045       0  387.49      .1       0
#XS Ineff= 2 , 0
           271.1 2521.71
Permanent Ineff=
       F       F
Bank Sta=318.2,387.49
XS Rating Curve= 0 ,0
Exp/Cntr(USF)=0,0
Exp/Cntr=0.3,0.1

Type RM Length L Ch R = 1 ,3807    ,267.5,267.6,268.8
XS GIS Cut Line= 2
2219937.68062977534766.0673344732220471.30464543534663.824412838
#Sta/Elev= 30
       0 2527.04    22.9 2524.51    35.1 2521.04   132.9 2520.47   149.9 2522.03
   206.2 2523.19   214.3 2522.25   226.5 2517.99   234.7 2516.43   291.7 2518.61
   317.3 2514.16   320.2  2512.9   328.4 2504.97   332.4 2502.29   336.5 2501.34
   397.6 2501.34   401.7 2501.75   408.6 2505.18   413.9  2508.7     418 2513.46
   426.7 2519.72   430.3 2524.15   434.3 2531.83   438.3 2537.79   447.2 2546.88
   462.8 2557.59   470.9 2565.03   483.1 2570.33   529.2  2602.1   543.3 2610.39
#Mann= 3 ,0,0
       0      .1       0   328.4    .045       0   408.6      .1       0
Bank Sta=328.4,408.6
XS Rating Curve= 0 ,0
Exp/Cntr(USF)=0,0
Exp/Cntr=0.3,0.1

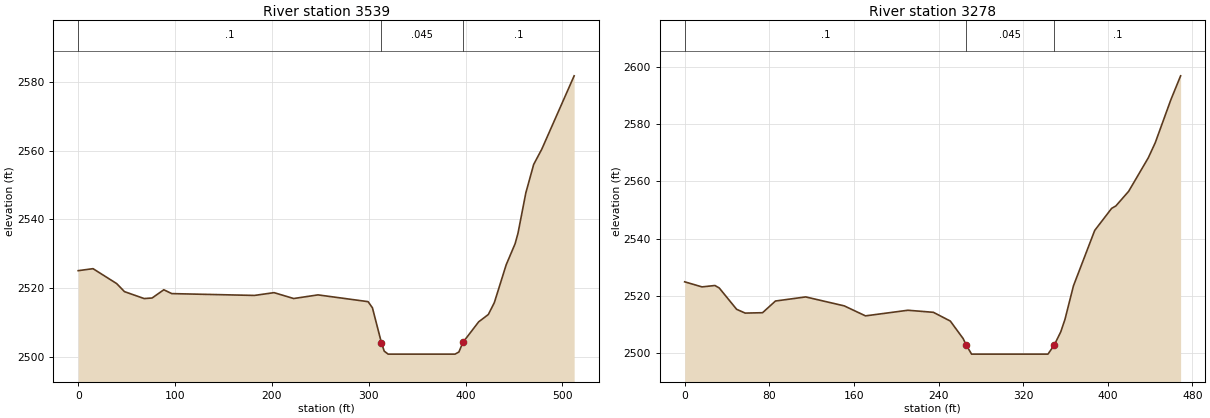
Type RM Length L Ch R = 1 ,3539    ,248.9,260.9,277.7
XS GIS Cut Line= 2
2219981.09885677535025.1761084822220485.31052511534935.538478555
#Sta/Elev= 30
       0 2525.02    15.3  2525.6    39.7 2521.26    47.8 2518.91    68.1  2516.9
    76.3 2517.06    88.4 2519.46    96.6 2518.34     182 2517.81   202.2 2518.62
   222.5 2516.91   247.6 2517.97   299.3    2516   303.8 2514.21   313.1 2504.04
     316 2501.59     320 2500.72   389.1 2500.72   393.1 2501.34   397.2 2504.12
   413.5 2510.12   423.5 2512.26   429.7 2515.73   441.9 2526.72   451.1 2532.84
   454.1  2535.9   462.2 2547.66   470.3 2555.94   478.7 2560.41   512.1 2581.75
#Mann= 3 ,0,0
       0      .1       0   313.1    .045       0   397.2      .1       0
Bank Sta=313.1,397.2
XS Rating Curve= 0 ,0
Exp/Cntr(USF)=0,0
Exp/Cntr=0.3,0.1

Type RM Length L Ch R = 1 ,3278    ,214.7,216.7,220.8
XS GIS Cut Line= 3
2220044.12531531535238.0654795592220172.97940833535211.454308174
2220509.12052056535238.065479559
#Sta/Elev= 30
       0 2524.92    16.4 2523.15    28.6 2523.64    32.7 2522.76    49.1 2515.33
    57.2 2514.01    73.6 2514.14    85.8 2518.22   114.4 2519.65   150.8 2516.53
   170.9 2513.04     211    2515   235.1 2514.28   251.1 2511.23   263.2 2505.13
   266.3 2502.76   271.2 2499.69   343.4 2499.69  349.29 2502.82   355.5 2507.46
   359.5 2511.84   367.5 2523.52   387.6 2542.86   403.6 2550.55   407.6  2551.4
   419.7 2556.51   438.2 2568.16   444.8 2573.44   459.6 2588.48   468.8  2596.8
#Mann= 3 ,0,0
       0      .1       0   266.3    .045       0  349.29      .1       0
Bank Sta=266.3,349.29
XS Rating Curve= 0 ,0
Exp/Cntr(USF)=0,0
Exp/Cntr=0.3,0.1