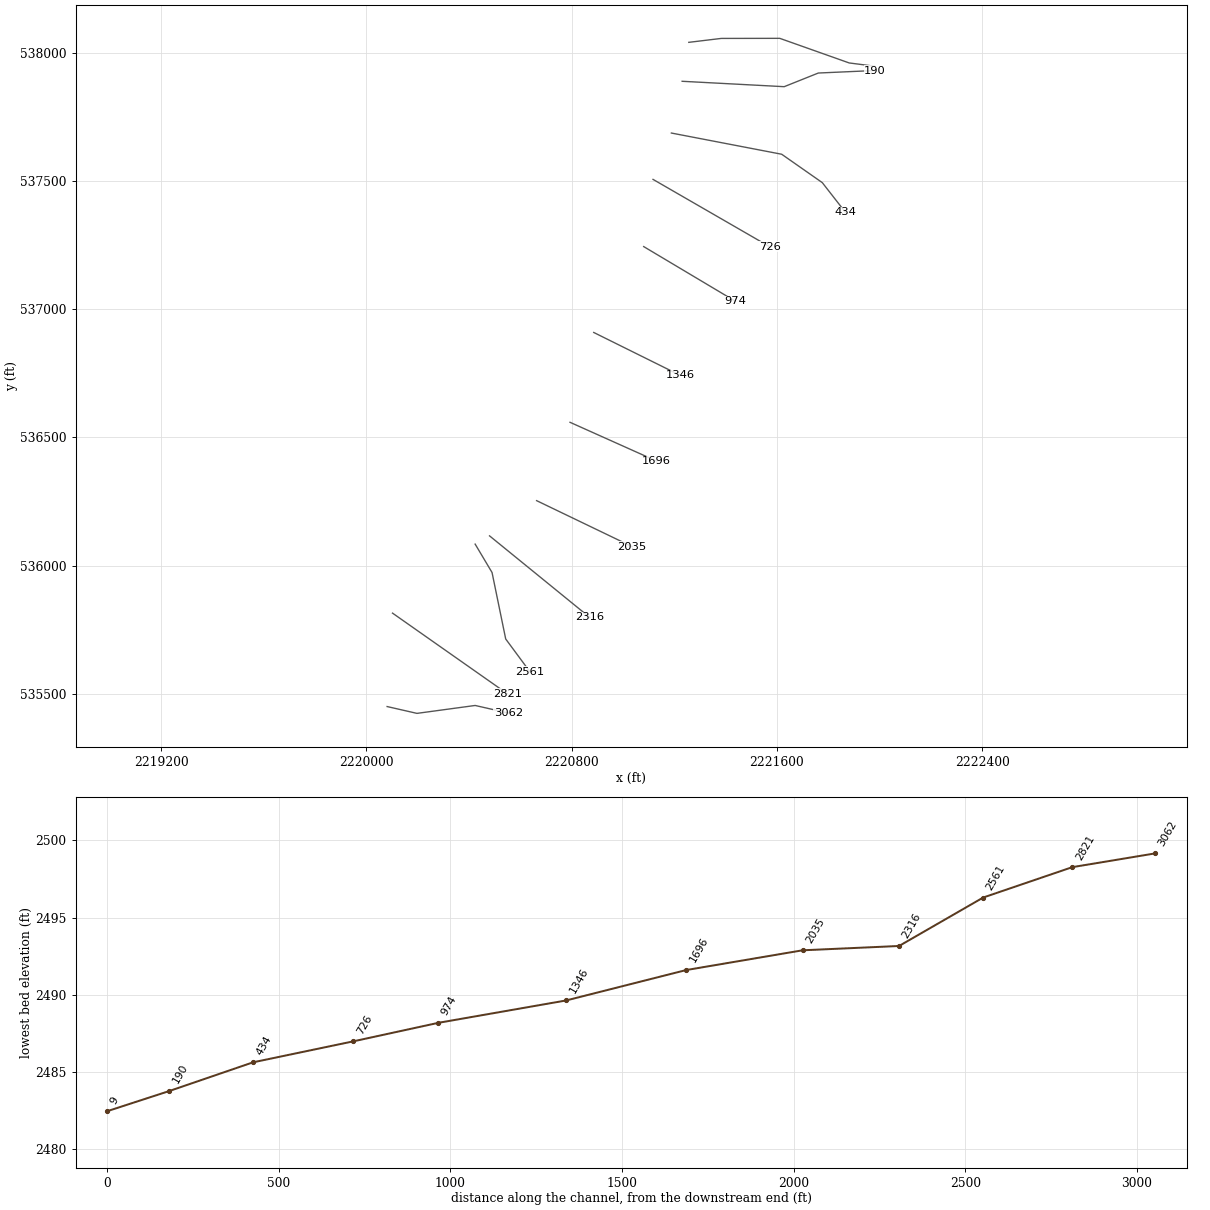
HEC-RAS study OLDFLDFK1.prj: OLDFLDFK1

--- OLDFLDFK1.g01 (geometry) --- (continued)

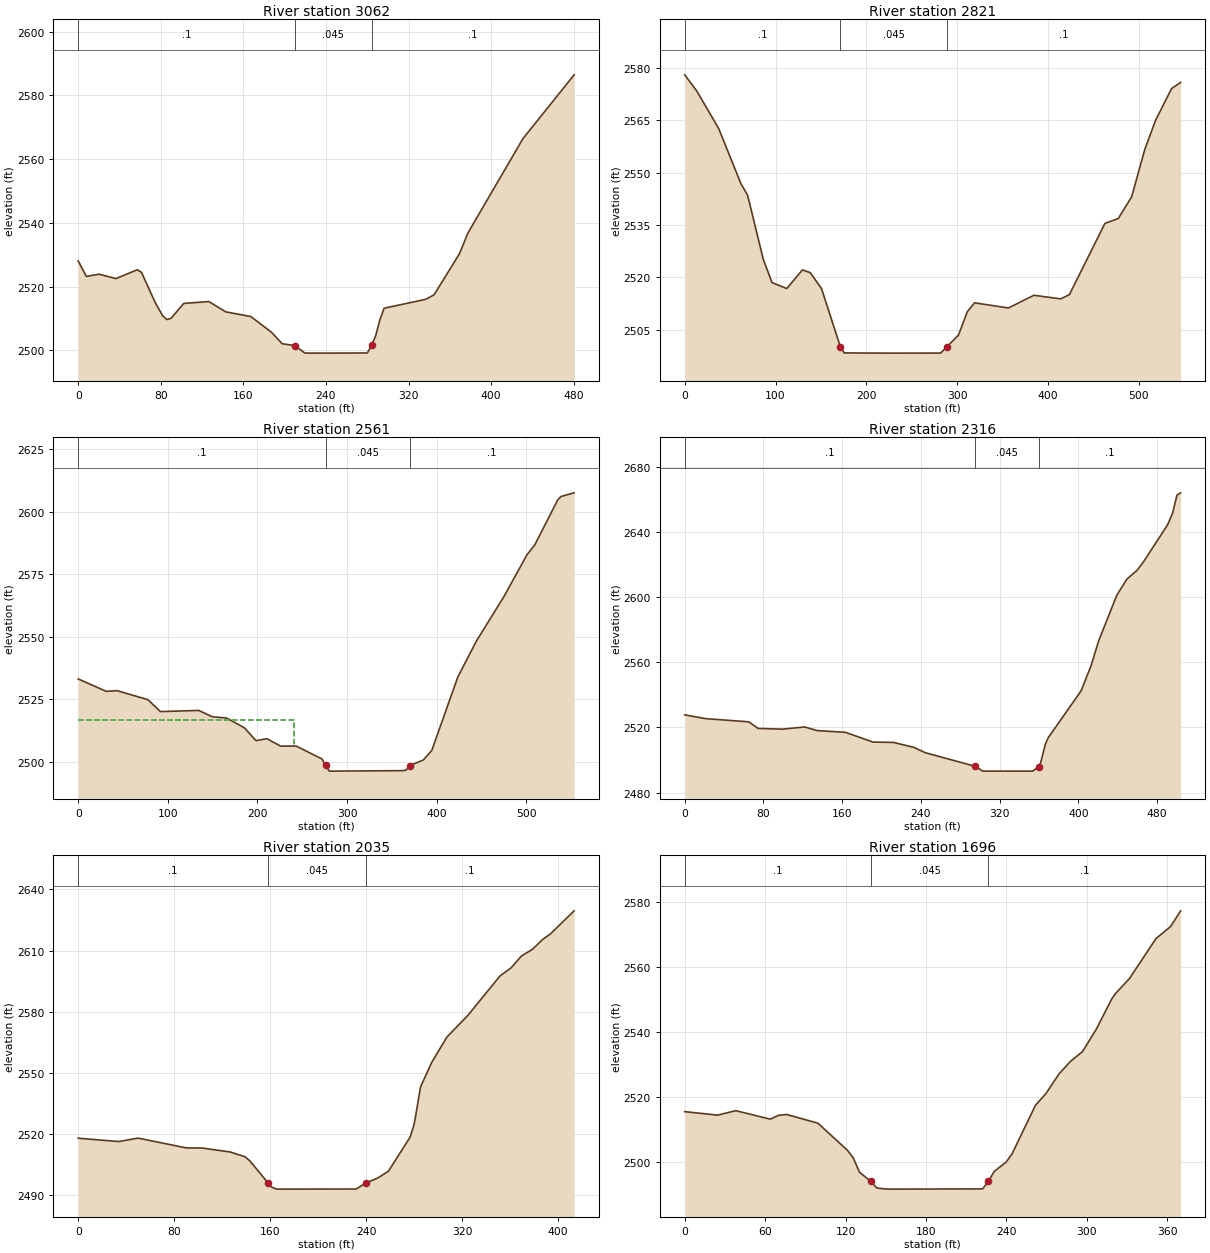
Type RM Length L Ch R = 1 ,3062    ,304.9,241.1,195.3
XS GIS Cut Line= 4
2220080.54060247535450.9548506362220196.78940378535424.343679251
2220423.68465453535455.1566145392220552.53874755535425.744267219
#Sta/Elev= 30
       0  2528.1     7.9 2523.22    20.1 2523.93    36.6 2522.55    57.1 2525.31
    61.2 2524.56    74.6 2515.04    81.7 2510.92    85.8 2509.71    89.9 2510.07
   102.2 2514.75   126.6 2515.34   142.9 2512.11   167.1 2510.65     187 2505.78
   197.6 2502.11  209.77 2501.52   219.6 2499.18   240.3 2499.16   280.1 2499.21
  284.38 2501.69   288.2 2504.67   292.2  2509.6   296.3 2513.25   336.6 2516.04
   344.7 2517.45   369.3 2530.34   377.5 2536.85   430.8 2566.46   480.4 2586.48
#Mann= 3 ,0,0
       0      .1       0  209.77    .045       0  284.38      .1       0
Bank Sta=209.77,284.38
XS Rating Curve= 0 ,0
Exp/Cntr(USF)=0,0
Exp/Cntr=0.3,0.1

Type RM Length L Ch R = 1 ,2821    ,319.9,259.7,213
XS GIS Cut Line= 2
2220101.54942198535815.1077222152220548.33698365 535501.37601747
#Sta/Elev= 30
       0 2577.98      13 2573.48    37.4 2562.63    61.9 2546.83    69.3 2543.47
    86.5 2525.17    96.1 2518.48   112.4 2516.77   129.6 2522.12   138.2 2521.32
   150.6 2516.77  171.48    2500   175.6 2498.33   221.5 2498.27   281.8 2498.28
   288.7  2500.1   301.4 2503.44   311.1 2510.12   319.1 2512.68   356.4  2511.2
   384.4 2514.84   413.9 2513.81   423.5 2515.03   462.6 2535.43   477.3 2536.83
     492 2543.04   506.6 2556.71   518.4 2564.98     536 2574.06   545.9 2575.81
#Mann= 3 ,0,0
       0      .1       0  171.48    .045       0   288.7      .1       0
Bank Sta=171.48,288.7
XS Rating Curve= 0 ,0
Exp/Cntr(USF)=0,0
Exp/Cntr=0.3,0.1

Type RM Length L Ch R = 1 ,2561    ,208.9,245,283.6
XS GIS Cut Line= 4
2220423.68465453536084.0206119972220489.51228901535973.374162555
2220542.73463178535714.2653885472220637.97461358535585.411295527
#Sta/Elev= 30
       0 2533.13    31.2 2528.18    43.3 2528.46    77.8 2524.86    91.7 2520.09
   134.6 2520.55   149.4 2518.04   165.7 2517.51   185.4 2513.63   198.4 2508.48
   210.6 2509.25     226 2506.28   243.3 2506.32   271.9 2501.19     276 2498.82
     280 2496.37   284.1  2496.3   361.7  2496.5   365.8 2496.66   369.9 2498.47
   385.2 2500.76   394.6 2504.56   423.7 2533.93   444.4 2548.25   475.2 2566.08
   500.9 2582.77   509.5 2586.65   535.2 2604.66   538.9 2606.04   553.5 2607.49
#Mann= 3 ,-1,0
       0      .1       0     276    .045       0   369.9      .1       0
#XS Ineff= 2 , 0
          240.68 2516.58
Permanent Ineff=
       F       F
Bank Sta=276,369.9
XS Rating Curve= 0 ,0
Exp/Cntr(USF)=0,0
Exp/Cntr=0.3,0.1

Type RM Length L Ch R = 1 ,2316    ,270.9,281.2,291.8
XS GIS Cut Line= 2
2220479.70817324536116.234135252 2220870.4722162535798.300666604
#Sta/Elev= 30
       0 2527.75    21.2 2525.45    65.1 2523.47    74.6 2519.41    99.2 2518.98
   121.9 2520.31   134.7 2518.08   163.3 2517.02   191.4 2511.01     212 2510.83
   232.7  2507.8   244.2 2504.54   295.4 2496.07   302.7 2493.16   353.4 2493.16
   359.8 2495.86   361.6  2498.3   366.4 2509.72   369.4  2513.8   402.8  2542.6
   413.1 2558.44   420.5 2573.18   438.9 2601.21   449.2 2611.21   459.5 2616.62
     466 2621.78   490.5 2644.56   495.6 2651.64   500.1 2662.91   503.8 2664.29
#Mann= 3 ,-1,0
       0      .1       0   295.4    .045       0   359.8      .1       0
Bank Sta=295.4,359.8
XS Rating Curve= 0 ,0
Exp/Cntr(USF)=0,0
Exp/Cntr=0.3,0.1

Type RM Length L Ch R = 1 ,2035    ,336.8,338.9,339.5
XS GIS Cut Line= 2
  2220663.185197536253.4917560782221035.74159638536074.216496223
#Sta/Elev= 30
       0 2517.86    33.9 2516.24    49.9 2517.93    89.9 2513.14   103.2 2513.06
   126.8  2511.1   139.1 2508.76   143.1 2506.73  158.19 2495.98   160.9 2493.96
   165.3 2492.88   231.7 2492.94  239.77 2495.88   249.7 2498.34   258.6 2501.69
   276.7 2518.43   279.7 2524.05   280.8 2527.12   285.2 2542.63   285.7 2543.52
   294.7 2555.14   307.4  2567.6   324.6 2578.04   351.6 2597.54   360.7 2601.43
   369.5 2607.34   378.6 2610.61   387.3 2615.54   393.6 2618.17   413.4 2629.51
#Mann= 3 ,0,0
       0      .1       0  158.19    .045       0  239.77      .1       0
Bank Sta=158.19,239.77
XS Rating Curve= 0 ,0
Exp/Cntr(USF)=0,0
Exp/Cntr=0.3,0.1

Type RM Length L Ch R = 1 ,1696    ,351.6,349.5,349.5
XS GIS Cut Line= 2
2220793.43987798536558.8199330172221130.98157818536407.556432515
#Sta/Elev= 30
       0 2515.42    24.5 2514.34    38.1 2515.72    63.8 2513.11    69.9 2514.27
      76 2514.55    99.4 2511.87   121.4 2503.53   125.7 2501.23   130.4  2496.8
   138.9 2493.95   143.3 2491.95   150.7  2491.6   222.2 2491.67   226.5 2493.99
   230.9 2497.06   239.7 2499.88   244.1 2502.37   261.6 2517.35   269.7 2521.11
   279.1 2526.97   287.8 2530.89   296.7 2533.87   307.2  2540.9   318.6 2550.11
   321.1  2551.6   331.7 2556.31   351.6 2568.66   362.4 2572.31   369.9 2577.15
#Mann= 3 ,-1,0
       0      .1       0   138.9    .045       0   226.5      .1       0
Bank Sta=138.9,226.5
XS Rating Curve= 0 ,0
Exp/Cntr(USF)=0,0
Exp/Cntr=0.3,0.1

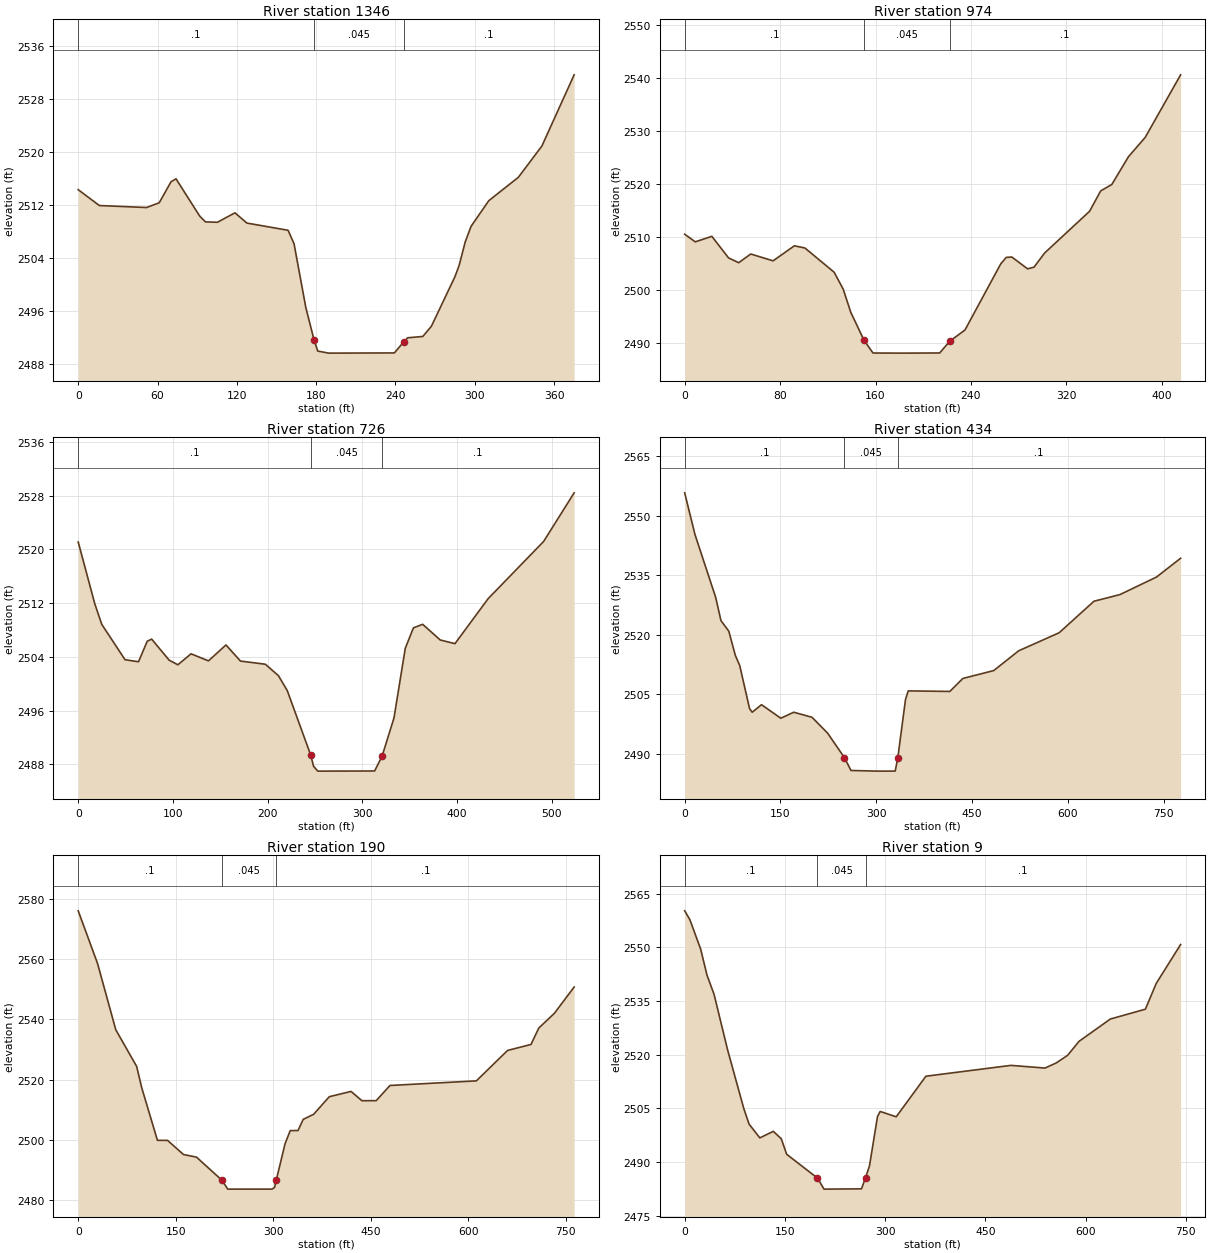
Type RM Length L Ch R = 1 ,1346    ,376,372.2,368.2
XS GIS Cut Line= 2
2220885.87868385 536908.966924922221222.01979607536742.296956775
#Sta/Elev= 30
       0 2514.34      16 2511.94    51.7 2511.64    61.3 2512.36    70.2 2515.53
      74 2515.98    91.9 2510.35    96.3 2509.47   105.3 2509.41   118.6 2510.84
   127.6 2509.29   158.8  2508.2   163.3 2506.16   172.2 2496.52  178.36 2491.68
   181.2 2489.94   189.6 2489.63   239.2 2489.66   246.3 2491.34   249.3 2491.95
   260.7 2492.15   267.2 2493.69   285.1 2501.22   288.3 2502.97   292.8 2506.45
   297.2 2508.79   310.6 2512.67     333 2516.21   350.8 2520.94   375.2  2531.7
#Mann= 3 ,0,0
       0      .1       0  178.36    .045       0   246.3      .1       0
Bank Sta=178.36,246.3
XS Rating Curve= 0 ,0
Exp/Cntr(USF)=0,0
Exp/Cntr=0.3,0.1

Type RM Length L Ch R = 1 ,974     ,247,247.7,248.4
XS GIS Cut Line= 2
2221080.56041134 537243.707449182221437.71034309537030.818078103
#Sta/Elev= 30
       0  2510.6     8.9 2509.16    22.8  2510.2    36.8 2506.13    45.3 2505.23
    55.4 2506.87    74.1 2505.58      92 2508.42   100.8    2508   125.3 2503.44
   132.9 2500.25   139.3 2495.86   150.4 2490.59   157.9  2488.2   182.5 2488.18
   213.8 2488.21   222.2 2490.41     235 2492.54     265 2505.01   269.6 2506.23
   274.3  2506.3   287.5 2504.07   292.9 2504.39   301.8 2507.06   339.5 2514.93
   348.8 2518.77   358.1 2519.97   372.1 2525.22   386.1 2528.85   415.8 2540.65
#Mann= 3 ,0,0
       0      .1       0   150.4    .045       0   222.2      .1       0
Bank Sta=150.4,222.2
XS Rating Curve= 0 ,0
Exp/Cntr(USF)=0,0
Exp/Cntr=0.3,0.1

Type RM Length L Ch R = 1 ,726     ,272.8,292.1,309.8
XS GIS Cut Line= 2
 2221116.9756985537505.6173991232221570.76620001 537243.70744918
#Sta/Elev= 30
       0 2521.09    17.5 2511.89    24.9 2508.82    49.5 2503.56    63.7 2503.26
    72.9 2506.31    77.6 2506.63    96.1 2503.49   105.3 2502.81   119.2 2504.44
   137.6 2503.39   156.1 2505.76   171.4 2503.36   197.7 2502.89   211.5 2501.19
   220.8 2498.98   245.7 2489.34   248.6 2487.71   253.1 2486.98   313.1    2487
     321  2489.2   333.6 2494.91   345.5 2505.26   354.1  2508.3   363.9 2508.83
   382.4  2506.5     398 2505.95     433 2512.64   491.7 2521.17   523.9  2528.4
#Mann= 3 ,-1,0
       0      .1       0   245.7    .045       0     321      .1       0
Bank Sta=245.7,321
XS Rating Curve= 0 ,0
Exp/Cntr(USF)=0,0
Exp/Cntr=0.3,0.1

Type RM Length L Ch R = 1 ,434     ,236.1,244,251.6
XS GIS Cut Line= 4
2221188.40568485537686.2932469452221618.38619091537603.658556856
2221776.65263125537493.0121074152221866.29026118537378.163894071
#Sta/Elev= 30
       0 2555.75    16.1 2545.26    48.6 2529.38    56.8 2523.55    69.1 2520.89
    79.3  2514.8    86.2 2512.24   101.6 2501.38   105.7 2500.46   120.3 2502.36
   150.5 2498.95   170.8 2500.46   199.4 2499.19   223.8  2495.2   250.2 2489.01
   260.4 2485.79   300.8 2485.62   329.7 2485.63   333.8 2489.05   345.8 2503.67
   350.1 2505.84   415.2  2505.7   435.6 2508.97     484 2510.96     523 2515.94
   586.4 2520.49   640.9 2528.43   681.5  2530.1   738.8 2534.52   776.6 2539.26
#Mann= 3 ,0,0
       0      .1       0   250.2    .045       0   333.8      .1       0
Bank Sta=250.2,333.8
XS Rating Curve= 0 ,0
Exp/Cntr(USF)=0,0
Exp/Cntr=0.3,0.1

Type RM Length L Ch R = 1 ,190     ,178.1,181.1,184.4
XS GIS Cut Line= 4
2221230.42332388537887.9779142812221628.19030668537866.969094767
 2221761.2461636537920.1914375372221982.53906249 537929.99555331
#Sta/Elev= 30
       0    2576    29.8 2558.52    57.8 2536.59    89.9 2524.44    97.9 2517.24
   121.9 2499.94   137.5 2499.91     162 2495.23     182 2494.37   221.2  2486.7
   230.1 2483.76   298.2 2483.76   302.2 2484.35   304.9 2486.87   318.2 2498.74
   326.2 2503.15   338.2 2503.18   346.2 2506.88   362.3 2508.57   386.3 2514.39
   419.8 2516.15   436.6 2513.06   458.5 2513.08   479.7 2518.11   612.6 2519.64
   660.7 2529.73   696.7 2531.71   708.7 2537.15   732.7 2542.04   763.1 2550.75
#Mann= 3 ,-1,0
       0      .1       0   221.2    .045       0   304.9      .1       0
Bank Sta=221.2,304.9
XS Rating Curve= 0 ,0
Exp/Cntr(USF)=0,0
Exp/Cntr=0.3,0.1

Type RM Length L Ch R = 1 ,9       ,,,
XS GIS Cut Line= 5
2221256.44686432538039.8106316492221382.65619828538055.044704613
2221610.86339018538055.401256223 2221881.4716721537959.484533329
2221980.38013938537946.746321635
#Sta/Elev= 30
       0 2560.17     7.8 2557.69    23.9  2549.5    33.3 2542.28      44 2536.83
    64.2 2521.37    88.4    2505    96.4  2500.6   112.5 2496.76   132.6 2498.59
   144.6 2496.51   152.6 2492.19   198.6 2485.55   208.6 2482.45   264.6 2482.53
   270.7 2485.66   276.6 2488.96   288.6 2502.75   292.6 2504.14   316.6 2502.65
     361 2513.98   488.3 2517.01   539.2 2516.26   556.2  2517.7   573.2 2519.83
   590.1 2523.71     637 2529.95   689.5  2532.7   705.7  2539.9   742.2 2550.76
#Mann= 3 ,0,0
       0      .1       0   198.6    .045       0   270.7      .1       0
Bank Sta=198.6,270.7
XS Rating Curve= 0 ,0
Exp/Cntr(USF)=0,0
Exp/Cntr=0.3,0.1
LCMann Table=0

Chan Stop Cuts=-1
Use User Specified Reach Order=0
Composite Channel Slope=5